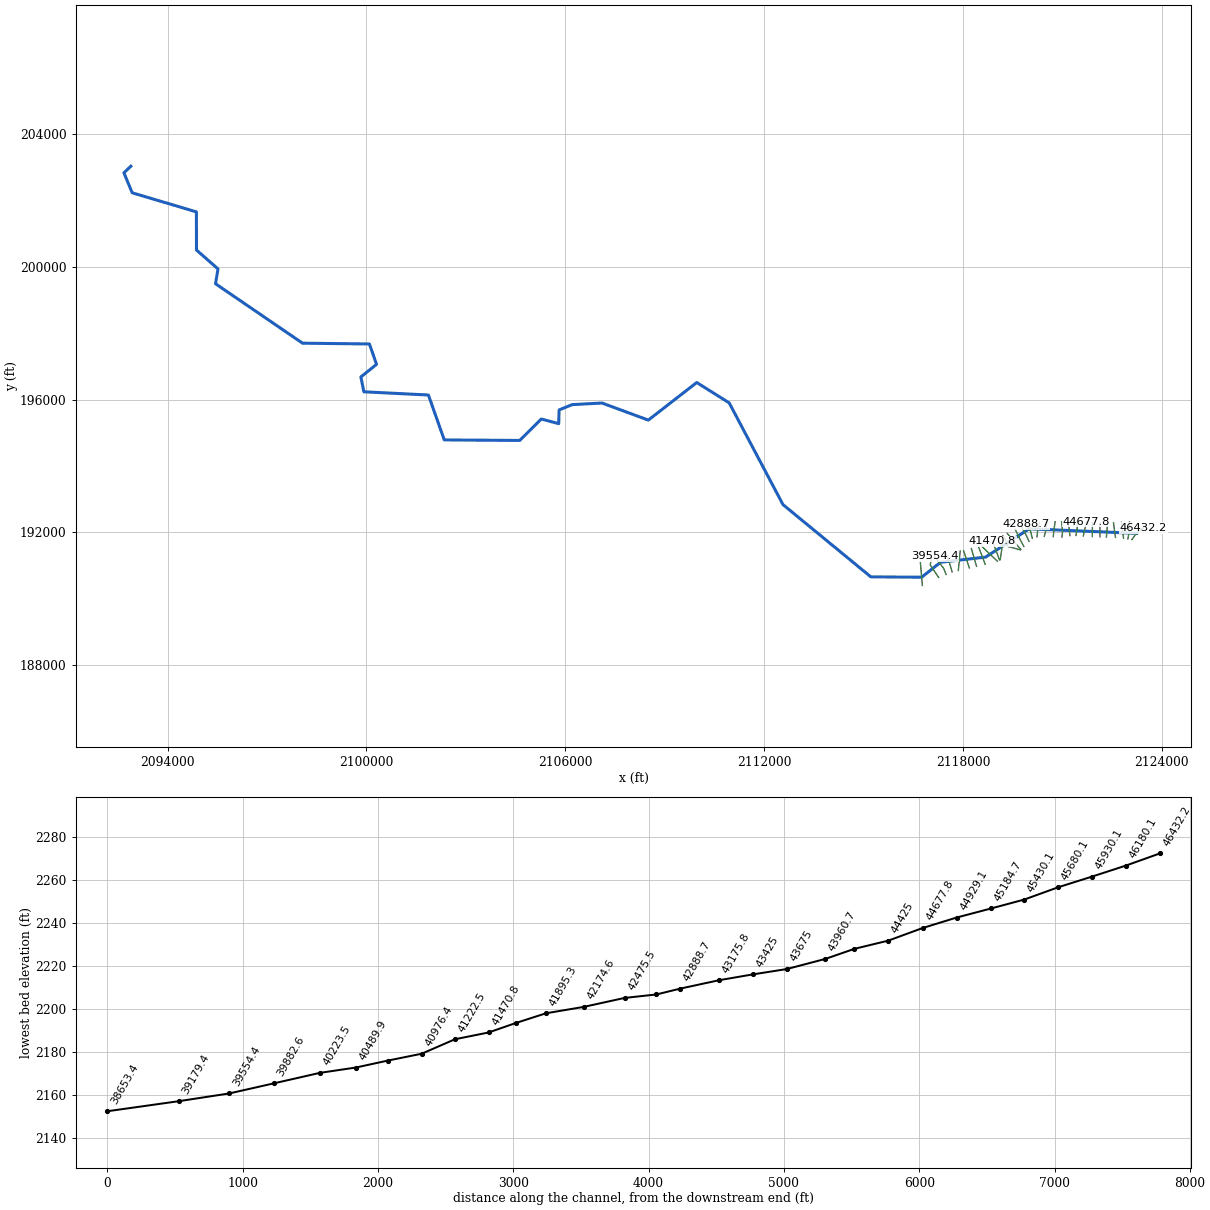
--- TRKYCK.prj (project) ---

Proj Title=TRKYCK
Current Plan=p01
Default Exp/Contr=0,0
English Units
Geom File=g01
Flow File=f01
Plan File=p01
BEGIN DESCRIPTION:
END DESCRIPTION:
DSS Export Rating Curves= 0
DSS Export Rating Curve Sorted= 0
DSS Export Volume Flow Curves= 0
DXF OffsetX= 0
DXF OffsetY= 0
DXF ScaleX= 0
DXF ScaleY= 0

--- TRKYCK.p01 (plan) ---

Plan Title=Floodplain
Program Version=4.00
Geom File=g01
Flow File=f01
K Sum by GR=0
Std Step Tol=0.01
Critical Tol=0.01
Num of Std Step Trials=20
Max Error Tol=0.3
Flow Tol Ratio=0.001
Split Flow NTrial=30
Split Flow Tol=0.02
Split Flow Ratio=0.02
Log Output Level=0
Friction Slope Method=1
Unsteady Friction Slope Method=2
Unsteady Bridges Friction Slope Method=1
Global Log Level=0
CheckData=False
Run HTab=0
Run UNet=0
Run PostProcess=0
UNET Theta=0
UNET Theta Warmup=0
UNET ZTol=0
UNET ZSATol=0
UNET MxIter=0
UNET MaxInSteps=0
UNET DtIC=0
UNET DtMin=0
UNET MaxCRTS=0
UNET WFStab=0
UNET SFStab=0
UNET WFX=0
UNET SFX=0
UNET DSS MLevel=0
UNET DZMax Abort=0
UNET Convert EG Bridges=0
UNET Use Existing IB Tables=0
UNET Froude Limit=0
UNET Froude Power=0
Write IC File=0
Echo Input=False
Echo Output=False
Write Detailed=0

--- TRKYCK.f01 (steady flow) ---

Flow Title=2010 USGS WV Regression Equation
Program Version=4.00
Number of Profiles=1
Profile Names=P100yr
River Rch & RM=TRKYCK,Main      ,46432.2
400.0948
River Rch & RM=TRKYCK,Main      ,45930.1
401.7552
River Rch & RM=TRKYCK,Main      ,45680.1
529.0419
River Rch & RM=TRKYCK,Main      ,43960.7
553.1040
River Rch & RM=TRKYCK,Main      ,43675
649.1572
River Rch & RM=TRKYCK,Main      ,42174.6
711.5788
River Rch & RM=TRKYCK,Main      ,41222.5
1212.801
River Rch & RM=TRKYCK,Main      ,37262.8
1283.341
River Rch & RM=TRKYCK,Main      ,34383.9
1405.005
River Rch & RM=TRKYCK,Main      ,32222.9
1541.954
River Rch & RM=TRKYCK,Main      ,29072.1
1614.592
River Rch & RM=TRKYCK,Main      ,20843.3
1793.414
River Rch & RM=TRKYCK,Main      ,19484.2
1944.095
River Rch & RM=TRKYCK,Main      ,17989
2110.512
River Rch & RM=TRKYCK,Main      ,16450.7
2197.090
River Rch & RM=TRKYCK,Main      ,13730.6
2433.368
River Rch & RM=TRKYCK,Main      ,104.6
2694.132
River Rch & RM=TRKYCK,Main      ,104.6
2694.082
Boundary for River Rch & Prof#=TRKYCK,Main      ,1
Up Type=0
Dn Type=3
Dn Slope=0.003675

--- TRKYCK.g01 (geometry) ---

Geom Title=LiDAR
Program Version=4.10

River Reach=TRKYCK          ,Main
Reach XY= 30
     2123244.238      191963.425     2119996.185      192100.359
     2118680.994      191246.106     2117325.525      191092.287
     2116752.609      190640.203     2115219.276       190650.62
     2112568.552      192830.597     2110945.202      195901.083
     2109966.078      196514.451     2108506.356      195380.423
      2107107.05      195895.701     2106208.439       195847.09
     2105813.697      195686.852     2105802.189      195272.784
     2105276.495      195413.062     2104625.106      194766.534
     2102348.876      194782.391     2101870.555      196137.373
     2099922.893      196234.453     2099833.439      196682.506
     2100305.662      197062.367     2100091.041      197677.303
     2098072.487       197701.14     2095448.182      199494.196
     2095522.328      199941.534     2094873.023      200511.673
     2094870.614      201662.791     2092933.808      202238.138
     2092683.287      202841.263     2092892.076      203039.989

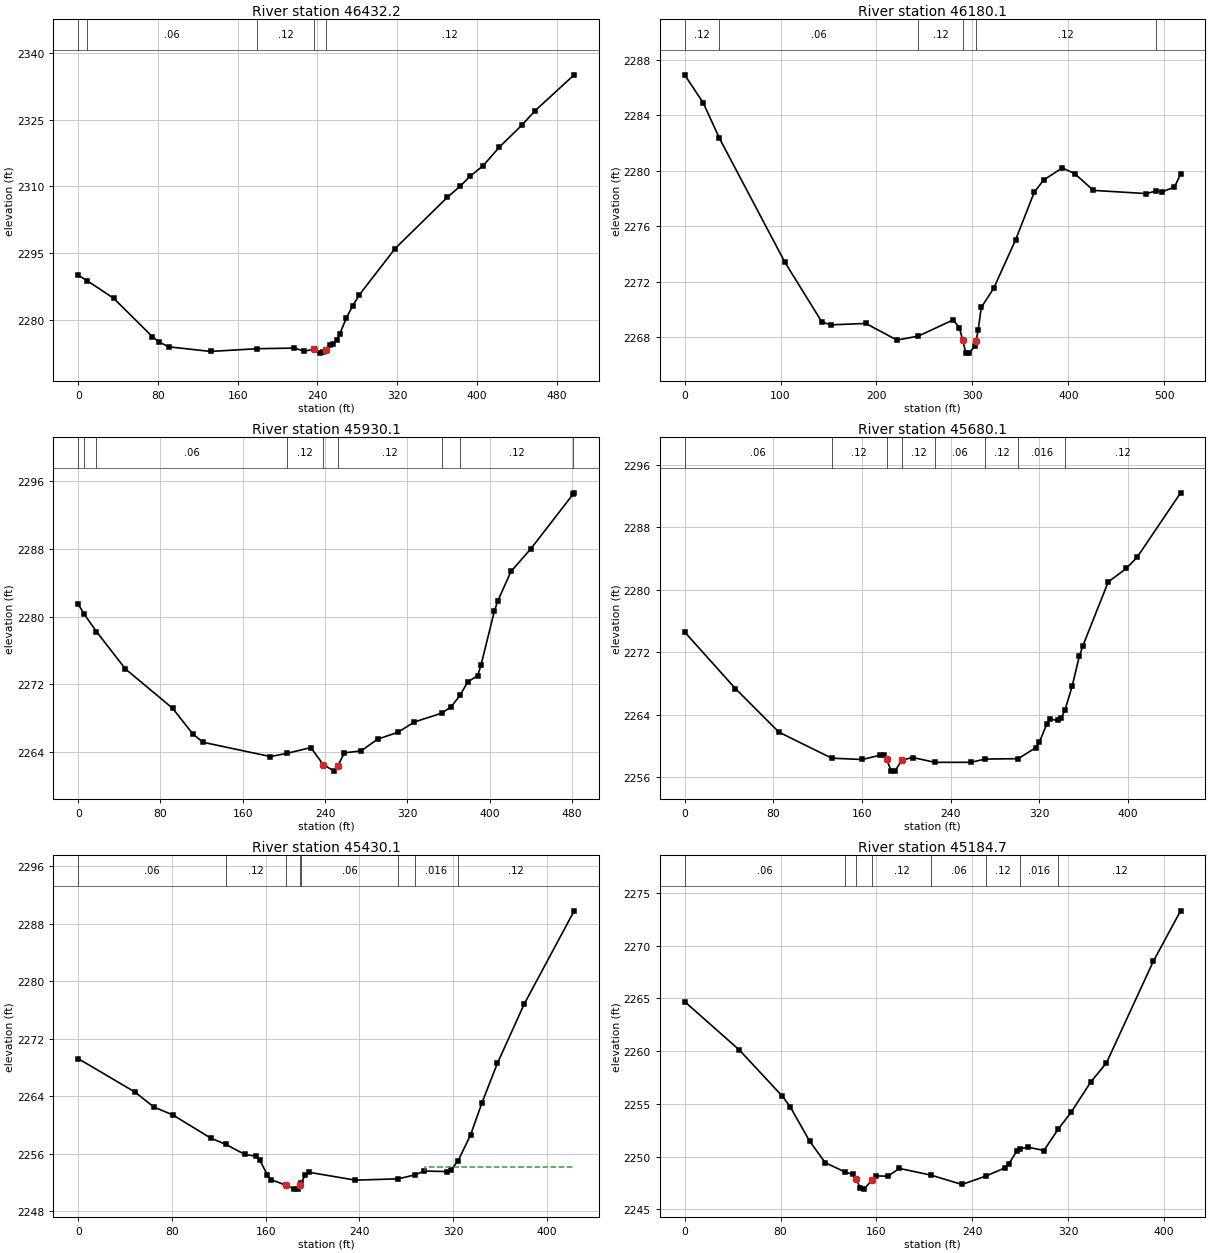
Type RM Length L Ch R = 1 ,46432.2 ,240.3,252.1,273.9
XS GIS Cut Line= 3
     2123097.716      191775.241     2123232.637      191969.162
     2123441.859      192125.682
#Sta/Elev= 30
       0 2290.04     8.82288.848    35.6 2284.85    74.4 2276.24    80.9 2275.07
    90.6 2273.96   132.7 2272.92  179.572273.536   216.8 2273.67   226.5    2273
   236.2 2273.36   242.8 2272.54     246 2272.71  248.152273.277   252.6 2274.26
   255.8 2274.59   259.1 2275.46   262.4  2276.9   268.9 2280.42   275.4 2283.21
     282 2285.65   317.9 2296.05   370.2 2307.55   383.2 2310.07     393 2312.28
   406.1 2314.65   422.4 2318.83   445.3 2323.84   458.3 2327.03   497.5 2335.08
#Mann= 5 ,-1 , 0
       0     .12       0     8.8     .06       0  179.57     .12       0
   236.2    .045       0  248.15     .12       0
Bank Sta=236.2,248.15
XS Rating Curve= 0 ,0
Exp/Cntr=0.3,0.1

Type RM Length L Ch R = 1 ,46180.1 ,241.2,250,239.7
XS GIS Cut Line= 3
     2122974.785       191795.73     2123029.893      192086.818
     2123022.669      192307.485
#Sta/Elev= 30
       0 2286.92    19.5 2284.89   36.162282.365   104.2 2273.45   143.2 2269.09
     153  2268.9   188.8    2269   221.4  2267.8  243.752268.092     280 2269.26
   286.5 2268.67   289.8 2267.81     293  2266.9   296.3 2266.86   302.8 2267.38
   303.8 2267.74     306 2268.53   309.2 2270.15   322.2 2271.54     345 2275.03
   364.4 2278.45   374.2 2279.34   393.7 2280.21   406.6  2279.8   426.1 2278.59
   481.3 2278.36  491.522278.551   497.6 2278.48   510.6 2278.83     517 2279.77
#Mann= 6 ,-1 , 0
       0     .12       0   36.16     .06       0  243.75     .12       0
   289.8    .045       0   303.8     .12       0  491.52    .016       0
Bank Sta=289.8,303.8
XS Rating Curve= 0 ,0
Exp/Cntr=0.3,0.1

Type RM Length L Ch R = 1 ,45930.1 ,248.5,250,248.1
XS GIS Cut Line= 3
     2122843.717      191817.575     2122812.732      192061.503
     2122779.301      192295.517
#Sta/Elev= 30
       0 2281.45    6.062280.245   17.652278.229    45.9 2273.81    91.8 2269.16
   111.5 2266.12   121.3 2265.15   186.9 2263.46  203.032263.841   226.2 2264.52
   238.32262.501   249.1 2261.74   252.4 2262.35   258.8  2263.9     275 2264.12
   291.2 2265.52   310.6 2266.31   326.8 2267.54  353.382268.581   362.5 2269.32
  371.372270.704   378.7 2272.27   388.4 2273.02   391.6 2274.23   404.6 2280.61
   407.8 2281.78   420.8 2285.32   440.2 2288.01  481.562294.509   482.3 2294.61
#Mann= 9 ,-1 , 0
       0     .06       0    6.06     .12       0   17.65     .06       0
  203.03     .12       0   238.3    .045       0   252.4     .12       0
  353.38    .016       0  371.37     .12       0  481.56     .06       0
Bank Sta=238.3,252.4
XS Rating Curve= 0 ,0
Exp/Cntr=0.3,0.1

Type RM Length L Ch R = 1 ,45680.1 ,252.9,250,241.4
XS GIS Cut Line= 3
     2122601.376      191840.543     2122572.465      192027.977
     2122541.633      192283.828
#Sta/Elev= 30
       0 2274.61    45.8 2267.36      85 2261.78   132.72258.438   160.2 2258.27
   176.6 2258.83   179.8 2258.81   182.12258.283   186.4 2256.82   189.6 2256.78
   196.2 2258.22     206 2258.52  225.682257.906   258.2 2257.91  271.072258.327
  300.832258.373   316.9  2259.8   320.1 2260.52   326.7 2262.83   329.9 2263.43
   336.4 2263.28   339.7  2263.6     343 2264.57   349.5 2267.63     356 2271.47
   359.3 2272.86   382.1 2281.02   398.4 2282.75   408.2 2284.19   447.4 2292.44
#Mann= 8 ,-1 , 0
       0     .06       0   132.7     .12       0   182.1    .045       0
   196.2     .12       0  225.68     .06       0  271.07     .12       0
  300.83    .016       0     343     .12       0
Bank Sta=182.1,196.2
XS Rating Curve= 0 ,0
Exp/Cntr=0.3,0.1

Type RM Length L Ch R = 1 ,45430.1 ,239.7,245.4,220.6
XS GIS Cut Line= 3
     2122326.499      191852.141     2122344.887       192032.13
     2122352.823      192274.542
#Sta/Elev= 30
       0 2269.24    48.5 2264.58    64.6  2262.5    80.8  2261.4   113.1 2258.18
     126  2257.3   142.2 2255.91   151.8 2255.65   155.1 2255.09   161.5 2253.05
   164.8 2252.37   177.7  2251.6   184.2 2251.07   187.5 2251.13  189.322251.619
  190.352251.898     194  2253.1   197.3 2253.41   236.6 2252.32   273.32252.505
  287.192253.047   295.6 2253.59   315.3 2253.51   318.6  2253.8  324.422255.038
     335 2258.62   344.8 2263.12   357.9 2268.59   380.9 2276.87   423.5 2289.82
#Mann= 8 ,-1 , 0
       0     .06       0     126     .12       0   177.7    .045       0
  189.32     .12       0  190.35     .06       0   273.3     .12       0
  287.19    .016       0  324.42     .12       0
#XS Ineff= 2 , 0
                          296.18         2254.19
Permanent Ineff=
       F       F
Bank Sta=177.7,189.32
XS Rating Curve= 0 ,0
Exp/Cntr=0.3,0.1

Type RM Length L Ch R = 1 ,45184.7 ,254.1,255.6,260.9
XS GIS Cut Line= 2
     2122132.436      191858.775     2122132.396      192272.502
#Sta/Elev= 30
       0 2264.69    45.6 2260.11    81.4 2255.74      88 2254.73   104.2 2251.48
   117.3 2249.42  133.692248.548   140.1 2248.32   143.12247.855   146.6 2247.02
   149.8 2246.92   156.4 2247.82   159.6 2248.17   169.4 2248.15   179.2 2248.88
  205.852248.238   231.3 2247.36  250.982248.146   267.1 2248.93   270.4 2249.31
   276.9  2250.5  279.54 2250.74   286.7 2250.89   299.7 2250.58   311.82252.635
   322.5 2254.22   338.8 2257.08   351.8 2258.87   390.9  2268.5   413.7 2273.29
#Mann= 8 ,-1 , 0
       0     .06       0  133.69     .12       0   143.1    .045       0
   156.4     .12       0  205.85     .06       0  250.98     .12       0
  279.54    .016       0   311.8     .12       0
Bank Sta=143.1,156.4
XS Rating Curve= 0 ,0
Exp/Cntr=0.3,0.1

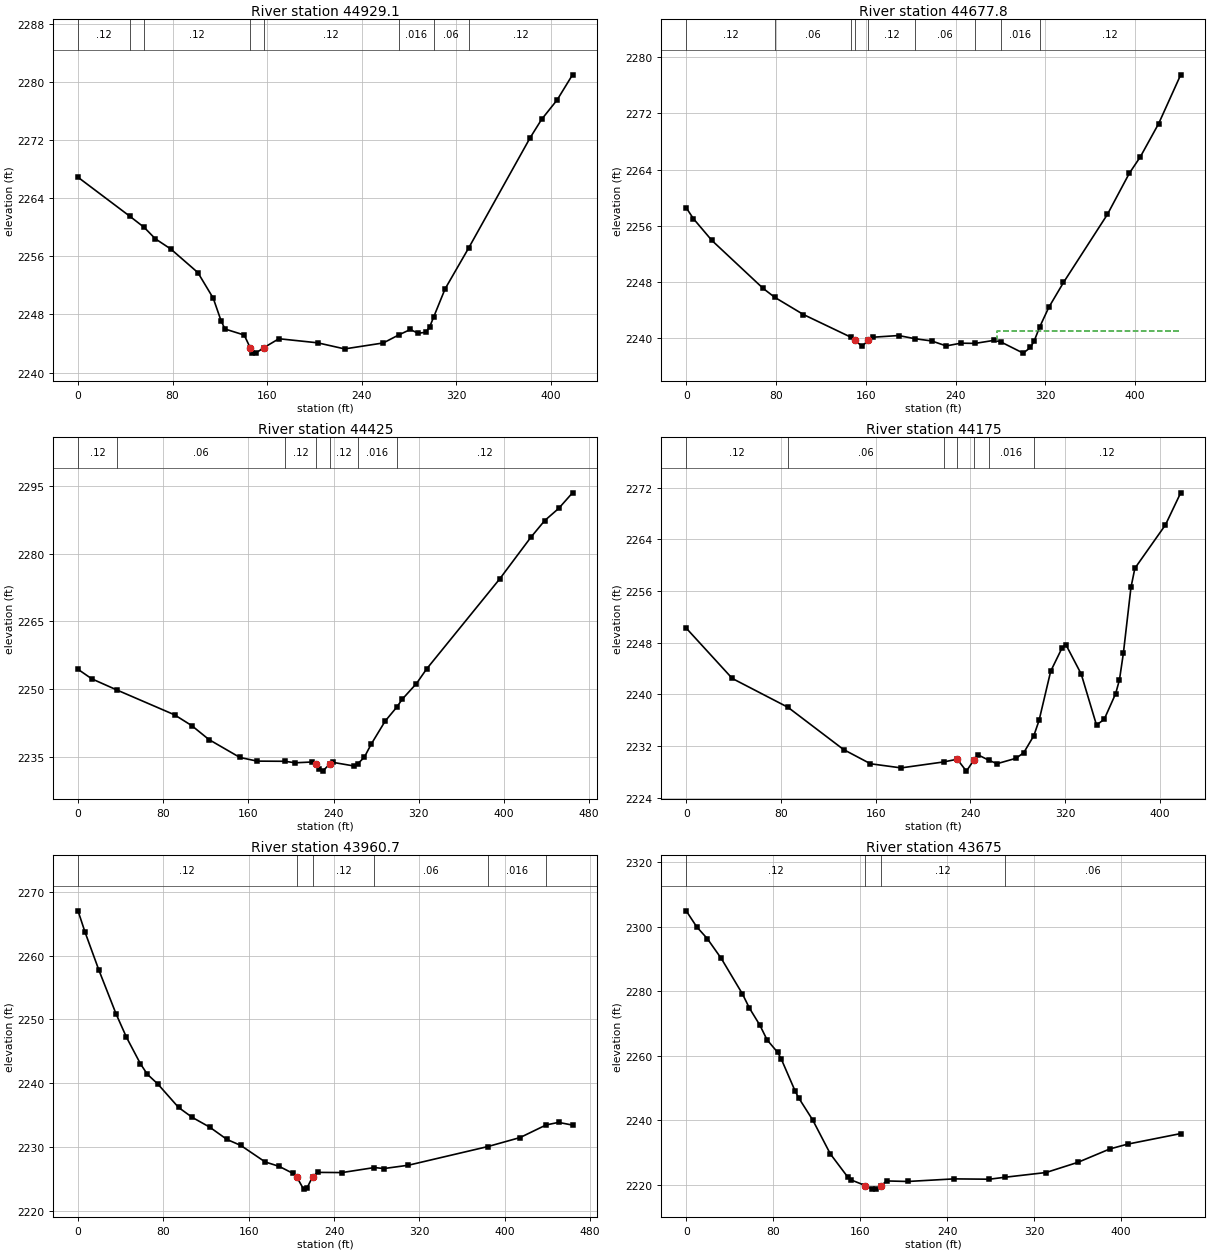
Type RM Length L Ch R = 1 ,44929.1 ,255.2,251.3,244.9
XS GIS Cut Line= 3
     2121902.221      191866.836     2121902.221      192023.797
     2121906.562      192285.236
#Sta/Elev= 30
       0 2266.87   43.832261.507   56.022259.971    65.4 2258.41    78.5    2257
   101.4 2253.76   114.4 2250.24     121 2247.15   124.3    2246   140.6 2245.17
  145.792243.388   147.2 2242.72   150.4 2242.68     157 2243.41     170 2244.66
   202.7  2244.1   225.6 2243.26   258.3 2244.08  271.482245.191   281.2 2245.93
   287.7 2245.41   294.2 2245.55   297.5 2246.27  301.022247.686   310.6 2251.52
  330.562257.147   382.5 2272.29   392.3 2274.84   405.4 2277.51   418.4 2280.96
#Mann= 8 ,-1 , 0
       0     .12       0   43.83     .06       0   56.02     .12       0
  145.79    .045       0     157     .12       0  271.48    .016       0
  301.02     .06       0  330.56     .12       0
Bank Sta=145.79,157
XS Rating Curve= 0 ,0
Exp/Cntr=0.3,0.1

Type RM Length L Ch R = 1 ,44677.8 ,250.5,252.8,257.4
XS GIS Cut Line= 2
      2121630.69      191884.811     2121725.791      192314.886
#Sta/Elev= 30
       0 2258.54     6.5 2256.97    22.8 2253.89    68.5 2247.04   78.882245.761
   104.4 2243.31  146.892240.059   150.12239.654   156.6 2238.78  162.36 2239.65
   166.4 2240.07   189.2 2240.31  204.142239.848   218.6 2239.54   231.6 2238.83
   244.7 2239.22  257.272239.188   274.1 2239.62  280.122239.412   300.2  2237.8
   306.7 2238.61     310 2239.55  314.912241.539     323 2244.33   336.1 2247.88
   375.2 2257.59   394.8 2263.48   404.6 2265.82   420.9 2270.56   440.5 2277.51
#Mann= 9 ,-1 , 0
       0     .12       0   78.88     .06       0  146.89     .12       0
   150.1    .045       0  162.36     .12       0  204.14     .06       0
  257.27     .12       0  280.12    .016       0  314.91     .12       0
#XS Ineff= 2 , 0
                          277.09          2240.9
Permanent Ineff=
       F       F
Bank Sta=150.1,162.36
XS Rating Curve= 0 ,0
Exp/Cntr=0.3,0.1

Type RM Length L Ch R = 1 ,44425   ,243.5,250,253.7
XS GIS Cut Line= 3
     2121408.899      191899.494     2121445.141      192126.314
     2121445.141      192360.918
#Sta/Elev= 30
       0 2254.44    12.9 2252.34   36.642249.859    90.6 2244.39   106.8    2242
   122.9 2238.93     152 2234.97   168.2 2234.16  194.482234.122   203.8 2233.79
     220 2233.97   223.2  2233.5   226.5 2232.42   229.7 2231.95   236.2 2233.48
   239.5 2233.88     259 2233.09  262.462233.518   268.8 2235.01   275.3 2237.91
   288.4    2243  299.122246.033   304.6 2247.88   317.7 2251.27   327.4 2254.54
   395.9 2274.39   425.2  2283.6   438.2 2287.29   451.3 2289.97   464.3 2293.42
#Mann= 7 ,-1 , 0
       0     .12       0   36.64     .06       0  194.48     .12       0
   223.2    .045       0   236.2     .12       0  262.46    .016       0
  299.12     .12       0
Bank Sta=223.2,236.2
XS Rating Curve= 0 ,0
Exp/Cntr=0.3,0.1

Type RM Length L Ch R = 1 ,44175   ,214,214.3,211.9
XS GIS Cut Line= 3
     2121226.965      191896.522     2121198.737      192131.466
     2121169.251      192310.059
#Sta/Elev= 30
       0 2250.27    38.9 2242.48   85.952238.015   132.9 2231.48   155.6 2229.28
   181.5 2228.64   217.72229.569   228.92229.983   236.6 2228.14   243.1 2229.88
   246.3 2230.67  255.812229.805   262.5 2229.29   278.6 2230.13   285.1    2231
  293.622233.644     298 2235.99   307.8 2243.59   317.4  2247.2   320.7 2247.69
   333.6 2243.16   346.5 2235.27     353 2236.15   362.7 2240.14   365.9 2242.28
   369.2 2246.39   375.6 2256.56   378.9 2259.52   404.7 2266.23   417.6  2271.2
#Mann= 7 ,-1 , 0
       0     .12       0   85.95     .06       0   217.7     .12       0
   228.9    .045       0   243.1     .12       0  255.81    .016       0
  293.62     .12       0
Bank Sta=228.9,243.1
XS Rating Curve= 0 ,0
Exp/Cntr=0.3,0.1

Type RM Length L Ch R = 1 ,43960.7 ,289,285.7,279.4
XS GIS Cut Line= 3
     2120985.998      191851.451     2121004.213      192016.012
     2120976.206      192312.555
#Sta/Elev= 30
       0    2267     6.5  2263.7    19.5 2257.75    35.7 2250.86    45.4 2247.22
    58.4  2243.1    64.9 2241.44    74.7 2239.92    94.2 2236.24   107.1 2234.68
   123.4 2233.16   139.6 2231.23   152.6 2230.29   175.4 2227.71   188.5 2227.02
   201.6 2225.91   204.8 2225.41   211.4 2223.46   214.7 2223.68  219.882225.403
   224.5 2226.08   247.4 2226.05  277.742226.835   286.7 2226.68   309.6  2227.2
  384.09 2230.12   414.3 2231.53  438.65  2233.5   450.3  2233.9   463.4 2233.48
#Mann= 6 ,-1 , 0
       0     .12       0   204.8    .045       0  219.88     .12       0
  277.74     .06       0  384.09    .016       0  438.65     .12       0
Bank Sta=204.8,219.88
XS Rating Curve= 0 ,0
Exp/Cntr=0.3,0.1

Type RM Length L Ch R = 1 ,43675   ,253.9,250,249.9
XS GIS Cut Line= 3
     2120724.167      191863.919     2120738.717       192037.96
     2120780.877      192315.081
#Sta/Elev= 30
       0 2304.85     9.7 2299.88    19.4 2296.25    32.3  2290.1    51.8  2279.1
    58.2 2274.73    67.9  2269.4    74.4 2264.93    84.1 2261.07    87.3 2259.13
   100.3 2249.03   103.5 2246.96   116.4 2240.13   132.6 2229.64   148.8  2222.4
     152 2221.54   164.9 2219.82   171.4 2218.73   174.6 2218.83  179.452219.838
   184.4 2221.26     204  2221.1   246.4  2221.9     279  2221.8  293.532222.414
   331.1 2223.87   360.4 2227.02   389.8 2231.16   406.1 2232.65     455 2235.92
#Mann= 4 ,-1 , 0
       0     .12       0   164.9    .045       0  179.45     .12       0
  293.53     .06       0
Bank Sta=164.9,179.45
XS Rating Curve= 0 ,0
Exp/Cntr=0.3,0.1

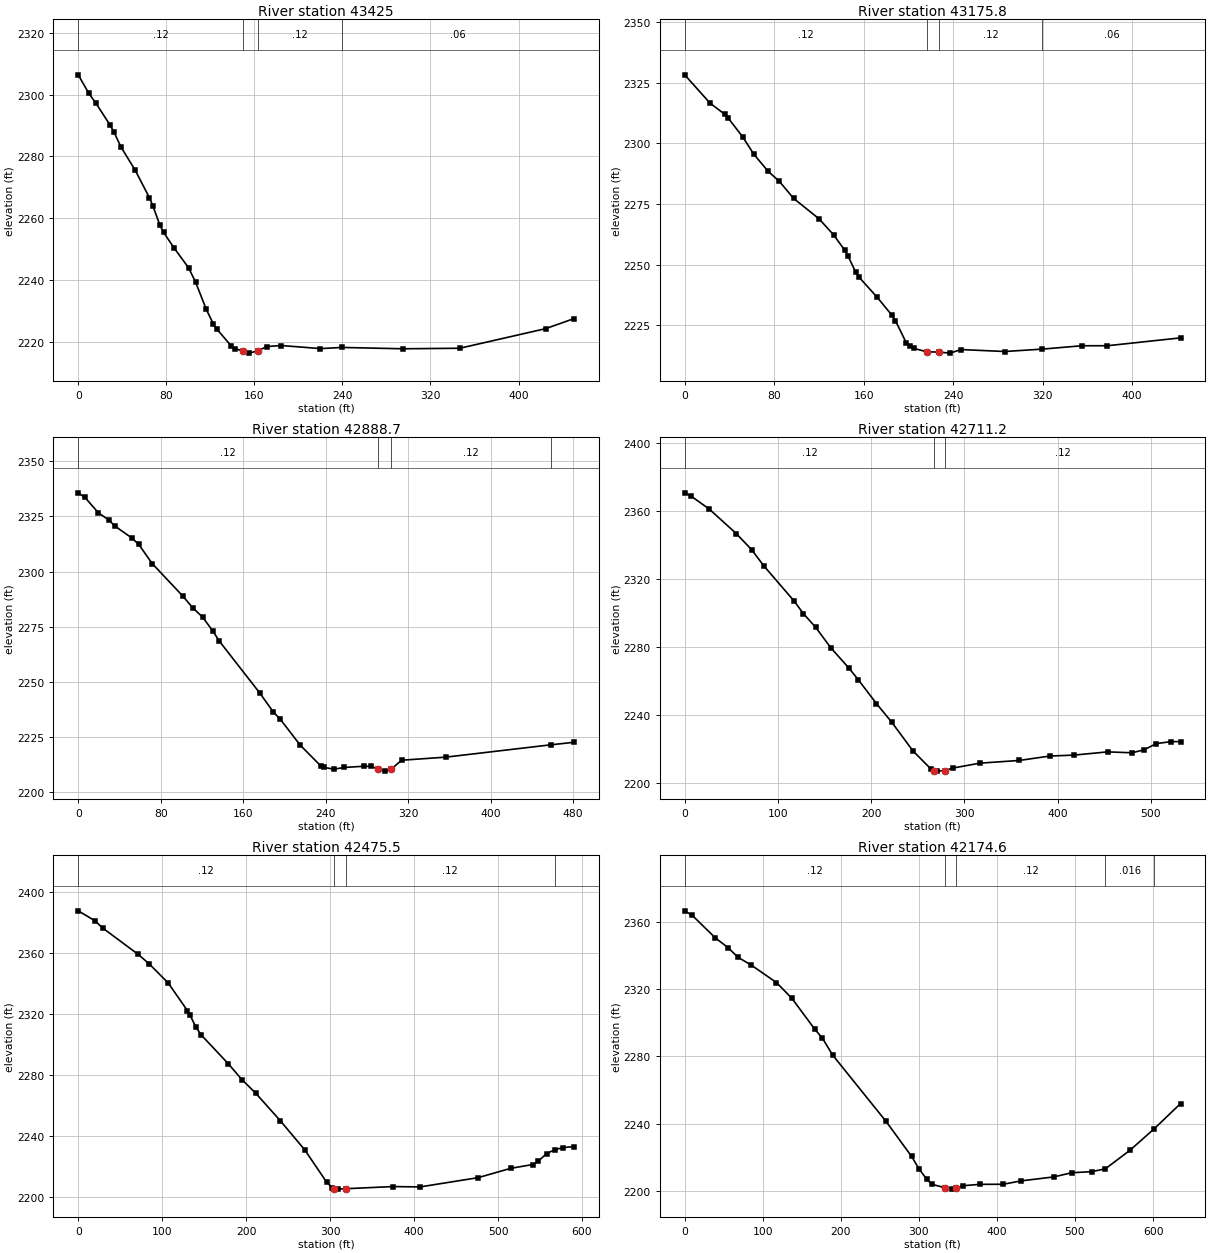
Type RM Length L Ch R = 1 ,43425   ,245.6,249.2,247.2
XS GIS Cut Line= 3
     2120453.038      191873.104     2120492.626      192026.376
     2120537.633      192315.075
#Sta/Elev= 30
       0 2306.38     9.7 2300.35    16.2 2297.12    29.1 2290.04    32.3 2287.98
    38.8 2283.03    51.7 2275.53    64.6 2266.64    67.8 2263.95    74.3 2257.61
    77.5 2255.37    87.2 2250.25   100.2 2243.92   106.6 2239.26   116.3 2230.45
   122.8 2225.66     126 2224.01   138.9 2218.62   142.2 2217.73  149.512216.942
   155.1 2216.25  163.312217.001   171.3 2218.37   184.3 2218.72     220 2217.72
  239.69 2218.09   294.7 2217.66   346.6 2217.83   424.5 2224.17   450.5 2227.45
#Mann= 4 ,-1 , 0
       0     .12       0  149.51    .045       0  163.31     .12       0
  239.69     .06       0
Bank Sta=149.51,163.31
XS Rating Curve= 0 ,0
Exp/Cntr=0.3,0.1

Type RM Length L Ch R = 1 ,43175.8 ,268.2,287.1,301.1
XS GIS Cut Line= 3
     2120232.147      191856.704     2120256.031      192079.552
     2120302.294      192293.795
#Sta/Elev= 30
       0 2328.26    22.7 2316.58    35.7 2312.03      39 2310.38      52 2302.58
    61.7 2295.59    74.7 2288.43    84.4 2284.47    97.4 2277.31   120.2 2268.87
   133.2 2262.24   142.9 2256.09   146.2 2253.41   152.7 2247.05   155.9 2244.83
   172.2  2236.5   185.2  2229.2   188.4 2226.92   198.1 2217.78   201.4 2216.29
   204.6 2215.56   216.32214.097   227.4 2213.97   237.2 2213.55     247 2215.02
   286.3 2214.22  319.75 2215.21     355 2216.59   377.9  2216.6   443.3 2219.84
#Mann= 4 ,-1 , 0
       0     .12       0   216.3    .045       0   227.4     .12       0
  319.75     .06       0
Bank Sta=216.3,227.4
XS Rating Curve= 0 ,0
Exp/Cntr=0.3,0.1

Type RM Length L Ch R = 1 ,42888.7 ,181.3,177.5,174.4
XS GIS Cut Line= 4
     2120090.071      191819.419     2120039.315      192025.346
     2119888.805      192240.027     2119889.992      192246.626
#Sta/Elev= 30
       0 2335.63     6.5 2333.56    19.6 2326.57    29.4 2323.41    35.9 2320.48
    52.2 2315.12    58.7 2312.28    71.8 2303.58   101.2 2289.01   110.9 2283.66
   120.7 2279.33   130.5 2273.11     137  2268.4   176.2 2244.94   189.2 2236.42
   195.8 2233.24   215.4 2221.36     235 2212.12   238.3 2211.32   248.1 2210.53
     258  2211.3   277.6 2211.86   284.2 2211.76   290.62210.561   297.3 2209.64
   303.8 2210.64   313.7 2214.58   356.3 2215.96  458.062221.538     481  2222.7
#Mann= 4 ,-1 , 0
       0     .12       0   290.6    .045       0   303.8     .12       0
  458.06     .06       0
Bank Sta=290.6,303.8
XS Rating Curve= 0 ,0
Exp/Cntr=0.3,0.1

Type RM Length L Ch R = 1 ,42711.2 ,235.1,235.7,233
XS GIS Cut Line= 3
     2119992.508      191722.747     2119874.537        191970.3
      2119746.95      192194.172
#Sta/Elev= 30
       0 2370.73     6.5 2368.92    26.1 2361.29    55.5 2346.65    71.8 2337.26
    84.9 2327.72   117.5 2306.95   127.3 2299.62   140.4 2291.63   156.7 2279.54
   176.3 2267.45   186.1 2260.77   205.7 2246.64     222 2235.76   244.8 2218.83
   264.4 2207.99   267.7 2207.08     271  2206.9   278.92207.214   287.3 2208.67
   316.6 2211.59     359 2213.19   391.6 2215.78   417.7 2216.34   453.6 2218.23
   479.7  2217.7   492.8 2219.45   505.8 2223.13   522.1 2224.27   531.9 2224.27
#Mann= 3 ,-1 , 0
       0     .12       0   267.7    .045       0   278.9     .12       0
Bank Sta=267.7,278.9
XS Rating Curve= 0 ,0
Exp/Cntr=0.3,0.1

Type RM Length L Ch R = 1 ,42475.5 ,264.9,300.9,248.7
XS GIS Cut Line= 3
     2119835.967      191567.635     2119698.073      191825.616
     2119570.531      192095.017
#Sta/Elev= 30
       0 2387.58    19.5 2381.21    29.2  2376.3    71.5 2359.01    84.5 2352.85
   107.3 2340.22     130 2322.27   133.3 2319.13   139.8 2311.77   146.3 2306.38
   178.8 2287.37     195 2276.99   211.3 2268.16   240.5  2250.2   269.8 2230.98
   295.8 2209.86   302.4 2206.28  304.862205.587   308.9 2205.28   318.7 2205.56
   374.4 2206.95   407.2 2206.73     476 2212.77   515.2 2218.92   541.5 2221.41
     548 2223.64   557.8 2228.59  567.47 2231.08   577.5 2232.49   590.6 2233.19
#Mann= 4 ,-1 , 0
       0     .12       0  304.86    .045       0   318.7     .12       0
  567.47    .016       0
Bank Sta=304.86,318.7
XS Rating Curve= 0 ,0
Exp/Cntr=0.3,0.1

Type RM Length L Ch R = 1 ,42174.6 ,284.4,279.2,325.7
XS GIS Cut Line= 3
     2119746.165      191478.653     2119520.986      191732.982
     2119334.485      191962.349
#Sta/Elev= 30
       0 2366.53     9.8 2363.81    39.2 2350.46    55.5 2344.67    68.6 2338.82
    84.9  2334.4   117.6  2323.9   137.2 2314.61   166.6 2296.19   176.4 2290.87
   189.4 2280.89     258 2241.35   290.7 2220.54   300.5 2212.92   310.3  2206.9
   316.8 2203.98   333.2 2201.96   342.9 2201.12   347.62201.622   355.9 2203.13
   378.7 2203.97   407.9 2204.01   430.6    2206   472.9 2208.38   495.6 2210.85
   521.6 2211.51  538.852213.194   570.3 2224.16  601.152236.867   635.3    2252
#Mann= 5 ,-1 , 0
       0     .12       0   333.2    .045       0   347.6     .12       0
  538.85    .016       0  601.15     .12       0
Bank Sta=333.2,347.6
XS Rating Curve= 0 ,0
Exp/Cntr=0.3,0.1

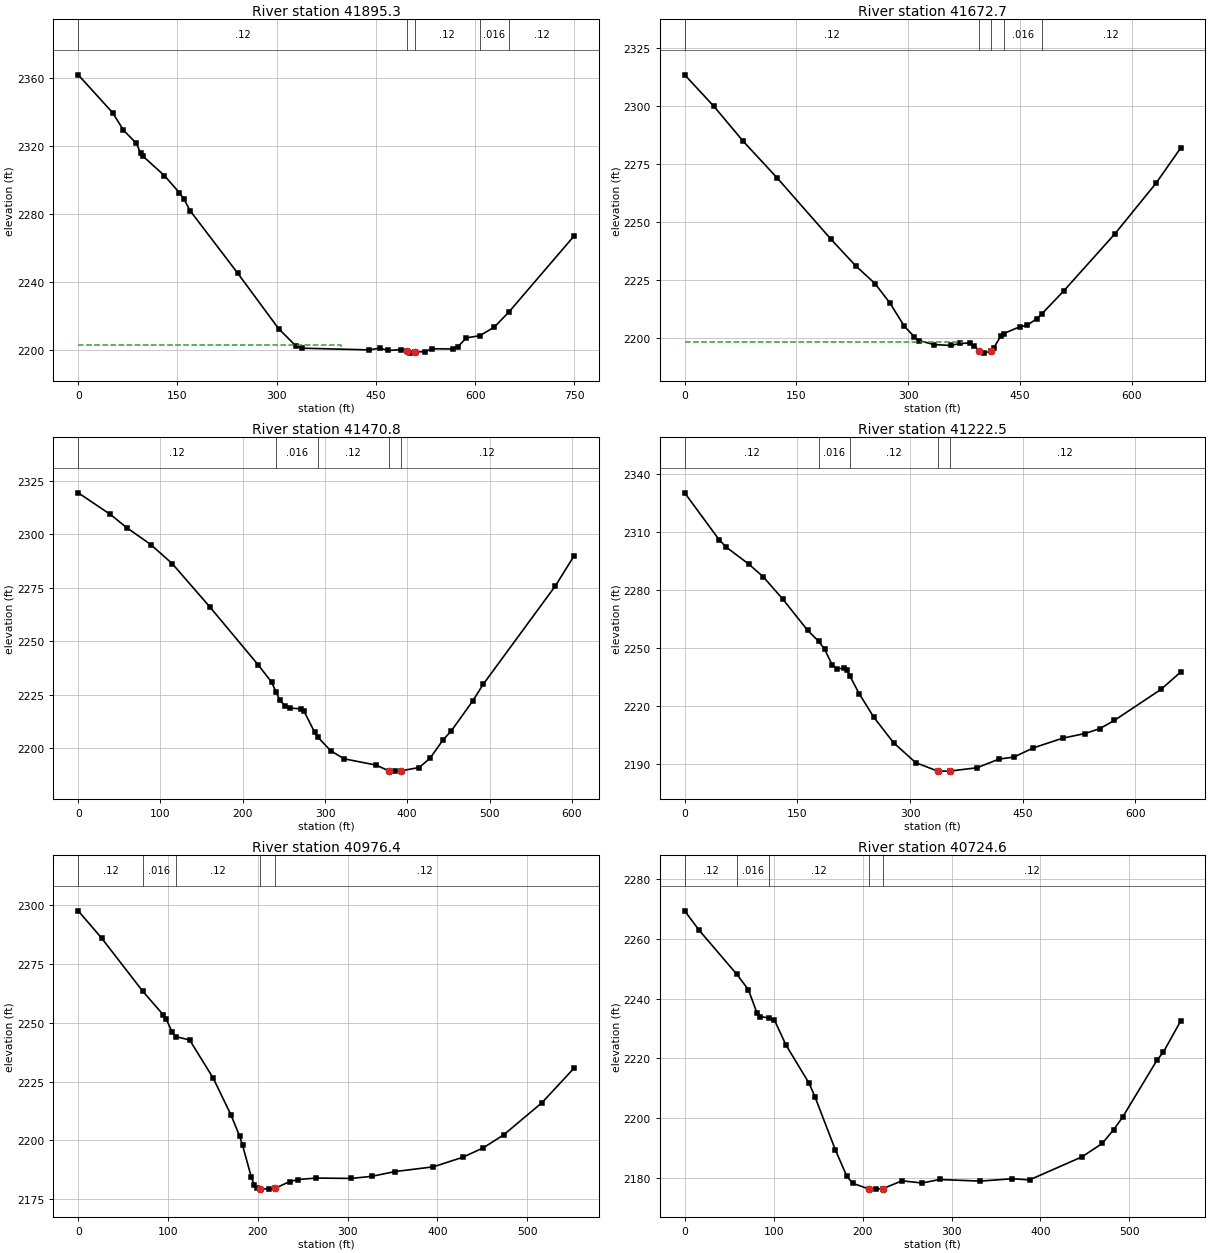
Type RM Length L Ch R = 1 ,41895.3 ,224.8,222.6,220.1
XS GIS Cut Line= 4
     2119732.786      191465.397     2119355.602      191566.815
     2119286.764      191763.995     2119202.256      191888.031
#Sta/Elev= 30
       0 2361.83    52.1 2339.51    68.4 2329.26    87.9 2321.52    94.4 2315.74
    97.6 2314.07   130.2 2302.57     153 2292.45   159.5 2288.98   169.2 2281.86
   240.9 2245.23   302.7 2212.61   328.7 2202.45   338.5 2201.05   439.5 2200.06
   455.8 2201.04   468.9 2199.71   488.5 2200.24  496.292199.128   501.5 2198.15
   508.62198.987   524.4 2198.92   534.2 2200.72   566.8  2200.6   573.3 2201.63
   586.4 2207.12  606.852208.389   628.8 2213.45  650.782222.287   749.5 2267.11
#Mann= 5 ,-1 , 0
       0     .12       0  496.29    .045       0   508.6     .12       0
  606.85    .016       0  650.78     .12       0
#XS Ineff= 2 , 0
          396.53 2202.74
Permanent Ineff=
       F       F
Bank Sta=496.29,508.6
XS Rating Curve= 0 ,0
Exp/Cntr=0.3,0.1

Type RM Length L Ch R = 1 ,41672.7 ,199.4,201.9,205
XS GIS Cut Line= 4
      2119123.42      191171.289      2119173.59      191504.978
     2119145.588      191616.985     2119050.894      191807.176
#Sta/Elev= 30
       0 2313.49    39.3 2299.89    78.6 2284.85   124.5 2268.94   196.6 2242.57
   229.3 2231.28   255.5 2223.54   275.2 2215.29   294.8 2205.17     308 2200.71
   314.5 2199.03   334.2 2197.33   356.7 2196.92   369.5 2197.79   382.3 2197.97
   388.8 2196.91   394.72194.462   401.6 2193.63   410.7  2194.5   414.4 2195.79
     424 2200.87   427.82202.019   449.7 2205.02   459.4 2205.56   472.5  2208.5
  478.912210.448   508.5 2220.39   577.1 2244.96   632.7 2266.94   665.4 2281.95
#Mann= 5 ,-1 , 0
       0     .12       0   394.7    .045       0   410.7     .12       0
   427.8    .016       0  478.91     .12       0
#XS Ineff= 2 , 0
          371.45 2198.46
Permanent Ineff=
       F       F
Bank Sta=394.7,410.7
XS Rating Curve= 0 ,0
Exp/Cntr=0.3,0.1

Type RM Length L Ch R = 1 ,41470.8 ,237.7,248.3,257.8
XS GIS Cut Line= 3
     2119099.626      191162.695     2118968.707      191525.063
     2118886.795      191726.694
#Sta/Elev= 30
       0 2319.35    39.2 2309.22    58.8 2303.11    88.2 2295.16   114.3 2286.24
     160    2266   218.8 2238.88   235.1 2230.84  240.292226.435   244.9 2222.58
   251.4 2219.62     258 2218.68     271 2218.32   274.3 2217.37   287.3  2207.5
  291.432205.055   306.9 2198.75   323.2 2194.97   362.4 2192.01   377.32189.352
   385.3 2189.21   391.8 2189.31   414.5  2190.9   427.5 2195.16   443.8 2203.94
   453.5    2208   479.5 2221.97   492.5  2229.9   580.2 2275.89   602.9 2289.93
#Mann= 5 ,-1 , 0
       0     .12       0  240.29    .016       0  291.43     .12       0
   377.3    .045       0   391.8     .12       0
Bank Sta=377.3,391.8
XS Rating Curve= 0 ,0
Exp/Cntr=0.3,0.1

Type RM Length L Ch R = 1 ,41222.5 ,255.8,246.1,235.6
XS GIS Cut Line= 3
     2119036.485      191123.779     2118773.052       191373.55
     2118559.513      191580.201
#Sta/Elev= 30
       0 2330.47    45.8 2306.14    55.6  2302.2      85 2293.59   104.6 2286.88
   130.8 2275.23   163.5 2259.19  178.282253.439   186.4 2249.24   196.2 2241.26
   202.8 2239.26   212.6 2239.38   215.8 2238.59  220.092235.326   232.2  2226.3
   251.8 2214.01     278 2200.83   307.4 2190.49   336.9 2186.06   353.2 2186.09
   389.1  2187.8   418.5 2192.31   438.1 2193.34   464.2 2198.12   503.4 2203.18
   532.8 2205.56   552.4 2208.07     572 2212.37     634 2228.46   660.2 2237.42
#Mann= 5 ,-1 , 0
       0     .12       0  178.28    .016       0  220.09     .12       0
   336.9    .045       0   353.2     .12       0
Bank Sta=336.9,353.2
XS Rating Curve= 0 ,0
Exp/Cntr=0.3,0.1

Type RM Length L Ch R = 1 ,40976.4 ,253.8,251.8,249.8
XS GIS Cut Line= 2
     2118669.334      191029.918     2118473.191      191546.422
#Sta/Elev= 30
       0 2297.59    26.2 2285.95   71.96 2263.38    94.8 2253.38    98.1 2251.58
   104.6 2246.04  108.552244.172   124.2 2242.68   150.4 2226.48     170 2211.01
   179.8 2201.87   183.1 2197.95   192.9 2184.32   196.2 2181.08   199.4 2179.81
   202.7 2179.54   212.5 2179.32     219 2179.62   235.4 2182.49   245.2 2183.41
   264.8 2184.02     304 2183.87   326.9 2184.75   353.1 2186.79   395.6  2188.8
   428.3 2192.84   451.2 2196.85     474 2202.38   516.5    2216   552.5 2230.77
#Mann= 5 ,-1 , 0
       0     .12       0   71.96    .016       0  108.55     .12       0
   202.7    .045       0     219     .12       0
Bank Sta=202.7,219
XS Rating Curve= 0 ,0
Exp/Cntr=0.3,0.1

Type RM Length L Ch R = 1 ,40724.6 ,233.3,234.7,235
XS GIS Cut Line= 3
     2118408.327      190969.851     2118348.144      191176.074
     2118252.161        191505.1
#Sta/Elev= 30
       0 2269.45    16.3 2262.92   58.622248.153    71.6 2243.02    81.4 2235.11
    84.6 2233.96   95.072233.559   100.9 2232.83   113.9 2224.43     140 2211.55
   146.5 2207.06   169.3 2189.37   182.3 2180.41   188.8 2178.08   206.72176.192
   214.8 2176.11   222.92176.261   244.2  2178.9     267 2178.16   286.6 2179.34
   332.3  2178.8   368.2 2179.59   387.8 2179.22   446.6 2186.92   469.4 2191.42
   482.5  2196.1   492.3 2200.22   531.4 2219.54     538 2221.95   557.6 2232.46
#Mann= 5 ,-1 , 0
       0     .12       0   58.62    .016       0   95.07     .12       0
   206.7    .045       0   222.9     .12       0
Bank Sta=206.7,222.9
XS Rating Curve= 0 ,0
Exp/Cntr=0.3,0.1

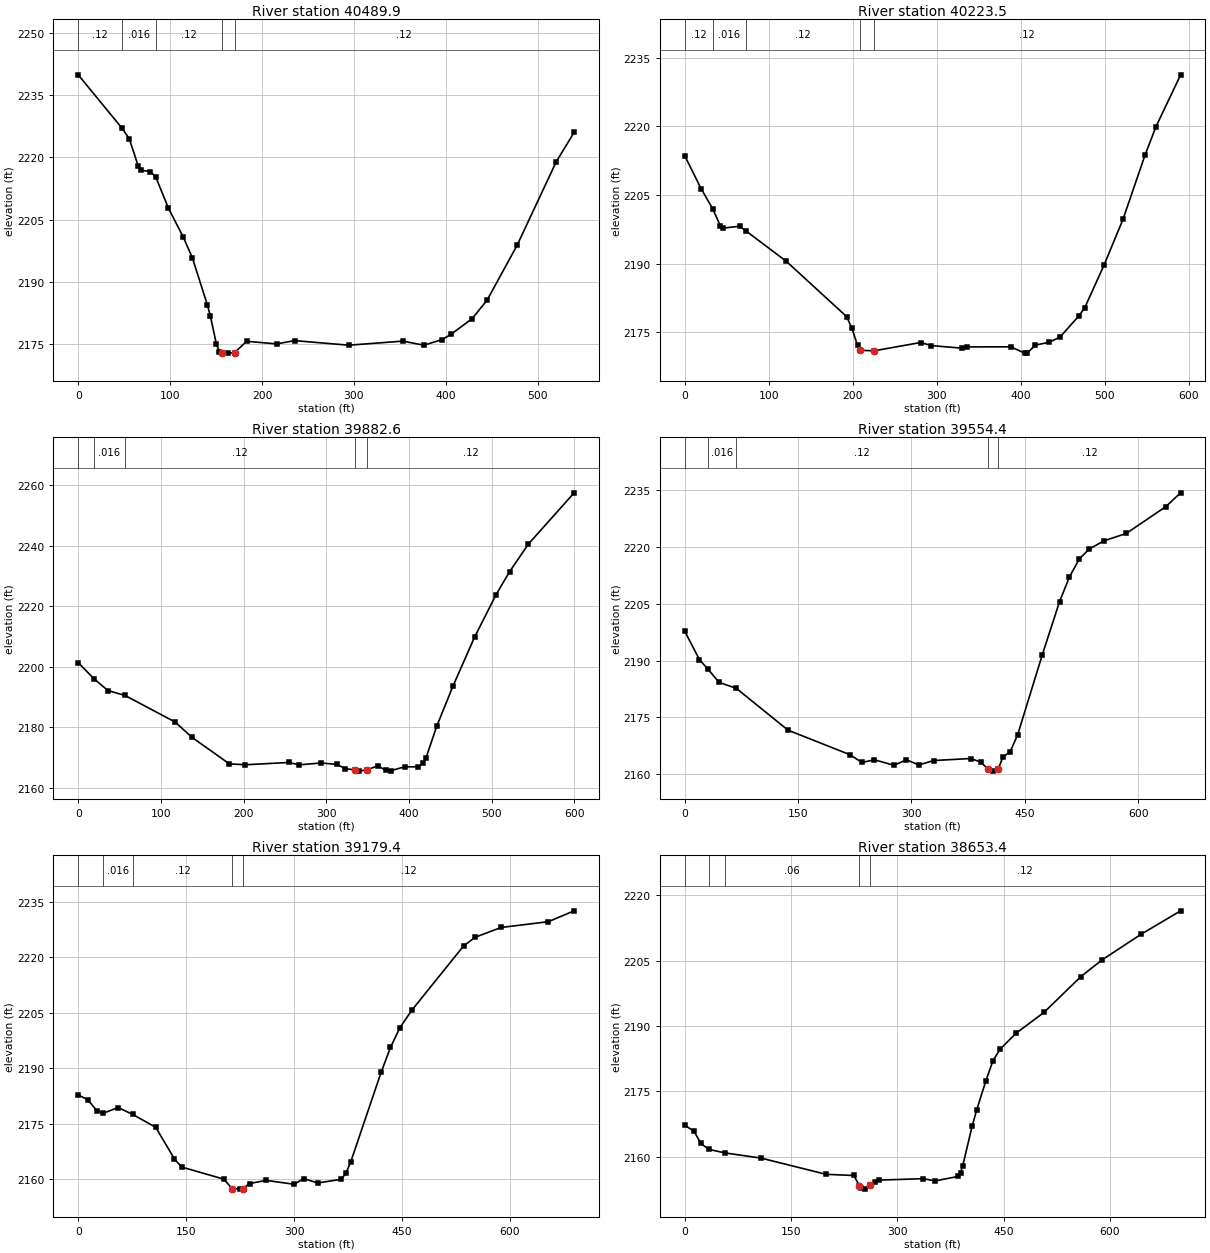
Type RM Length L Ch R = 1 ,40489.9 ,275.6,266.3,256.1
XS GIS Cut Line= 2
     2118191.349      190919.918     2118020.659      191431.865
#Sta/Elev= 30
       0 2239.89   47.822227.007    55.6  2224.5    65.4 2217.84    68.7 2216.91
    78.5  2216.6    84.3 2215.34    98.1 2207.83   114.5 2200.74   124.3 2195.78
   140.6 2184.46   143.9 2181.74   150.4 2174.99   153.7 2173.27   156.52173.015
   163.5  2172.9   170.1 2173.01   183.2 2175.75   215.9 2175.12   235.5 2175.91
   294.4 2174.81   353.2 2175.79   376.1 2174.81   395.8 2176.15   405.6 2177.42
   428.4 2181.16   444.8 2185.62   477.5 2198.84     520 2218.92   539.6 2226.05
#Mann= 5 ,-1 , 0
       0     .12       0   47.82    .016       0    84.3     .12       0
   156.5    .045       0   170.1     .12       0
Bank Sta=156.5,170.1
XS Rating Curve= 0 ,0
Exp/Cntr=0.3,0.1

Type RM Length L Ch R = 1 ,40223.5 ,330.6,340.9,349.9
XS GIS Cut Line= 3
     2117858.838      190843.396      2117880.91      191067.496
     2117914.706      191430.696
#Sta/Elev= 30
       0 2213.62    19.6 2206.36   33.422201.962    42.4 2198.28    45.7 2197.76
    65.3 2198.17   72.562197.187   120.8 2190.51   192.6 2178.41   199.1  2175.8
   205.6 2172.08   208.9 2171.04   225.2 2170.91   280.6 2172.73   293.6 2172.06
   329.4  2171.5   335.9 2171.77     388 2171.79   404.3 2170.41   407.6 2170.45
   417.3 2172.18   433.6 2172.77   446.6 2173.94   469.4 2178.64     476 2180.37
   498.8 2189.62   521.6 2199.76   547.6  2213.7   560.6 2219.92     590 2231.29
#Mann= 5 ,-1 , 0
       0     .12       0   33.42    .016       0   72.56     .12       0
   208.9    .045       0   225.2     .12       0
Bank Sta=208.9,225.2
XS Rating Curve= 0 ,0
Exp/Cntr=0.3,0.1

Type RM Length L Ch R = 1 ,39882.6 ,318.1,328.2,334.7
XS GIS Cut Line= 3
     2117671.418      190799.761     2117578.973      191115.958
      2117491.53      191371.691
#Sta/Elev= 30
       0 2201.35   18.952196.046    35.9 2192.13    56.52190.527   117.4  2181.7
     137  2176.8   182.7 2167.93   202.2 2167.62   254.4 2168.38   267.5  2167.6
   293.6 2168.22   313.1 2167.72   322.9 2166.33   334.52165.942   339.2 2165.52
     349 2165.92     362 2167.25   371.8 2165.85   378.3 2165.69   394.6 2166.94
   410.8 2166.95   417.4 2168.12   420.6 2169.94   433.6 2180.39   453.2 2193.63
   479.2 2209.72   505.3 2223.82   521.6 2231.38   544.4 2240.52   599.7 2257.43
#Mann= 5 ,-1 , 0
       0     .12       0   18.95    .016       0    56.5     .12       0
   334.5    .045       0     349     .12       0
Bank Sta=334.5,349
XS Rating Curve= 0 ,0
Exp/Cntr=0.3,0.1

Type RM Length L Ch R = 1 ,39554.4 ,364.4,375,368
XS GIS Cut Line= 3
     2117489.304        190724.9     2117419.972      190900.604
     2117137.496      191272.979
#Sta/Elev= 30
       0 2197.79    19.5 2190.26    30.82187.735    45.6 2184.25   68.352182.678
   136.8 2171.64   218.3 2165.21   234.6 2163.13     251 2163.83   277.1 2162.38
   293.5 2163.84   309.8 2162.47   329.4 2163.63   378.5 2164.17   391.5 2163.23
   401.3 2161.44   407.9 2160.84  415.112161.492     421 2164.49   430.8 2165.99
   440.6 2170.41   473.2 2191.51   496.1 2205.56   509.2 2212.09   522.3 2216.84
   535.4 2219.46     555 2221.61   584.4 2223.56   636.7 2230.62   656.3 2234.27
#Mann= 5 ,-1 , 0
       0     .12       0    30.8    .016       0   68.35     .12       0
   401.3    .045       0  415.11     .12       0
Bank Sta=401.3,415.11
XS Rating Curve= 0 ,0
Exp/Cntr=0.3,0.1

Type RM Length L Ch R = 1 ,39179.4 ,537.7,526,476.9
XS GIS Cut Line= 3
     2117266.096      190633.147     2117012.778      191005.611
     2117049.237      191241.767
#Sta/Elev= 30
       0 2182.74    13.1 2181.48    26.1 2178.42   35.142177.812    55.5 2179.33
   75.812177.458   107.7 2173.98   133.8 2165.41   143.6 2163.22   202.4 2159.92
  213.852157.383   225.2 2157.22   228.62157.362   238.3 2158.73   261.1 2159.59
   300.3 2158.54   313.4 2160.08   332.9 2158.89   365.6 2159.87   372.1 2161.53
   378.6 2164.47   421.1  2188.9   434.1 2195.63   447.2 2200.97   463.5 2205.64
   535.6  2223.1   551.9 2225.49   587.9 2228.13   653.4 2229.69   689.4 2232.64
#Mann= 5 ,-1 , 0
       0     .12       0   35.14    .016       0   75.81     .12       0
  213.85    .045       0   228.6     .12       0
Bank Sta=213.85,228.6
XS Rating Curve= 0 ,0
Exp/Cntr=0.3,0.1

Type RM Length L Ch R = 1 ,38653.4 ,318.5,316.7,344.6
XS GIS Cut Line= 2
     2116774.263      190390.704     2116714.326      191087.968
#Sta/Elev= 30
       0 2167.22    13.1 2165.87    22.9 2163.05   33.652161.701   56.692160.877
   107.9 2159.68   199.5 2155.96   238.7 2155.69  246.422153.388   248.5 2152.81
   255.1 2152.56   261.6 2153.43   268.2 2154.31   274.7 2154.64   336.8 2154.96
   353.2 2154.44   385.9 2155.48   389.2 2156.31   392.4 2157.94   405.5 2166.95
     412 2170.72   425.1 2177.48   434.9 2181.99   444.8 2184.64   467.6 2188.36
   506.9 2193.12   559.2 2201.38   588.6 2205.15   644.2  2211.1   699.8 2216.46
#Mann= 5 ,-1 , 0
       0     .12       0   33.65    .016       0   56.69     .06       0
  246.42    .045       0   261.6     .12       0
Bank Sta=246.42,261.6
XS Rating Curve= 0 ,0
Exp/Cntr=0.3,0.1