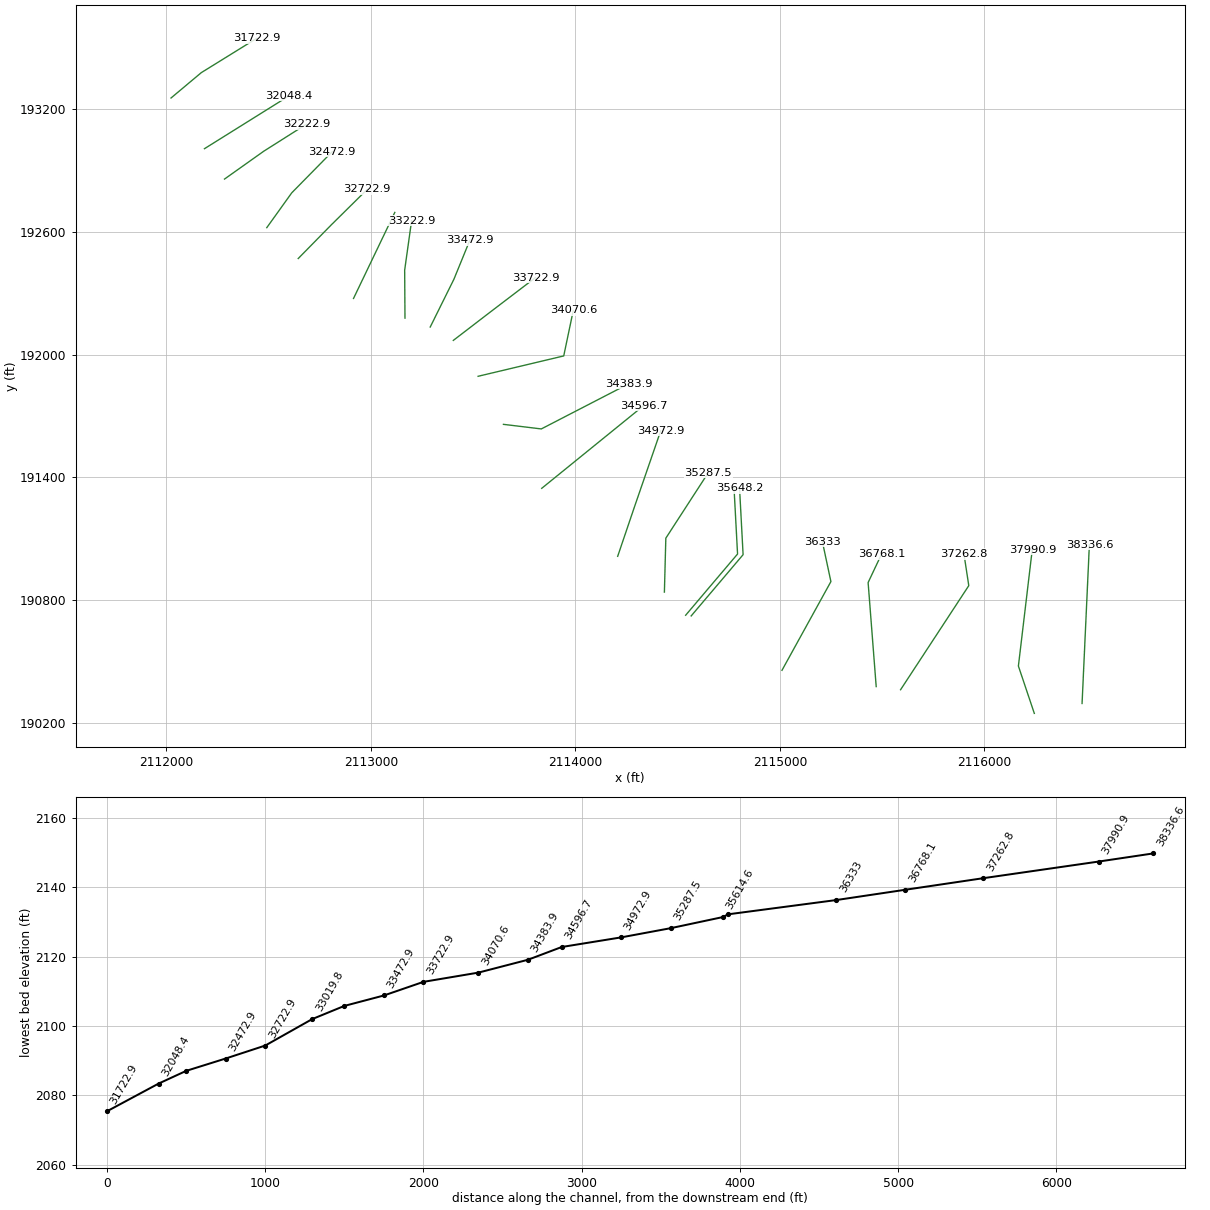
HEC-RAS study TRKYCK.prj: TRKYCK

--- TRKYCK.g01 (geometry) --- (continued)

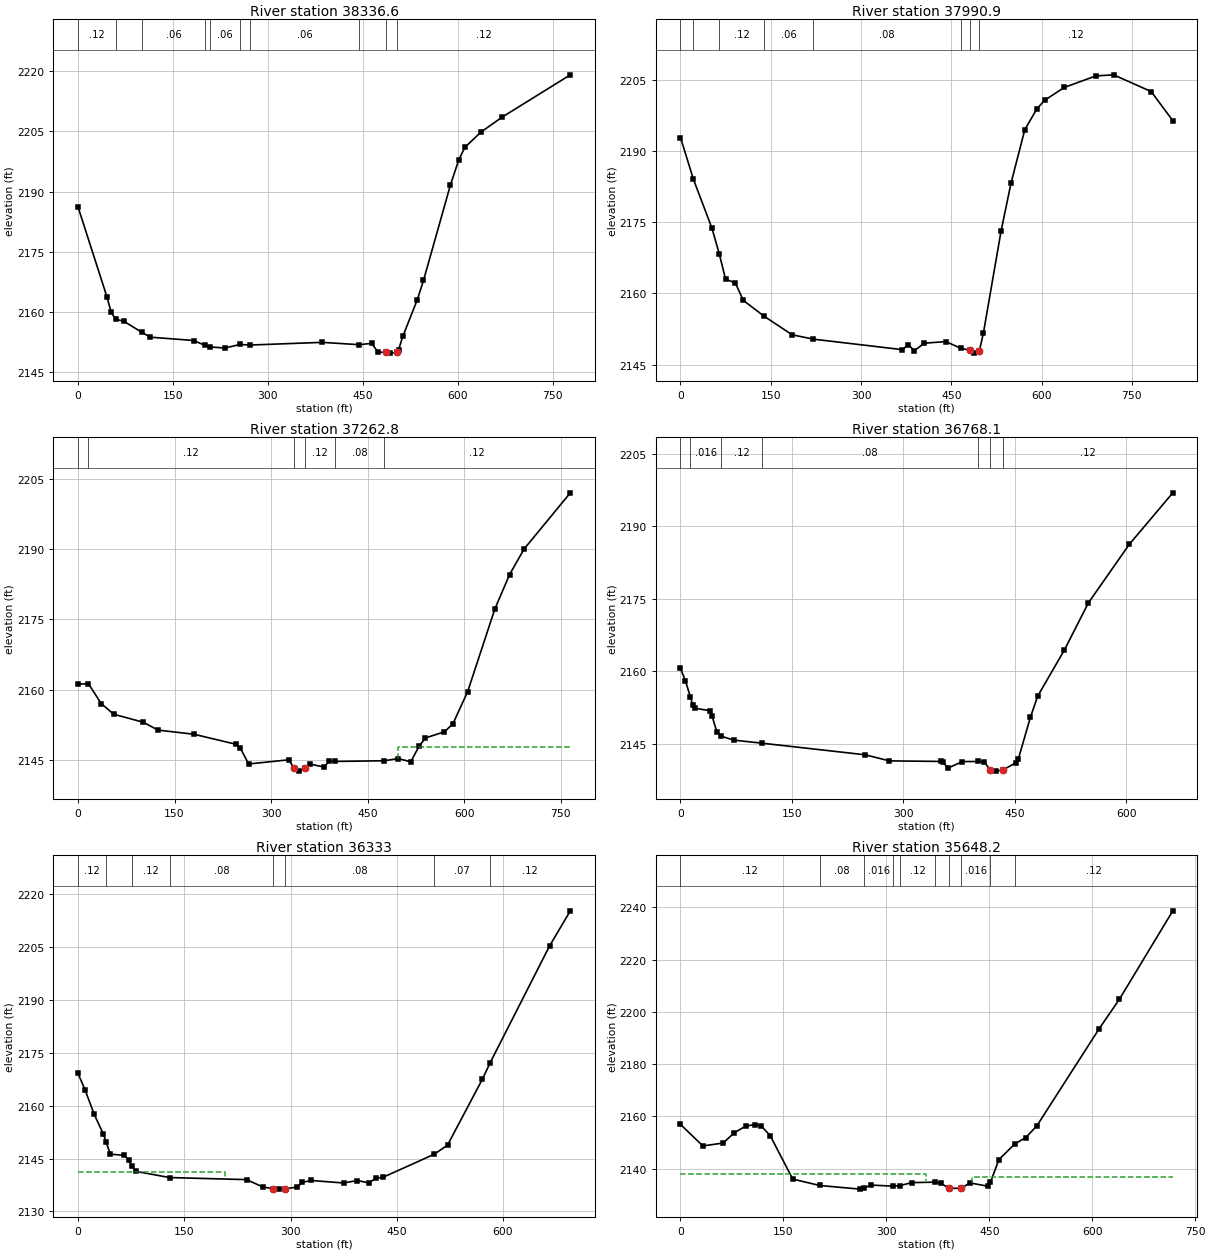
Type RM Length L Ch R = 1 ,38336.6 ,346.2,345.7,343.9
XS GIS Cut Line= 2
     2116478.317      190293.934     2116514.063      191070.881
#Sta/Elev= 30
       0 2186.17    45.8 2163.72    52.3 2159.96   59.552158.187    71.9 2157.75
  101.272154.913   114.4 2153.74     183 2152.91  200.752151.676  208.632151.307
     232 2151.04   255.6 2151.92  272.042151.785   385.6 2152.45  444.48 2151.87
     464 2152.21   473.8 2150.02   486.62149.937   493.5 2149.77   503.3 2149.94
   506.5 2150.65   513.1 2153.93   535.9 2163.02   545.8 2167.86   588.2 2191.57
   601.3  2197.8   611.1 2201.02   637.2 2204.89   669.9 2208.53   777.8 2219.08
#Mann= 10 ,-1 , 0
       0     .12       0   59.55    .016       0  101.27     .06       0
  200.75     .12       0  208.63     .06       0   255.6     .12       0
  272.04     .06       0  444.48     .12       0   486.6    .045       0
   503.3     .12       0
Bank Sta=486.6,503.3
XS Rating Curve= 0 ,0
Exp/Cntr=0.3,0.1

Type RM Length L Ch R = 1 ,37990.9 ,738,728.1,701.2
XS GIS Cut Line= 3
     2116244.706      190245.565     2116166.887      190477.075
     2116234.686      191047.043
#Sta/Elev= 30
       0 2192.82   21.562184.006    52.1 2173.79   64.492168.315    74.9 2162.98
    91.2 2162.21   104.2 2158.54  139.072155.181   185.6 2151.28  220.692150.365
   368.9 2148.15   378.7 2149.21   388.6 2147.91     405 2149.51     441 2149.85
  465.922148.435   481.12148.012     487 2147.42   496.8 2147.96   503.4 2151.64
   532.9 2173.21   549.3 2183.22   572.2 2194.47   591.9 2198.78     605 2200.65
   637.8 2203.37   690.3  2205.8   719.8 2206.03   782.2 2202.51   818.2 2196.38
#Mann= 8 ,-1 , 0
       0     .12       0   21.56    .016       0   64.49     .12       0
  139.07     .06       0  220.69     .08       0  465.92     .12       0
   481.1    .045       0   496.8     .12       0
Bank Sta=481.1,496.8
XS Rating Curve= 0 ,0
Exp/Cntr=0.3,0.1

Type RM Length L Ch R = 1 ,37262.8 ,475.5,494.7,508.5
XS GIS Cut Line= 3
     2115590.597      190361.186     2115924.204      190870.268
     2115900.668      191024.842
#Sta/Elev= 30
       0  2161.2   16.232161.273      36 2157.04    55.6 2154.76   101.4 2153.06
   124.4 2151.38     180  2150.5   245.4 2148.36     252 2147.59   265.1 2144.16
   327.2 2145.04     3362143.289   343.6 2142.63     3532143.247     360 2144.14
   382.9 2143.49   389.4 2144.71  398.862144.698  475.98 2144.84   497.4 2145.31
     517 2144.62   530.1 2147.97   539.9  2149.7   569.4 2151.03   582.5 2152.72
   605.4 2159.57   647.7 2177.22   670.5 2184.55   693.4 2190.06     765    2202
#Mann= 6 ,-1 , 0
       0    .016       0   16.23     .12       0     336    .045       0
     353     .12       0  398.86     .08       0  475.98     .12       0
#XS Ineff= 2 , 0
                          497.01          2147.8
Permanent Ineff=
       F       F
Bank Sta=336,353
XS Rating Curve= 0 ,0
Exp/Cntr=0.3,0.1

Type RM Length L Ch R = 1 ,36768.1 ,443.5,435.1,421.9
XS GIS Cut Line= 3
     2115471.382       190376.57     2115431.838      190885.436
     2115497.055      191023.294
#Sta/Elev= 30
       0 2160.54     6.5 2158.03   13.422154.598    16.4    2153    19.6  2152.3
    39.3  2151.8    42.5 2150.69    49.1 2147.32   55.072146.495      72 2145.69
   109.42145.073   248.7 2142.66   281.4  2141.4   350.1 2141.29   353.4 2141.18
   359.9 2139.89   379.5 2141.26  400.372141.276     409 2141.21   416.62139.594
   425.3 2139.28   433.72139.479   451.5 2141.01   454.8 2141.72   471.1  2150.4
     481 2154.82   516.9 2164.35   549.3 2174.13   604.5 2186.27   662.9  2196.9
#Mann= 7 ,-1 , 0
       0     .12       0   13.42    .016       0   55.07     .12       0
   109.4     .08       0  400.37     .12       0   416.6    .045       0
   433.7     .12       0
Bank Sta=416.6,433.7
XS Rating Curve= 0 ,0
Exp/Cntr=0.3,0.1

Type RM Length L Ch R = 1 ,36333   ,675.9,684.8,694.1
XS GIS Cut Line= 3
      2115010.57      190456.252     2115249.826      190890.103
     2115208.214      191085.309
#Sta/Elev= 30
       0 2169.16     9.8 2164.57    22.8 2157.56    35.8 2151.94   39.74 2149.65
    45.6 2146.23    65.2 2145.92    71.7 2144.57   75.94 2142.75    81.5 2141.37
  129.432139.603     238 2139.02   260.8 2136.94  275.462136.449   283.6 2136.32
  291.892136.431   309.7  2136.9   316.2 2138.23   329.2 2138.77   374.8 2138.07
   394.4 2138.76   410.7 2138.09   420.5 2139.44   430.3 2139.66  502.652146.203
   521.6  2148.8   570.7 2167.48  581.852172.216   665.6 2205.32     695 2215.32
#Mann= 8 ,-1 , 0
       0     .12       0   39.74    .016       0   75.94     .12       0
  129.43     .08       0  275.46    .045       0  291.89     .08       0
  502.65     .07       0  581.85     .12       0
#XS Ineff= 2 , 0
          207.75  2141.2
Permanent Ineff=
       F       F
Bank Sta=275.46,291.89
XS Rating Curve= 0 ,0
Exp/Cntr=0.3,0.1

Type RM Length L Ch R = 1 ,35648.2 ,22.9,33.6,34.6
XS GIS Cut Line= 3
     2114566.493      190722.277     2114820.399      191021.756
     2114803.038      191346.192
#Sta/Elev= 30
       0 2156.94    32.7 2148.72    62.2 2149.84    78.5 2153.78    94.9 2156.28
     108  2156.9   117.8 2156.36   130.9 2152.57   163.6 2136.04  202.842133.593
   261.8  2132.2  267.932132.723   278.1 2133.75  309.712133.339  320.332133.583
     337 2134.68   371.12134.875   379.5 2134.46  391.322132.504   408.9 2132.52
   421.9 2134.58   447.9 2133.31  451.782134.839   464.1 2143.52  487.282149.496
   503.1 2151.91   519.3 2156.38   610.3 2193.61   639.6  2204.8   717.5 2238.65
#Mann= 10 ,-1 , 0
       0     .12       0  202.84     .08       0  267.93    .016       0
  309.71     .08       0  320.33     .12       0   371.1    .016       0
  391.32    .045       0   408.9    .016       0  451.78     .07       0
  487.28     .12       0
#XS Ineff= 2 , 0
          358.31 2138.04  425.18         2137.03
Permanent Ineff=
       F       F
Bank Sta=391.32,408.9
XS Rating Curve= 0 ,0
Exp/Cntr=0.3,0.1

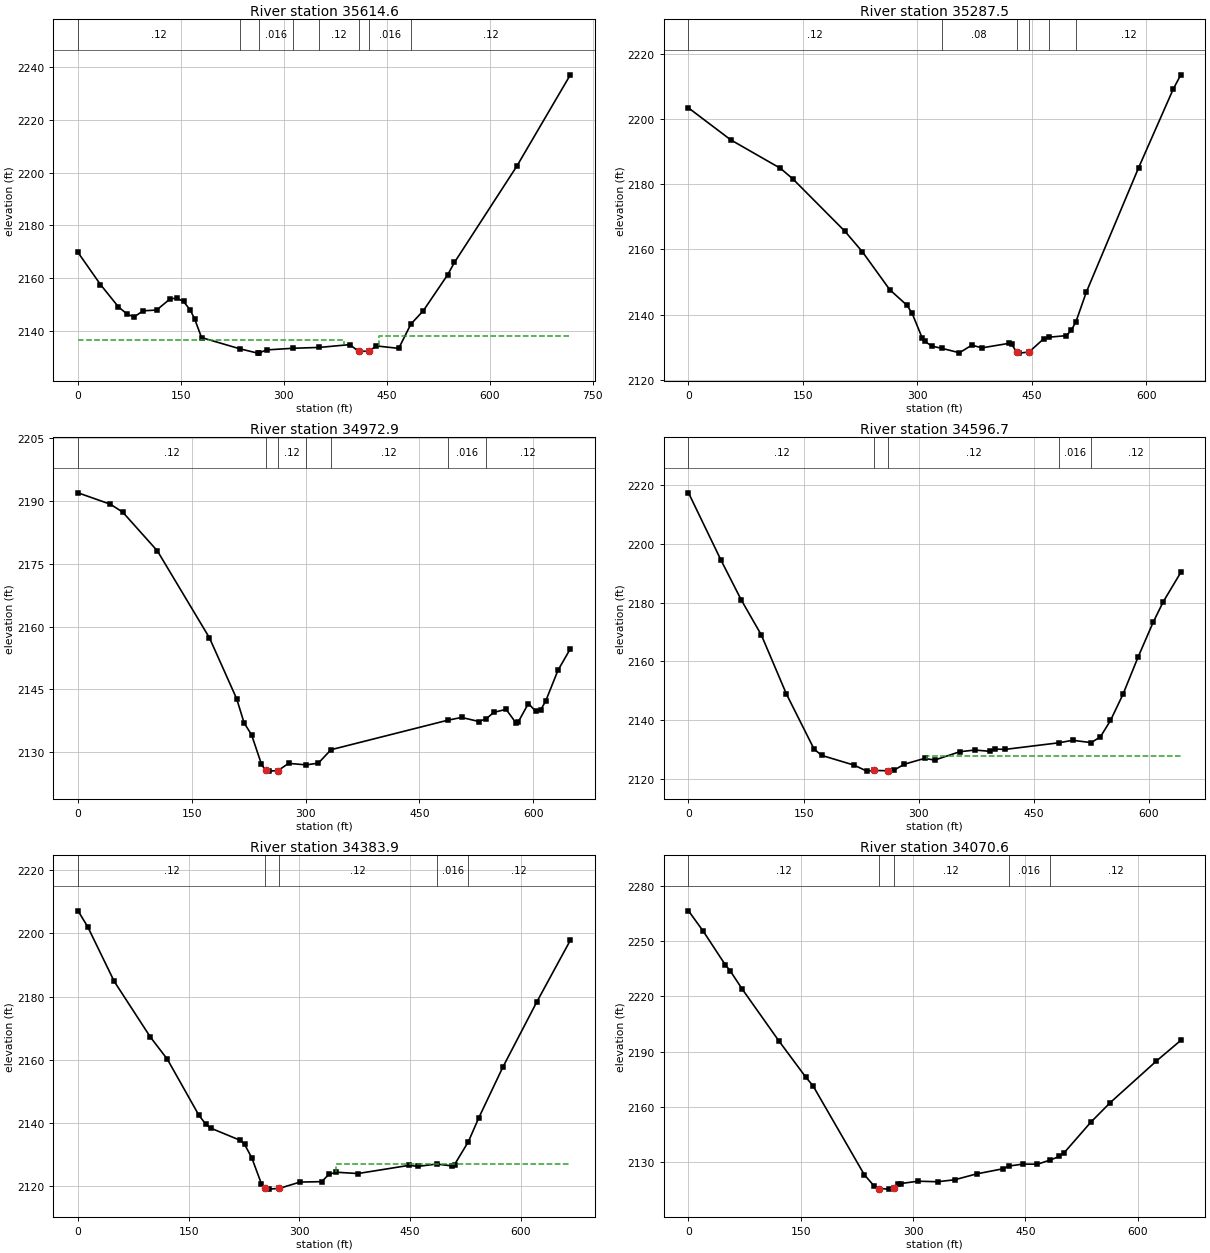
Type RM Length L Ch R = 1 ,35614.6 ,339.5,327.1,308.3
XS GIS Cut Line= 3
     2114539.366      190725.532     2114793.272      191025.011
     2114775.911      191349.447
#Sta/Elev= 30
       0 2169.66    32.7 2157.47    58.9 2148.98      72 2146.14    81.8 2145.18
    94.9 2147.49   114.5 2147.77   134.2 2152.02     144 2152.32   153.8 2151.04
   163.6 2147.76   170.1 2144.31     180 2137.31  235.892133.041   261.8  2131.4
  263.662131.441   274.8 2132.62  313.412133.248  351.75 2133.57   395.9 2134.63
   408.9  2132.1   424.12132.124   434.9 2134.13   467.4 2133.21  485.062142.427
   503.1 2147.47   538.8 2161.22   548.6 2165.88   639.6 2202.52   717.5 2237.21
#Mann= 8 ,-1 , 0
       0     .12       0  235.89     .08       0  263.66    .016       0
  313.41     .08       0  351.75     .12       0   408.9    .045       0
   424.1    .016       0  485.06     .12       0
#XS Ineff= 2 , 0
           387.2 2136.42  438.39         2137.84
Permanent Ineff=
       F       F
Bank Sta=408.9,424.1
XS Rating Curve= 0 ,0
Exp/Cntr=0.3,0.1

Type RM Length L Ch R = 1 ,35287.5 ,308.6,314.6,319.8
XS GIS Cut Line= 3
     2114435.437      190838.766     2114442.438      191102.451
     2114649.763      191422.453
#Sta/Elev= 30
       0 2203.38    55.4 2193.58   120.5 2184.86   136.8  2181.6   205.2 2165.51
     228 2159.24   263.8 2147.64   286.6 2142.82   293.1 2140.39   306.1 2132.93
   309.4 2131.85   319.2 2130.34  331.542129.721     355 2128.33   371.3 2130.67
   384.4 2129.83   420.2 2131.23   423.5 2130.89   430.1 2128.53   433.2 2128.22
   446.3 2128.56   465.8  2132.7  472.852133.113   495.2 2133.58   501.7 2135.26
  507.752137.868   521.2 2146.86   589.7 2184.98   635.3 2209.21   645.1 2213.52
#Mann= 6 ,-1 , 0
       0     .12       0  331.54     .08       0   430.1    .045       0
   446.3     .08       0  472.85    .016       0  507.75     .12       0
Bank Sta=430.1,446.3
XS Rating Curve= 0 ,0
Exp/Cntr=0.3,0.1

Type RM Length L Ch R = 1 ,34972.9 ,388.5,376.2,363.1
XS GIS Cut Line= 3
     2114206.915      191013.641     2114288.791      191254.961
     2114417.354      191627.504
#Sta/Elev= 30
       0 2191.85    42.5 2189.14    58.8 2187.27   104.6 2178.01   173.2 2157.31
   209.1 2142.79   218.9 2137.03   228.7 2134.22   241.8 2127.19  247.142125.729
   251.6 2125.55   263.62125.684   277.6  2127.4  300.432127.042   316.7 2127.44
  333.42 2130.65  487.212137.674   505.6 2138.34   528.4 2137.37  538.282138.056
     548 2139.55   564.2 2140.27   577.3 2137.03   580.5 2137.34   593.6 2141.66
   603.3  2139.8   609.8 2140.14   616.4 2142.23   632.6 2149.57   648.9 2154.69
#Mann= 7 ,-1 , 0
       0     .12       0  247.14    .045       0   263.6     .12       0
  300.43     .08       0  333.42     .12       0  487.21    .016       0
  538.28     .12       0
Bank Sta=247.14,263.6
XS Rating Curve= 0 ,0
Exp/Cntr=0.3,0.1

Type RM Length L Ch R = 1 ,34596.7 ,217.3,212.8,208.2
XS GIS Cut Line= 2
     2113835.452      191346.323     2114333.581      191750.372
#Sta/Elev= 30
       0 2217.25    42.5  2194.3    68.7 2180.91    94.9 2168.99   127.6 2148.94
   163.6 2130.25   173.4 2128.12     216 2124.78   232.3 2122.77   242.32122.989
   259.82122.916   268.3  2123.2   281.4 2125.13   307.6 2127.09   320.7 2126.52
   353.4 2129.35   373.1 2129.93   392.7  2129.5   399.2 2130.27   412.3 2130.14
  482.54 2132.39   500.7 2133.24  524.662132.439   536.7 2134.42   549.8 2139.96
   566.1 2148.86   585.8 2161.53   605.4  2173.3   618.5 2180.26   641.4 2190.23
#Mann= 5 ,-1 , 0
       0     .12       0   242.3    .045       0   259.8     .12       0
  482.54    .016       0  524.66     .12       0
#XS Ineff= 2 , 0
                          311.21         2128.06
Permanent Ineff=
       F       F
Bank Sta=242.3,259.8
XS Rating Curve= 0 ,0
Exp/Cntr=0.3,0.1

Type RM Length L Ch R = 1 ,34383.9 ,318.4,313.3,307.6
XS GIS Cut Line= 3
     2113648.356      191659.181     2113833.397       191636.82
     2114260.426      191857.335
#Sta/Elev= 30
       0 2207.11    13.1 2202.07      49 2184.81    98.1 2167.16     121 2160.18
   163.5 2142.57   173.3 2139.55   179.8 2138.39   219.1  2134.6   225.6 2133.29
   235.4    2129   248.5 2120.76  253.69 2119.37   258.3  2119.1   272.92119.341
   300.8 2121.34   330.2 2121.46     340  2123.8   349.9 2124.44   379.3 2124.03
   447.9  2126.6     461 2126.31  485.882127.032   506.8 2126.44   510.1 2126.85
  528.842134.101   542.8 2141.57   575.4  2157.6   621.2 2178.14     667  2197.8
#Mann= 5 ,-1 , 0
       0     .12       0  253.69    .045       0   272.9     .12       0
  485.88    .016       0  528.84     .12       0
#XS Ineff= 2 , 0
                          348.92         2127.16
Permanent Ineff=
       F       F
Bank Sta=253.69,272.9
XS Rating Curve= 0 ,0
Exp/Cntr=0.3,0.1

Type RM Length L Ch R = 1 ,34070.6 ,335.3,347.7,357.6
XS GIS Cut Line= 3
     2113524.356      191894.313     2113943.071      191993.844
     2113989.651      192216.098
#Sta/Elev= 30
       0 2266.51    19.6 2255.49    48.9 2237.35    55.4  2234.1    71.7 2224.04
   120.6 2195.93   156.5 2176.27   166.3 2171.49   234.8 2123.23   247.8 2117.13
   254.72115.707   267.4 2115.39   273.9 2115.78   280.4 2118.09   283.7 2118.43
   306.5 2119.69   332.6  2119.4   355.4 2120.46   384.7 2123.65   420.6 2126.49
  427.64  2127.9   446.6 2128.98   466.1 2128.92  483.082131.203   495.3 2133.13
   501.8 2135.18   537.4 2151.76   563.4 2162.42     625 2184.98   657.5 2196.16
#Mann= 5 ,-1 , 0
       0     .12       0   254.7    .045       0   273.9     .12       0
  427.64    .016       0  483.08     .12       0
#XS Ineff= 2 , 0
                          368.42         2099.46
Permanent Ineff=
       F       F
Bank Sta=254.7,273.9
XS Rating Curve= 0 ,0
Exp/Cntr=0.3,0.1

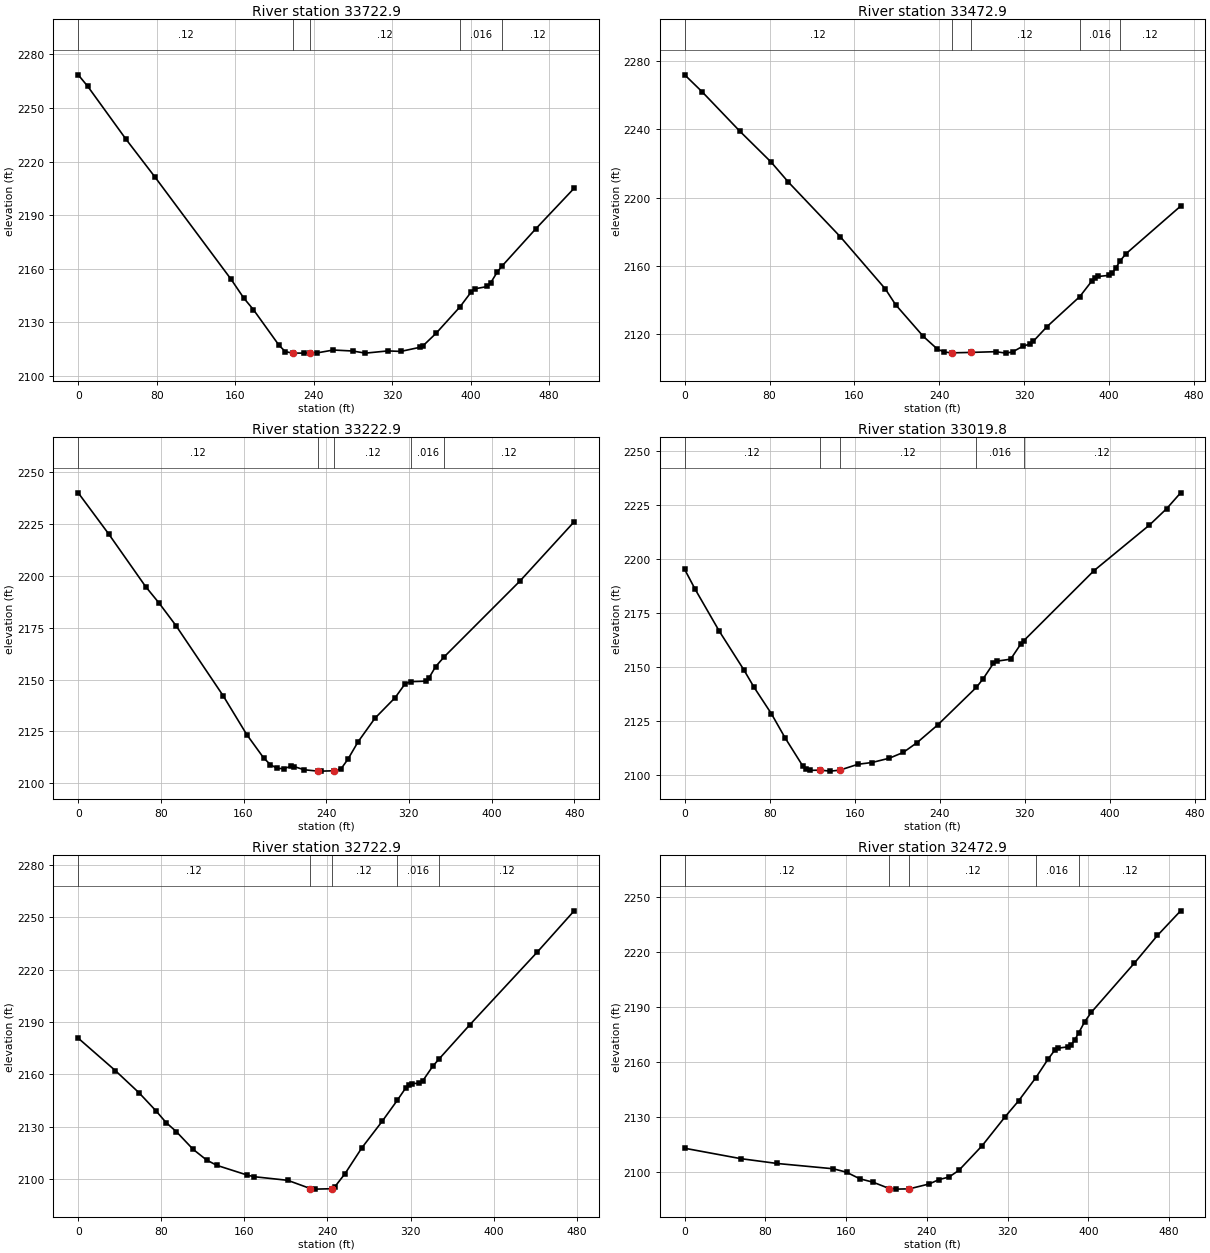
Type RM Length L Ch R = 1 ,33722.9 ,239.3,250,261.8
XS GIS Cut Line= 3
     2113403.002      192069.772     2113583.392      192208.178
     2113804.666      192376.799
#Sta/Elev= 30
       0 2268.53     9.7 2262.09    48.7 2232.48      78 2211.49   155.9 2154.01
   168.9 2143.46   178.6 2137.08   204.6  2117.2   211.1 2113.56   218.52112.752
   230.6 2112.72   236.22112.777   243.7 2112.87   260.1 2114.46   279.7 2113.91
   292.8 2112.72   315.7 2113.96   328.8 2113.67   348.5 2115.99   351.7 2116.92
   364.8  2123.8  389.242138.639   400.8 2147.09   404.1 2148.69   417.2 2150.03
   420.5 2152.07     427 2157.95  431.832161.322   466.3 2182.21   505.6 2205.04
#Mann= 5 ,-1 , 0
       0     .12       0   218.5    .045       0   236.2     .12       0
  389.24    .016       0  431.83     .12       0
Bank Sta=218.5,236.2
XS Rating Curve= 0 ,0
Exp/Cntr=0.3,0.1

Type RM Length L Ch R = 1 ,33472.9 ,239.4,250,255.2
XS GIS Cut Line= 3
     2113290.082      192135.185     2113405.898      192368.859
     2113484.091      192560.236
#Sta/Elev= 30
       0 2271.93    16.3 2262.07    52.2 2238.75    81.5 2220.76    97.8 2209.01
   146.7 2177.02   189.1 2146.45   198.9 2137.12   224.9 2118.63     238 2111.26
   244.5 2109.44   251.92108.956   269.72109.201   293.1 2109.64   302.8 2108.79
   309.2 2109.52   318.9  2112.9   325.4 2114.07   328.6 2115.72   341.6 2124.35
  372.452141.937   383.6 2150.89   386.8 2152.83     390 2153.74   399.7 2154.36
   402.9 2155.63   406.2 2158.46  410.372162.754   415.8 2166.94   467.5 2194.97
#Mann= 5 ,-1 , 0
       0     .12       0   251.9    .045       0   269.7     .12       0
  372.45    .016       0  410.37     .12       0
Bank Sta=251.9,269.7
XS Rating Curve= 0 ,0
Exp/Cntr=0.3,0.1

Type RM Length L Ch R = 1 ,33222.9 ,212.9,203.1,195.5
XS GIS Cut Line= 3
       2113166.6      192178.767     2113165.073       192413.64
      2113199.12      192656.254
#Sta/Elev= 30
       0 2240.17    29.4 2220.37    65.2 2194.91    78.3  2186.9    94.6 2176.04
   140.3 2142.15   163.1 2123.42   179.4 2112.18   185.9 2108.94   192.5 2107.09
     199    2107   205.5 2108.04   208.8    2108   218.6 2106.45   231.6 2105.79
   234.9 2105.78   247.9 2105.95   254.5 2107.01     261 2111.54   270.8 2119.94
   287.1  2131.3   306.7 2141.28   316.5 2148.08  322.362148.983   336.1 2149.22
   339.4 2150.77   345.9 2156.28  354.232161.018   427.6 2197.65   479.9 2226.18
#Mann= 5 ,-1 , 0
       0     .12       0   231.6    .045       0   247.9     .12       0
  322.36    .016       0  354.23     .12       0
Bank Sta=231.6,247.9
XS Rating Curve= 0 ,0
Exp/Cntr=0.3,0.1

Type RM Length L Ch R = 1 ,33019.8 ,304.5,296.9,288.8
XS GIS Cut Line= 2
     2112914.945       192275.04     2113116.748        192695.7
#Sta/Elev= 30
       0 2195.12     9.8 2186.01    32.6 2166.57    55.5 2148.89    65.2 2140.75
    81.6 2128.47    94.6 2117.24   110.9 2104.52   114.2 2102.88   117.5 2102.32
   127.2 2102.44     137 2101.98   145.82102.417   163.1 2105.15   176.2 2105.96
   192.5 2107.94   205.6 2110.61   218.6 2115.12   238.2 2123.37  274.43 2140.67
   280.6 2144.47   290.4 2151.69   293.6 2152.75   306.7 2153.68   316.5 2160.88
   318.9 2162.14     385 2194.51   437.2 2215.58   453.5  2223.2   466.6 2230.49
#Mann= 5 ,-1 , 0
       0     .12       0   127.2    .045       0   145.8     .12       0
  274.43    .016       0   318.9     .12       0
Bank Sta=127.2,145.8
XS Rating Curve= 0 ,0
Exp/Cntr=0.3,0.1

Type RM Length L Ch R = 1 ,32722.9 ,246.3,250,249.9
XS GIS Cut Line= 3
     2112644.552      192470.386     2112806.469      192635.194
     2112981.886      192808.451
#Sta/Elev= 30
       0  2180.8    35.8  2162.2    58.6  2149.5    74.8 2139.24    84.6 2132.49
    94.4 2127.33   110.6 2117.17   123.6 2111.04   133.4 2107.99   162.7 2102.41
   169.2 2101.48   201.8 2099.39   223.42094.709   227.8 2094.35     244 2094.57
   247.3 2095.82     257 2103.25   273.2 2118.04   292.7 2133.17  307.152145.108
   315.4 2152.29   318.6  2154.2   321.9  2154.8   328.4    2155   331.6 2156.19
   341.3  2164.6  347.262168.713     377 2188.38   441.9 2229.97   477.6 2253.71
#Mann= 5 ,-1 , 0
       0     .12       0   223.4    .045       0     244     .12       0
  307.15    .016       0  347.26     .12       0
Bank Sta=223.4,244
XS Rating Curve= 0 ,0
Exp/Cntr=0.3,0.1

Type RM Length L Ch R = 1 ,32472.9 ,257.2,250,244.5
XS GIS Cut Line= 3
     2112490.717      192621.249     2112612.721      192791.505
     2112810.383      192992.531
#Sta/Elev= 30
       0 2112.89    55.6 2107.22    91.6 2104.59   147.3  2101.7   160.4 2099.82
   173.5 2096.25   186.6  2094.4   202.9  2090.9   209.5 2090.61   222.6 2090.77
   242.2 2093.42   252.1 2095.83   261.9 2097.19   271.7 2100.86   294.7 2114.25
   317.6 2130.11   330.8 2138.69  347.962151.378   360.2 2161.58   366.8 2166.43
   370.1 2167.45   379.9 2168.18   383.2 2169.44   386.5  2171.9  390.542175.924
   396.3 2181.82   402.9 2186.98   445.5 2213.76   468.4 2228.87   491.4 2242.31
#Mann= 5 ,-1 , 0
       0     .12       0   202.9    .045       0   222.6     .12       0
  347.96    .016       0  390.54     .12       0
Bank Sta=202.9,222.6
XS Rating Curve= 0 ,0
Exp/Cntr=0.3,0.1

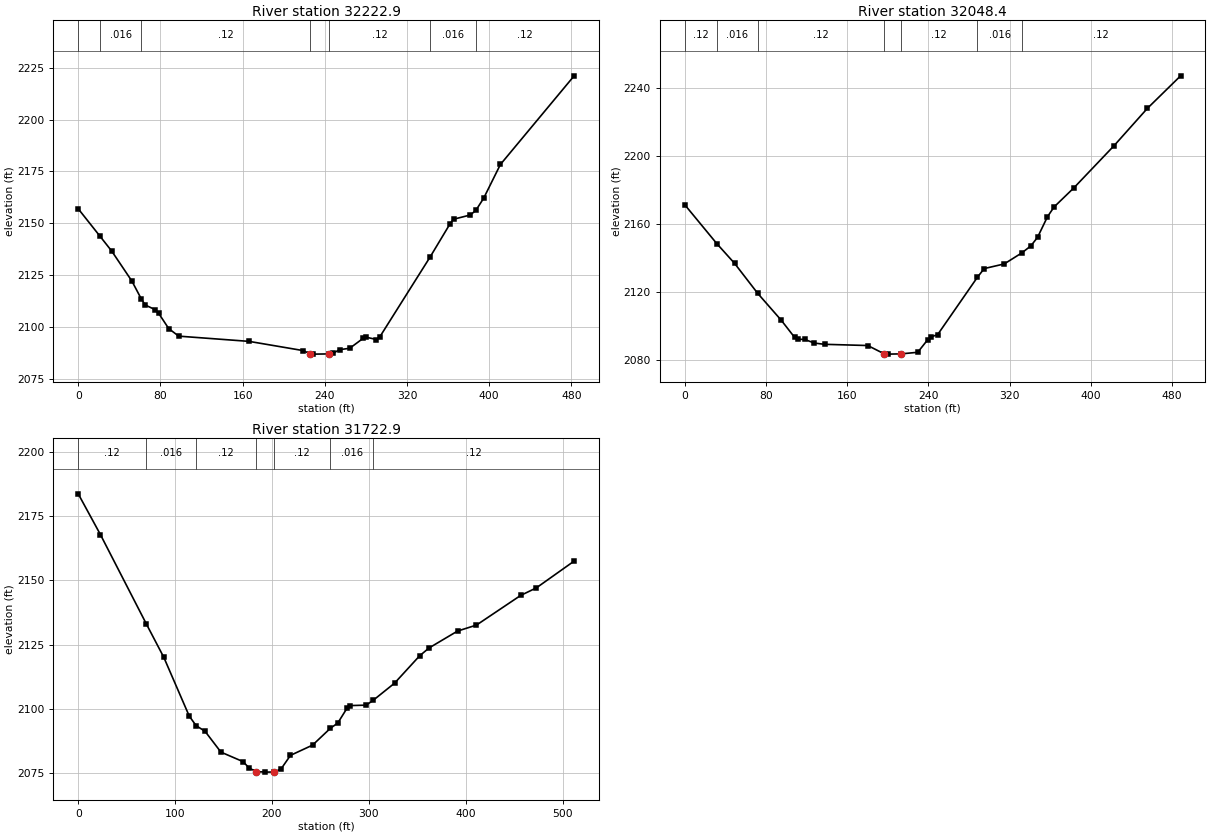
Type RM Length L Ch R = 1 ,32222.9 ,175.9,174.5,174.1
XS GIS Cut Line= 3
     2112283.853      192858.854     2112475.341       192994.76
     2112684.711      193127.419
#Sta/Elev= 30
       0 2157.04   20.952143.973    32.6 2136.67    52.2 2122.25   61.462113.577
    65.2  2110.7      75 2108.43    78.3 2106.69    88.1 2099.34    97.8  2095.7
   166.3 2093.18   218.5 2088.78   225.82087.273   228.3 2087.04   243.82087.136
   247.9 2087.41   254.4  2089.2   264.2 2089.84   277.2  2094.6   280.5 2095.16
   290.3 2094.08   293.5 2095.32  342.492133.801     362 2149.88   365.3    2152
   381.6 2154.04  386.992156.244   394.6 2162.09   410.9 2178.36   482.7 2221.06
#Mann= 7 ,-1 , 0
       0     .12       0   20.95    .016       0   61.46     .12       0
   225.8    .045       0   243.8     .12       0  342.49    .016       0
  386.99     .12       0
Bank Sta=225.8,243.8
XS Rating Curve= 0 ,0
Exp/Cntr=0.3,0.1

Type RM Length L Ch R = 1 ,32048.4 ,322,325.5,325.2
XS GIS Cut Line= 2
     2112185.851      193007.477     2112600.117      193266.195
#Sta/Elev= 30
       0 2171.19   31.622148.305    49.2 2136.65   71.972119.033    95.1 2103.28
   108.2 2093.25   111.4  2092.1     118 2092.03   127.8 2089.86   137.7 2089.14
   180.3 2088.42   196.7 2083.49     200 2083.37   213.1 2083.52   229.5 2084.45
   239.3 2091.82   242.6 2093.51   249.1 2094.82  288.252128.512     295 2133.64
   314.7 2136.36  332.122142.883   340.9 2146.96   347.5 2151.98   357.3 2164.12
   363.8 2169.84   383.5 2181.19   422.9 2205.87   455.6 2227.72   488.4 2246.88
#Mann= 7 ,-1 , 0
       0     .12       0   31.62    .016       0   71.97     .12       0
   196.7    .045       0   213.1     .12       0  288.25    .016       0
  332.12     .12       0
Bank Sta=196.7,213.1
XS Rating Curve= 0 ,0
Exp/Cntr=0.3,0.1

Type RM Length L Ch R = 1 ,31722.9 ,256.9,250,249.9
XS GIS Cut Line= 3
     2112022.345      193255.437     2112170.365      193379.441
     2112441.446      193547.245
#Sta/Elev= 30
       0 2183.57    22.9 2167.74   70.482132.886    88.4 2119.98   114.6 2097.19
  121.682093.464   130.9 2091.28   147.3 2083.18   170.2 2079.47   176.7 2076.89
     184 2075.63   193.1  2075.4   202.22075.456   209.4 2076.65   219.1 2081.92
   241.9  2085.9  260.262092.431   267.9 2094.48   277.7 2100.39   280.9 2101.27
   297.2 2101.43  304.222103.242   326.5 2109.97   352.5 2120.65   362.3  2123.7
   391.5 2130.22   411.1 2132.56   456.6 2144.06   472.9 2147.02   511.9 2157.43
#Mann= 7 ,-1 , 0
       0     .12       0   70.48    .016       0  121.68     .12       0
     184    .045       0   202.2     .12       0  260.26    .016       0
  304.22     .12       0
Bank Sta=184,202.2
XS Rating Curve= 0 ,0
Exp/Cntr=0.3,0.1