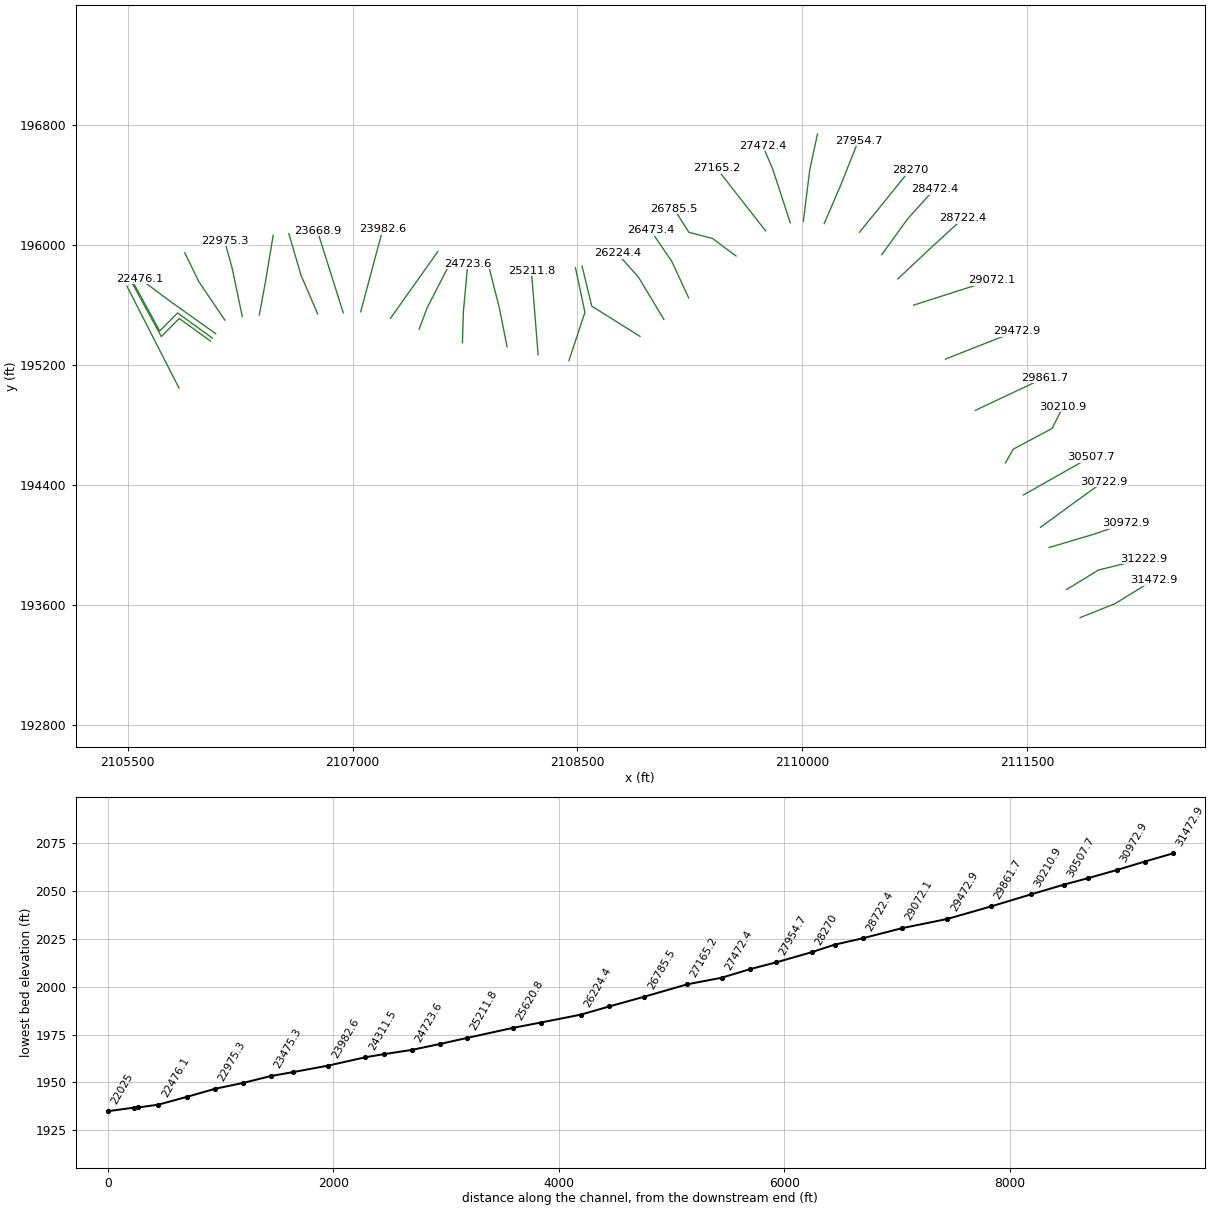
HEC-RAS study TRKYCK.prj: TRKYCK

--- TRKYCK.g01 (geometry) --- (continued)

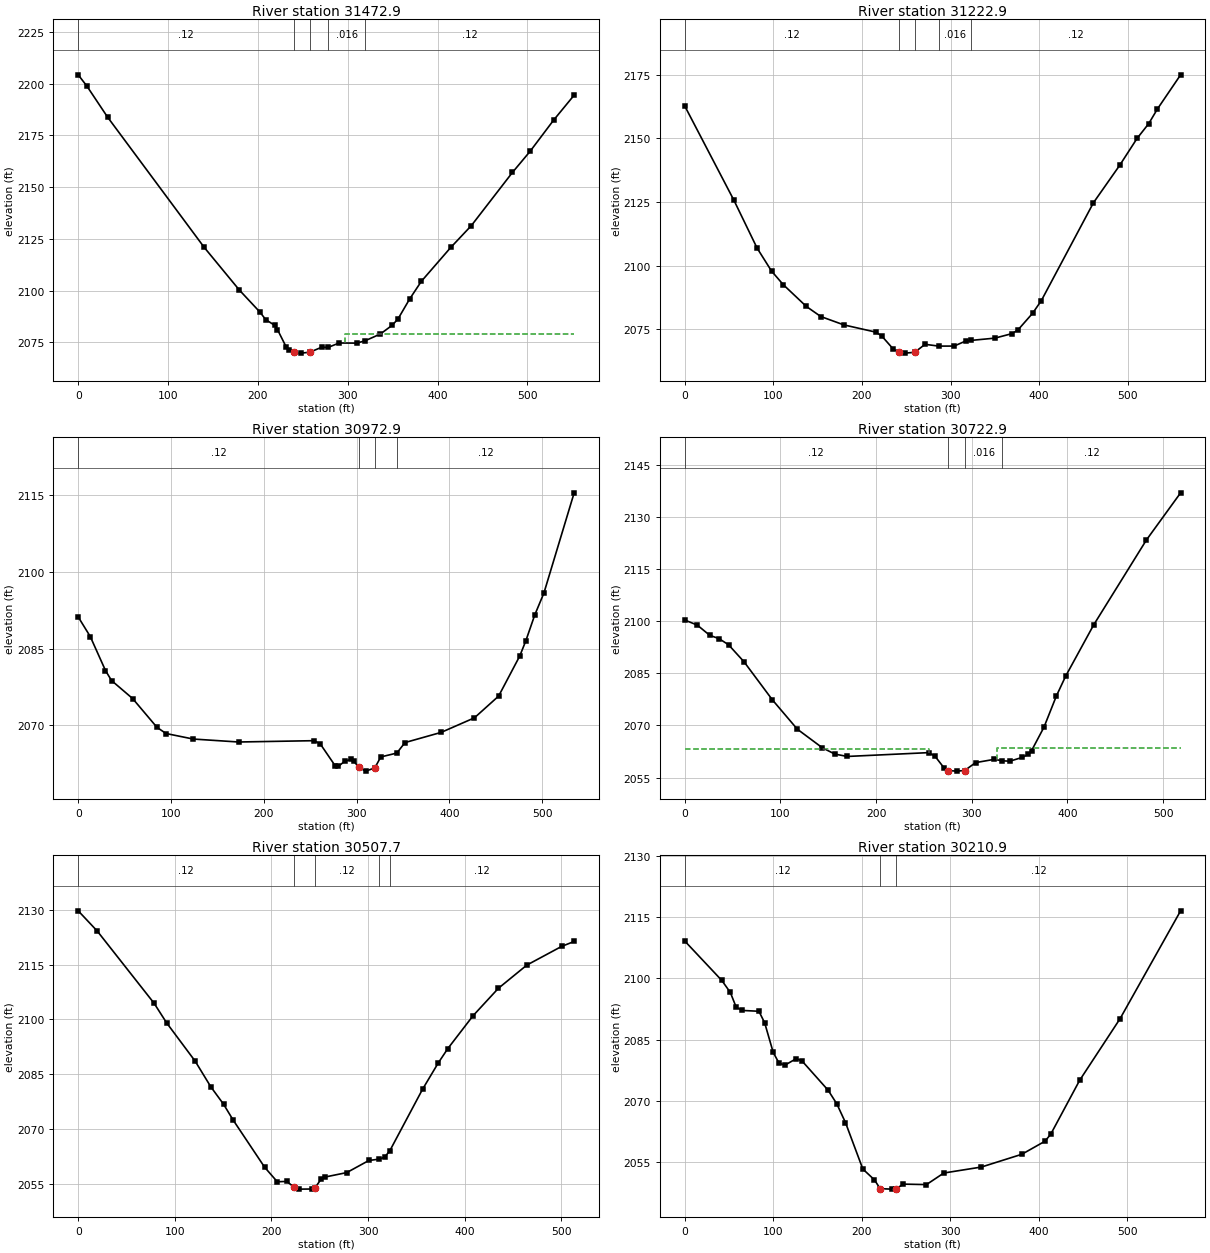
Type RM Length L Ch R = 1 ,31472.9 ,246.1,250,243
XS GIS Cut Line= 3
     2111851.951      193513.845     2112085.064      193607.242
     2112341.319      193764.854
#Sta/Elev= 30
       0 2204.29     9.8 2198.75    32.6  2183.9   140.2 2120.92   179.4 2100.25
   202.2 2089.66   208.7 2085.98   218.5 2083.28   221.8 2081.15   231.6 2072.67
   234.8 2071.17  239.942070.201   247.9 2069.79   257.7 2070.21   270.8 2072.62
  278.232072.569   290.4 2074.69     310 2074.62  319.442075.788   336.2    2079
   349.2 2083.17   355.8 2086.21   368.8 2095.88   381.9 2104.48   414.6 2120.84
   437.5 2131.38   483.3 2157.11   502.9 2167.28   529.1 2182.37     552 2194.47
#Mann= 5 ,-1 , 0
       0     .12       0  239.94    .045       0   257.7     .12       0
  278.23    .016       0  319.44     .12       0
#XS Ineff= 2 , 0
                          297.21         2079.19
Permanent Ineff=
       F       F
Bank Sta=239.94,257.7
XS Rating Curve= 0 ,0
Exp/Cntr=0.3,0.1

Type RM Length L Ch R = 1 ,31222.9 ,256,250,251.8
XS GIS Cut Line= 3
     2111762.517      193701.703     2111974.442      193831.137
     2112276.629      193905.447
#Sta/Elev= 30
       0 2162.85    55.6 2125.65    81.7 2106.85      98 2097.81   111.1  2092.5
   137.2  2083.9   153.6 2079.91   179.7 2076.61   215.6 2073.78   222.2  2072.3
   235.3 2067.12   241.8 2065.82   248.3 2065.51  259.442065.819   271.2 2068.98
   286.62068.273     304 2068.29   317.1 2070.29  322.782070.509   349.9 2071.41
   369.5 2073.21   376.1 2074.69   392.4 2081.15   402.3 2086.14   461.2 2124.73
   490.7 2139.41   510.4 2150.05   523.5 2155.84   533.3  2161.6   559.5 2175.06
#Mann= 5 ,-1 , 0
       0     .12       0   241.8    .045       0  259.44     .12       0
   286.6    .016       0  322.78     .12       0
Bank Sta=241.8,259.44
XS Rating Curve= 0 ,0
Exp/Cntr=0.3,0.1

Type RM Length L Ch R = 1 ,30972.9 ,242,250,256.3
XS GIS Cut Line= 3
     2111644.872       193980.86      2111944.93      194070.211
     2112154.251      194142.272
#Sta/Elev= 30
       0 2091.17      13 2087.34    29.4  2080.7    35.9 2078.75    58.7 2075.22
    84.8 2069.62    94.6  2068.4   123.9 2067.32   172.8 2066.74   254.4    2067
   260.9 2066.36   277.2 2062.03   280.5    2062     287 2062.95   293.5 2063.33
   296.8 2063.07  302.312061.781   309.8 2061.05   319.6 2061.67   326.1 2063.82
  343.352064.576   352.2 2066.63   391.2 2068.62     427 2071.46   453.1 2075.71
   475.9 2083.55   482.4  2086.5   492.1 2091.59   501.9 2095.84   534.5 2115.42
#Mann= 4 ,-1 , 0
       0     .12       0  302.31    .045       0   319.6    .016       0
  343.35     .12       0
Bank Sta=302.31,319.6
XS Rating Curve= 0 ,0
Exp/Cntr=0.3,0.1

Type RM Length L Ch R = 1 ,30722.9 ,217.8,215.2,212.5
XS GIS Cut Line= 3
     2111587.968      194115.887     2111817.698      194283.684
     2112007.461      194420.152
#Sta/Elev= 30
       0 2100.33    13.1 2098.88    26.2 2095.93      36 2094.96    45.8 2093.22
    62.1 2088.29    91.6 2077.39   117.7 2068.94   143.9 2063.58     157 2061.77
     170  2061.1   255.1  2062.2   261.6 2061.16   271.4 2057.66   274.7 2057.04
   284.5 2056.88  292.572057.059     304 2059.33   323.4 2060.26  331.962059.853
   339.7 2059.73   352.7 2060.83   359.2 2061.71   362.4 2062.74   375.4  2069.5
   388.4  2078.5   398.1  2084.2   427.3  2098.9   482.5 2123.36   518.2  2136.9
#Mann= 4 ,-1 , 0
       0     .12       0   274.7    .045       0  292.57    .016       0
  331.96     .12       0
#XS Ineff= 2 , 0
          255.02 2063.32   325.9         2063.49
Permanent Ineff=
       F       F
Bank Sta=274.7,292.57
XS Rating Curve= 0 ,0
Exp/Cntr=0.3,0.1

Type RM Length L Ch R = 1 ,30507.7 ,297.2,296.8,296.4
XS GIS Cut Line= 2
     2111474.038       194331.55     2111921.029      194583.773
#Sta/Elev= 30
       0 2129.71    19.6  2124.2    78.5  2104.4    91.5 2099.02     121 2088.54
   137.3 2081.47   150.4 2076.74   160.2 2072.45   192.9 2059.48     206  2055.5
   215.8 2055.59   223.8 2053.93   228.8 2053.48   241.9 2053.51   245.2 2053.88
   251.7 2056.37     255 2056.77   277.9 2058.01   300.8 2061.33  311.772061.701
   317.1 2062.25  322.392063.961   356.3 2080.83   372.7  2088.1   382.5 2091.99
   408.6 2100.98   434.8 2108.49   464.2 2114.84   500.2 2119.96   513.2 2121.32
#Mann= 5 ,-1 , 0
       0     .12       0   223.8    .045       0   245.2     .12       0
  311.77    .016       0  322.39     .12       0
Bank Sta=223.8,245.2
XS Rating Curve= 0 ,0
Exp/Cntr=0.3,0.1

Type RM Length L Ch R = 1 ,30210.9 ,350.3,349.2,348
XS GIS Cut Line= 4
     2111354.176      194545.793     2111404.999       194635.69
     2111664.344      194774.411     2111738.659      194919.536
#Sta/Elev= 30
       0 2109.18      42 2099.48    51.6 2096.54    58.1 2092.98    64.5 2092.14
    83.9 2091.93    90.4 2089.09     100 2081.86   106.5 2079.25   113.1 2078.69
   126.1 2080.31   132.7 2079.72   162.1 2072.56   171.9 2069.22   181.7 2064.63
   201.3 2053.23   214.4 2050.58   220.9 2048.41     234  2048.3  239.252048.432
   247.1 2049.53   273.2 2049.41   292.8 2052.25   335.3 2053.72     381 2056.85
   407.2 2060.06   413.7  2061.8   446.3 2074.99     492 2090.12   560.4 2116.57
#Mann= 3 ,-1 , 0
       0     .12       0   220.9    .045       0  239.25     .12       0
Bank Sta=220.9,239.25
XS Rating Curve= 0 ,0
Exp/Cntr=0.3,0.1

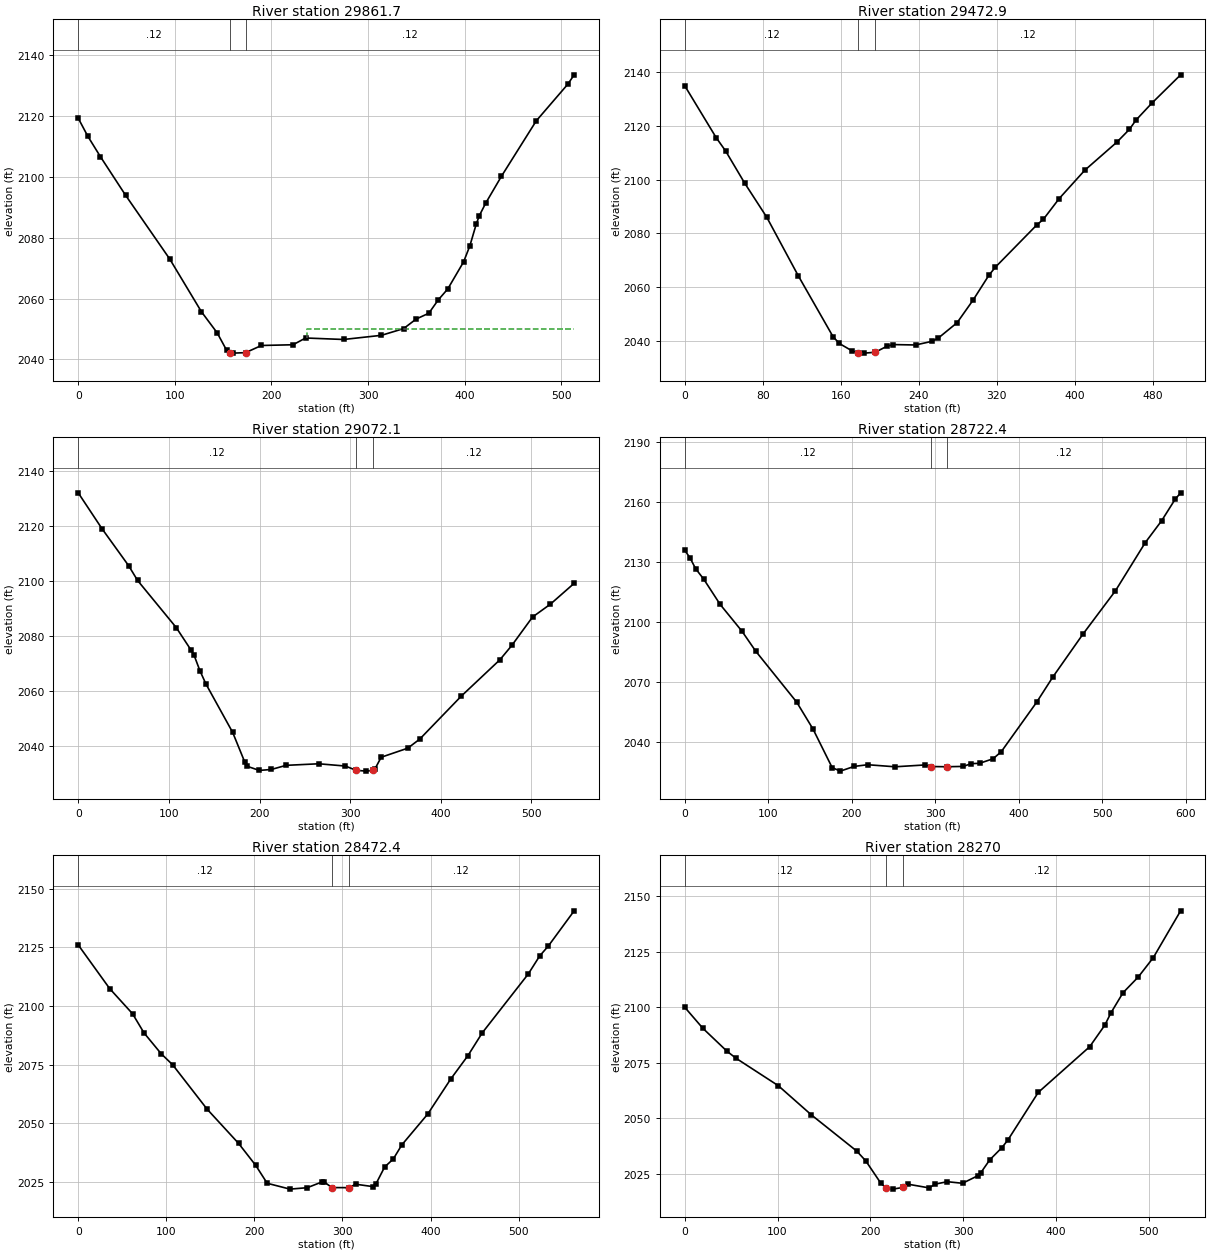
Type RM Length L Ch R = 1 ,29861.7 ,389.7,388.8,386.8
XS GIS Cut Line= 2
       2111153.2      194895.057     2111617.387      195113.862
#Sta/Elev= 30
       0 2119.25     9.8 2113.38    22.9 2106.64      49 2093.94    94.8 2072.95
   127.5 2055.68   143.8 2048.75   153.6 2043.01   156.72042.277   160.2 2042.09
   173.2 2042.25   189.6  2044.6   222.3 2044.84   235.3 2047.06   274.6 2046.57
   313.8 2047.94   336.7 2050.14   349.7 2053.28   362.8 2055.19   372.6 2059.58
   382.4 2063.16   398.8 2072.06   405.3 2077.35   411.8 2084.38   415.1 2087.25
   421.6  2091.3     438 2100.19     474 2118.37   506.6 2130.39   513.2 2133.48
#Mann= 3 ,-1 , 0
       0     .12       0   156.7    .045       0   173.2     .12       0
#XS Ineff= 2 , 0
                          236.53         2049.97
Permanent Ineff=
       F       F
Bank Sta=156.7,173.2
XS Rating Curve= 0 ,0
Exp/Cntr=0.3,0.1

Type RM Length L Ch R = 1 ,29472.9 ,402.4,400.8,399.4
XS GIS Cut Line= 3
     2110954.087      195236.647     2111125.458      195304.399
     2111426.764      195423.519
#Sta/Elev= 30
       0 2134.98    32.3 2115.63      42 2110.66    61.4 2098.78    84.1 2086.06
   116.4 2064.29     152 2041.67   158.4 2039.12   171.4 2036.38   177.8 2035.62
   184.3 2035.51  195.272035.834   207.2 2038.05   213.7 2038.69   236.6 2038.54
     253 2039.86   259.6 2041.01   279.2 2046.82   295.6 2055.24   311.9 2064.52
   318.5 2067.49     361 2083.22   367.6 2085.26   383.9 2093.01   410.1 2103.53
   442.8 2113.91   455.9 2118.75   462.5 2122.15   478.8 2128.46   508.3    2139
#Mann= 3 ,-1 , 0
       0     .12       0   177.8    .045       0  195.27     .12       0
Bank Sta=177.8,195.27
XS Rating Curve= 0 ,0
Exp/Cntr=0.3,0.1

Type RM Length L Ch R = 1 ,29072.1 ,339,349.7,358.8
XS GIS Cut Line= 2
     2110741.992      195596.372     2111263.035      195763.261
#Sta/Elev= 30
       0 2132.22    26.2 2119.15    55.7 2105.61    65.5 2100.25   108.1 2083.09
   124.5 2074.85   127.8 2072.99   134.3  2067.3   140.9 2062.49   170.4 2044.83
   183.5  2034.2   186.7 2032.44   199.8 2030.97     213 2031.31   229.3 2032.82
   265.4 2033.39   294.8 2032.56  306.562031.004   317.8 2030.71  324.962030.988
   327.6 2031.66   334.2 2035.77   363.6 2039.09   376.8  2042.4   422.6 2058.07
   465.2 2071.33   478.3 2076.54   501.2 2086.92   520.9 2091.61   547.1 2099.21
#Mann= 3 ,-1 , 0
       0     .12       0  306.56    .045       0  324.96     .12       0
Bank Sta=306.56,324.96
XS Rating Curve= 0 ,0
Exp/Cntr=0.3,0.1

Type RM Length L Ch R = 1 ,28722.4 ,245.1,250,251.5
XS GIS Cut Line= 3
     2110636.063       195770.98     2110858.059      195978.901
     2111071.374       196174.77
#Sta/Elev= 30
       0 2135.84     6.5 2131.85    13.1 2126.55    22.9 2121.26    42.5 2108.67
    68.7 2095.25      85 2085.36   134.1 2059.87   153.7 2046.38   176.6 2027.14
   186.4 2025.39   202.8 2027.74   219.1 2028.59   251.8 2027.56   287.8 2028.48
   294.72027.685   313.62027.586   333.4 2027.74   343.2 2029.13     353 2029.29
   369.2 2031.56     379 2035.07   421.3 2059.74   440.8 2072.42   476.6  2093.7
   515.7 2115.46   551.5 2139.59     571 2150.46   587.2  2161.2   593.8 2164.45
#Mann= 3 ,-1 , 0
       0     .12       0   294.7    .045       0   313.6     .12       0
Bank Sta=294.7,313.6
XS Rating Curve= 0 ,0
Exp/Cntr=0.3,0.1

Type RM Length L Ch R = 1 ,28472.4 ,203.8,202.4,203.5
XS GIS Cut Line= 3
     2110528.812      195931.907     2110702.019      196171.555
     2110881.228      196369.965
#Sta/Elev= 30
       0 2126.04    35.7 2107.45    61.7 2096.72    74.7 2088.57    94.2 2079.69
   107.2    2075   146.2 2056.15     182 2041.54   201.5 2032.16   214.5 2024.54
   240.4 2022.04     260 2022.65   276.2 2025.02   279.4 2025.05  287.97  2022.7
  306.932022.666   315.2 2024.12   334.8  2023.1   338.1 2024.34   347.9 2031.49
   357.6 2034.83   367.4 2040.89   396.8 2054.02   422.8 2068.88   442.4 2078.88
   458.7 2088.61   510.9 2113.66   523.9 2121.36   533.7 2125.58     563 2140.56
#Mann= 3 ,-1 , 0
       0     .12       0  287.97    .045       0  306.93     .12       0
Bank Sta=287.97,306.93
XS Rating Curve= 0 ,0
Exp/Cntr=0.3,0.1

Type RM Length L Ch R = 1 ,28270   ,308.8,315.3,322.1
XS GIS Cut Line= 3
      2110380.51      196082.071     2110534.568      196270.961
     2110716.797      196496.969
#Sta/Elev= 30
       0 2099.96    19.5  2090.5    45.5 2080.17    55.2 2077.02   100.8 2064.66
   136.5  2051.5   185.2 2035.28     195 2030.85   211.2 2020.82  216.312018.837
   224.2 2018.13  234.692018.868   240.5 2020.35   263.3 2018.68   269.8  2020.4
   282.9 2021.47   299.2 2020.76   315.5 2024.12   318.8 2025.44   328.6 2031.32
   341.6 2036.78   348.1 2040.24   380.8 2061.64   436.2  2082.2   452.5  2091.9
     459 2097.37   472.1 2106.48   488.4  2113.5   504.7 2122.26   534.1  2143.3
#Mann= 3 ,-1 , 0
       0     .12       0  216.31    .045       0  234.69     .12       0
Bank Sta=216.31,234.69
XS Rating Curve= 0 ,0
Exp/Cntr=0.3,0.1

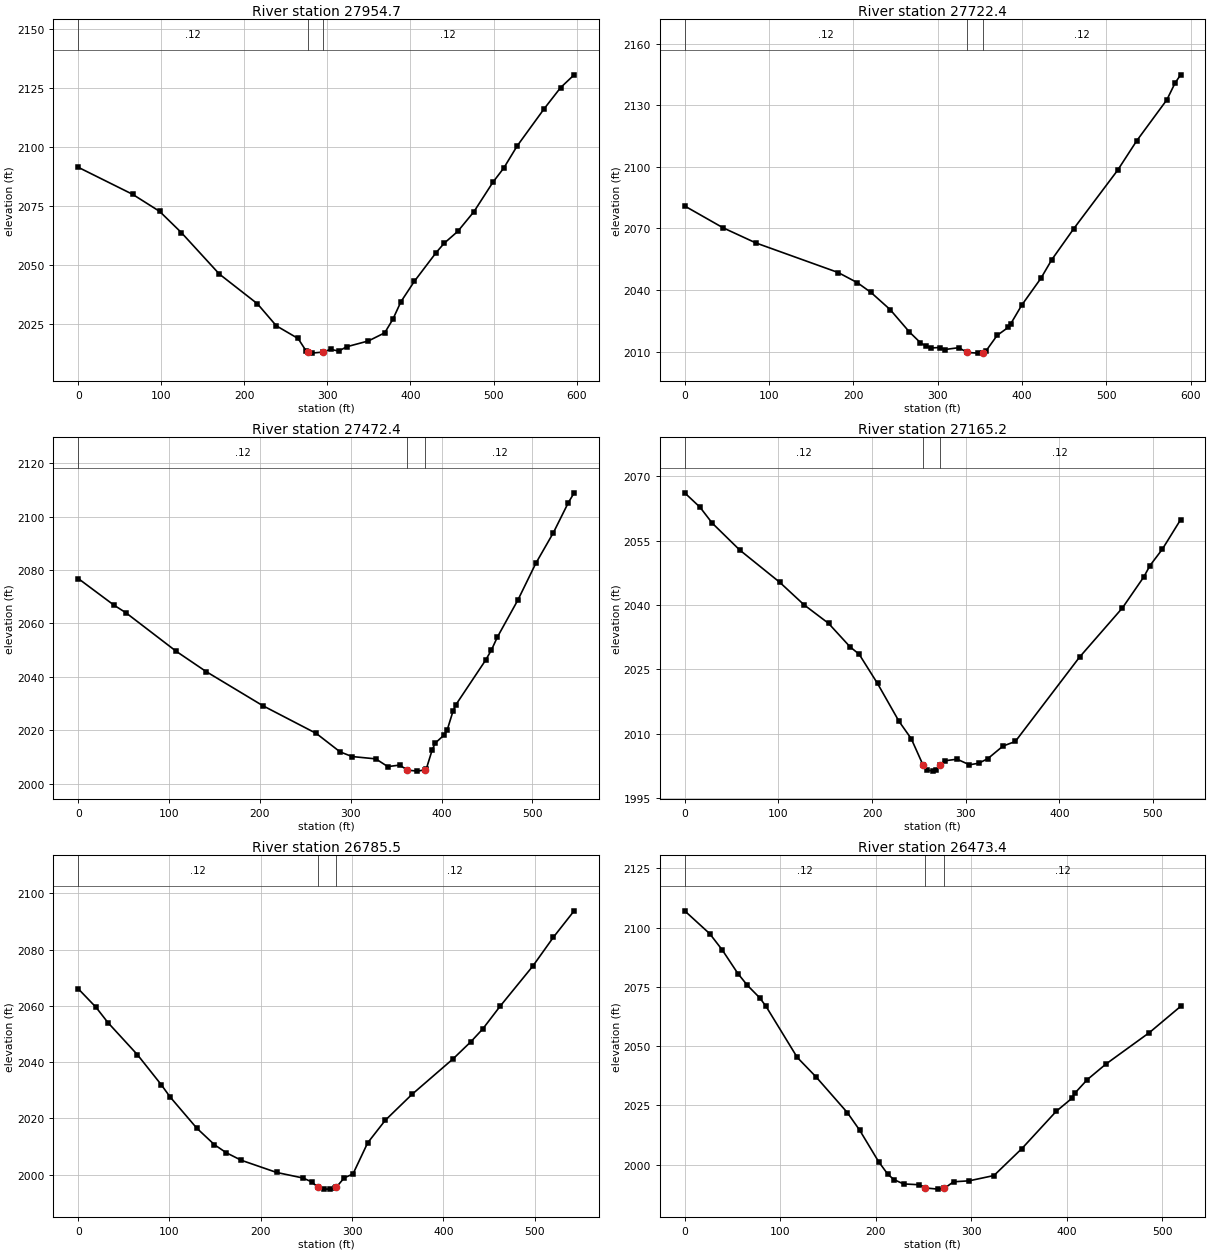
Type RM Length L Ch R = 1 ,27954.7 ,225.9,232.3,236
XS GIS Cut Line= 3
     2110145.479      196139.866     2110257.483      196401.155
     2110373.165      196691.755
#Sta/Elev= 30
       0 2091.48    65.4 2080.05      98 2072.81   124.2 2063.82   169.9 2046.28
   215.7 2033.71   238.5 2024.37   264.7    2019   274.5 2013.68  276.65 2013.21
     281  2012.8   294.22013.227   303.8  2014.4   313.6 2013.67   323.4 2015.51
   349.4 2017.96     369 2021.39   378.8 2027.11   388.5 2034.54   404.8 2043.24
   430.9 2055.35   440.7 2059.35     457 2064.36   476.5 2072.71   499.3 2085.15
   512.4 2091.18   528.6 2100.57   561.2 2116.35   580.8 2125.21   597.1 2130.62
#Mann= 3 ,-1 , 0
       0     .12       0  276.65    .045       0   294.2     .12       0
Bank Sta=276.65,294.2
XS Rating Curve= 0 ,0
Exp/Cntr=0.3,0.1

Type RM Length L Ch R = 1 ,27722.4 ,239.9,250,263.7
XS GIS Cut Line= 3
     2110006.381      196156.127     2110048.874      196498.076
     2110100.234      196736.178
#Sta/Elev= 30
       0 2080.91    45.5 2070.29    84.5  2062.9     182 2048.51   204.8 2043.56
     221 2038.79   243.8 2030.41   266.6 2019.52   279.6 2014.33   286.1 2012.61
   292.6 2011.78   302.3 2011.98   308.8 2011.01   325.1 2011.91   335.12009.565
   347.8 2009.25   354.12009.438   357.6 2010.44   370.6 2017.89   383.6 2021.76
   386.8 2023.58   399.8 2032.64   422.5 2045.69   435.5 2054.83   461.5 2069.89
   513.5 2098.32   536.2  2112.7   571.9 2132.63   581.7 2140.86   588.2 2144.78
#Mann= 3 ,-1 , 0
       0     .12       0   335.1    .045       0   354.1     .12       0
Bank Sta=335.1,354.1
XS Rating Curve= 0 ,0
Exp/Cntr=0.3,0.1

Type RM Length L Ch R = 1 ,27472.4 ,299.3,307.2,312.8
XS GIS Cut Line= 3
     2109919.085      196145.109     2109802.902      196500.118
     2109735.456      196658.812
#Sta/Elev= 30
       0 2076.82    39.3 2066.88    52.4 2064.04   108.1 2049.55   140.9    2042
   203.2 2029.26   262.1 2018.88   288.3 2011.98   301.4 2010.24   327.7 2009.36
   340.8 2006.47   353.9 2007.04  362.462005.153   373.5 2004.78  381.432005.235
   383.3 2005.69   389.8 2012.83   393.1 2015.28   402.8 2018.27   406.1 2020.02
   412.6 2027.18   415.8 2029.61   448.4 2046.22   454.9 2050.06   461.4 2054.87
   484.2 2068.87   503.7 2082.44   523.2    2094   539.5 2105.14     546 2108.87
#Mann= 3 ,-1 , 0
       0     .12       0  362.46    .045       0  381.43     .12       0
Bank Sta=362.46,381.43
XS Rating Curve= 0 ,0
Exp/Cntr=0.3,0.1

Type RM Length L Ch R = 1 ,27165.2 ,364.9,379.8,394.5
XS GIS Cut Line= 2
     2109754.637      196091.303      2109428.18      196508.178
#Sta/Elev= 30
       0 2066.18    16.3 2062.84    29.4 2059.12    58.8 2052.84   101.3 2045.36
   127.5 2040.06   153.6 2035.75   176.5 2030.29   186.3 2028.54   205.9 2021.73
   228.8 2012.92   241.9 2008.86   254.62002.666   258.2 2001.62   264.7  2001.3
     268 2001.48  272.672002.788   277.8 2003.72   290.9 2004.08     304 2002.78
   313.8 2003.13   323.6  2004.2   339.9 2007.15     353 2008.21   421.6 2027.88
   467.4 2039.36   490.3 2046.61   496.8 2049.23   509.9 2053.01   529.5 2059.92
#Mann= 3 ,-1 , 0
       0     .12       0   254.6    .045       0  272.67     .12       0
Bank Sta=254.6,272.67
XS Rating Curve= 0 ,0
Exp/Cntr=0.3,0.1

Type RM Length L Ch R = 1 ,26785.5 ,332.2,312,294.1
XS GIS Cut Line= 4
     2109557.245       195923.73     2109401.198      196040.272
     2109242.344      196081.938      2109144.33      196238.006
#Sta/Elev= 30
       0 2066.07    19.5 2059.48    32.5 2054.06    64.9 2042.61    90.9 2031.99
   100.6 2027.63   129.8 2016.54   149.3 2010.61   162.3 2007.76   178.5 2005.12
   217.3 2000.77   246.3 1998.79     256 1997.38   262.4 1995.53   268.8 1994.87
   275.3 1994.84   281.7 1995.09  282.85 1995.55   291.4 1998.85     301 2000.22
   317.1 2011.29   336.4 2019.32   365.5 2028.48   410.7 2041.16   430.1 2047.22
     443 2051.71   462.4 2059.94     498 2074.11   520.6  2084.4   543.3 2093.77
#Mann= 3 ,-1 , 0
       0     .12       0   262.4    .045       0  282.85     .12       0
Bank Sta=262.4,282.85
XS Rating Curve= 0 ,0
Exp/Cntr=0.3,0.1

Type RM Length L Ch R = 1 ,26473.4 ,246.5,249,252.7
XS GIS Cut Line= 3
     2109241.648       195644.16     2109128.832      195887.856
     2108987.543      196095.077
#Sta/Elev= 30
       0 2107.03    26.2  2097.4    39.3 2090.57    55.7 2080.61    65.5 2075.71
    78.6 2070.36    85.2 2066.76   117.9 2045.24   137.6 2037.03   170.3 2022.02
   183.4 2014.49     203 2001.37   212.9 1995.91   219.4  1993.7   229.2 1991.92
   245.6 1991.58   252.2 1990.22   265.3 1989.73   271.8 1990.03   281.6 1992.82
   297.9 1993.23   323.9 1995.46   353.2 2006.84   389.1 2022.52   405.4 2027.96
   408.6 2030.16   421.6 2035.87   441.2 2042.45   486.8 2055.74   519.4 2066.76
#Mann= 3 ,-1 , 0
       0     .12       0   252.2    .045       0   271.8     .12       0
Bank Sta=252.2,271.8
XS Rating Curve= 0 ,0
Exp/Cntr=0.3,0.1

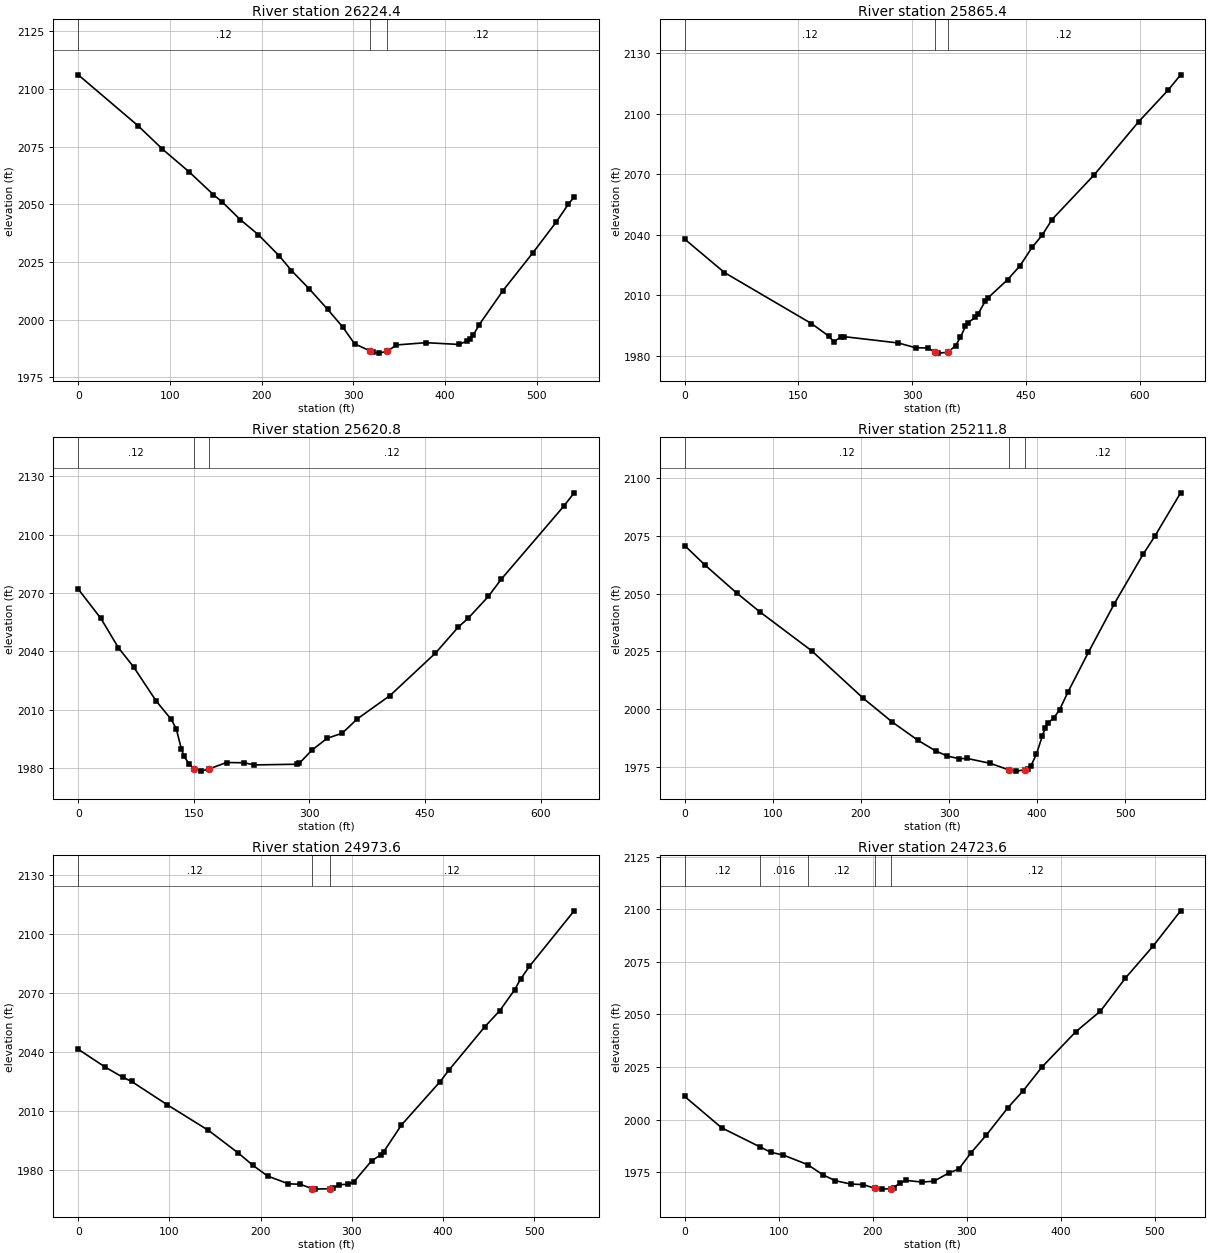
Type RM Length L Ch R = 1 ,26224.4 ,347.3,359,364.8
XS GIS Cut Line= 3
     2109075.946      195501.308     2108907.122      195782.138
     2108765.362      195941.489
#Sta/Elev= 30
       0 2106.13    65.5 2083.97    91.8 2073.96   121.2 2063.99   147.4  2054.2
   157.3 2050.94   176.9 2043.31   196.6  2036.8   219.5 2027.55   232.6  2021.3
   252.3 2013.22     272  2004.5   288.4 1996.87   301.5 1989.51     3181986.518
   321.1 1985.86   327.7 1985.48   337.31986.295   347.1 1989.02   379.4 1990.01
   414.9 1989.25   424.6 1990.71   427.8 1991.66   431.1 1993.39   437.5 1997.85
   463.4 2012.61   495.7 2028.84   521.6 2042.39   534.5 2049.97     541 2053.15
#Mann= 3 ,-1 , 0
       0     .12       0     318    .045       0   337.3     .12       0
Bank Sta=318,337.3
XS Rating Curve= 0 ,0
Exp/Cntr=0.3,0.1

Type RM Length L Ch R = 1 ,25865.4 ,274.6,244.6,214
XS GIS Cut Line= 3
      2108917.19      195387.911     2108595.208      195589.751
     2108530.714      195855.789
#Sta/Elev= 30
       0 2037.85    52.4 2021.27   167.1 1995.97     190 1989.74   196.6 1986.95
   206.4 1989.41   209.7 1989.49   281.7 1986.33   304.7 1983.95     321 1983.87
  329.341981.856   334.2  1981.3   347.3 1981.71   357.1 1985.07   363.6 1989.17
   370.2 1994.68   373.5 1996.48   383.3 1999.01   386.5 2000.51   396.3 2007.12
   399.6 2008.62   425.6 2017.68   441.9 2024.57   458.2 2033.84   471.3  2039.8
   484.3 2047.57   539.7 2069.65   598.4 2096.04   637.5  2111.8   653.8 2119.32
#Mann= 3 ,-1 , 0
       0     .12       0  329.34    .045       0   347.3     .12       0
Bank Sta=329.34,347.3
XS Rating Curve= 0 ,0
Exp/Cntr=0.3,0.1

Type RM Length L Ch R = 1 ,25620.8 ,399.1,409,416.9
XS GIS Cut Line= 3
     2108443.029      195225.973     2108549.635      195548.084
     2108486.336      195845.686
#Sta/Elev= 30
       0 2072.05    29.4 2056.98    52.2  2041.9    71.8  2032.1   101.1  2014.6
   120.7 2005.12   127.2 2000.34   133.8 1990.05     137 1986.35   143.6 1982.41
   150.1  1979.6   159.9 1978.54   169.6 1979.63   192.5 1982.97   215.3 1982.83
   228.4 1981.73   283.8 1982.08   287.1 1982.62   303.4 1989.37     323 1995.38
   342.6 1998.02   362.2 2005.37   404.7 2017.38   463.6 2039.15   493.1 2052.46
   506.2 2057.11   532.3 2068.28   548.7 2076.97   630.5 2114.79   643.6 2121.48
#Mann= 3 ,-1 , 0
       0     .12       0   150.1    .045       0   169.6     .12       0
Bank Sta=150.1,169.6
XS Rating Curve= 0 ,0
Exp/Cntr=0.3,0.1

Type RM Length L Ch R = 1 ,25211.8 ,235.2,238.2,241.7
XS GIS Cut Line= 2
      2108237.78      195265.089     2108192.547      195825.978
#Sta/Elev= 30
       0 2070.73    22.9 2062.35    58.9 2050.26    85.1 2042.13     144 2025.27
   202.8 2004.67   235.6 1994.44     265 1986.49   284.6 1982.02   297.7  1979.8
   310.8 1978.66   320.6 1978.72   346.8 1976.61   367.9 1973.76   376.2 1973.25
     386  1973.8   389.3 1974.06   392.6 1975.36   399.1 1980.56   405.7 1988.36
     409  1991.7   412.2 1994.02   418.8 1996.25   425.3 1999.72   435.1  2007.6
     458 2024.54   487.5  2045.6   520.2 2066.99   533.3 2074.68   562.7 2093.51
#Mann= 3 ,-1 , 0
       0     .12       0   367.9    .045       0     386     .12       0
Bank Sta=367.9,386
XS Rating Curve= 0 ,0
Exp/Cntr=0.3,0.1

Type RM Length L Ch R = 1 ,24973.6 ,254.9,250,241.9
XS GIS Cut Line= 3
     2108030.574      195319.676      2107978.28      195580.802
     2107909.793      195849.861
#Sta/Elev= 30
       0 2041.37    29.2 2032.41    48.7 2027.14    58.5 2024.99    97.4 2013.17
   142.9 2000.03   175.4 1988.58   191.6 1982.23   207.8 1976.77   230.6 1972.81
   243.6 1972.58   256.51970.366   259.8 1970.11   276.1 1970.34   279.4 1970.51
   285.9  1972.4   295.7 1972.55   302.2 1973.71   321.8 1984.51   331.6 1987.49
   334.9 1989.02   354.5 2002.74     397  2024.9   406.8 2030.86     446 2052.84
   462.3 2060.96   478.6 2071.58   485.2  2077.1     495 2083.65     544  2111.9
#Mann= 3 ,-1 , 0
       0     .12       0   256.5    .045       0   276.1     .12       0
Bank Sta=256.5,276.1
XS Rating Curve= 0 ,0
Exp/Cntr=0.3,0.1

Type RM Length L Ch R = 1 ,24723.6 ,257.4,249.7,241.1
XS GIS Cut Line= 3
     2107732.856      195346.064     2107739.326      195555.354
     2107768.799      195871.851
#Sta/Elev= 30
       0 2011.04    39.3 1996.15   80.451987.002    91.6 1984.51   104.7 1983.23
   130.8 1978.64   147.2 1973.75   160.3    1971   176.7 1969.42   189.8 1969.16
   202.8 1967.31   209.4 1967.01   219.2 1967.21   222.5 1967.69     229 1970.09
   235.6 1971.16     252 1970.37   265.1 1970.77   281.5 1974.86   291.3 1976.46
   304.4 1984.25   320.8 1992.73   343.8 2005.78   360.1 2013.84   379.8 2024.98
   415.8 2041.77   442.1 2051.61   468.3 2067.12   497.8 2082.36   527.3 2099.24
#Mann= 5 ,-1 , 0
       0     .12       0   80.45    .016       0   130.8     .12       0
   202.8    .045       0   219.2     .12       0
Bank Sta=202.8,219.2
XS Rating Curve= 0 ,0
Exp/Cntr=0.3,0.1

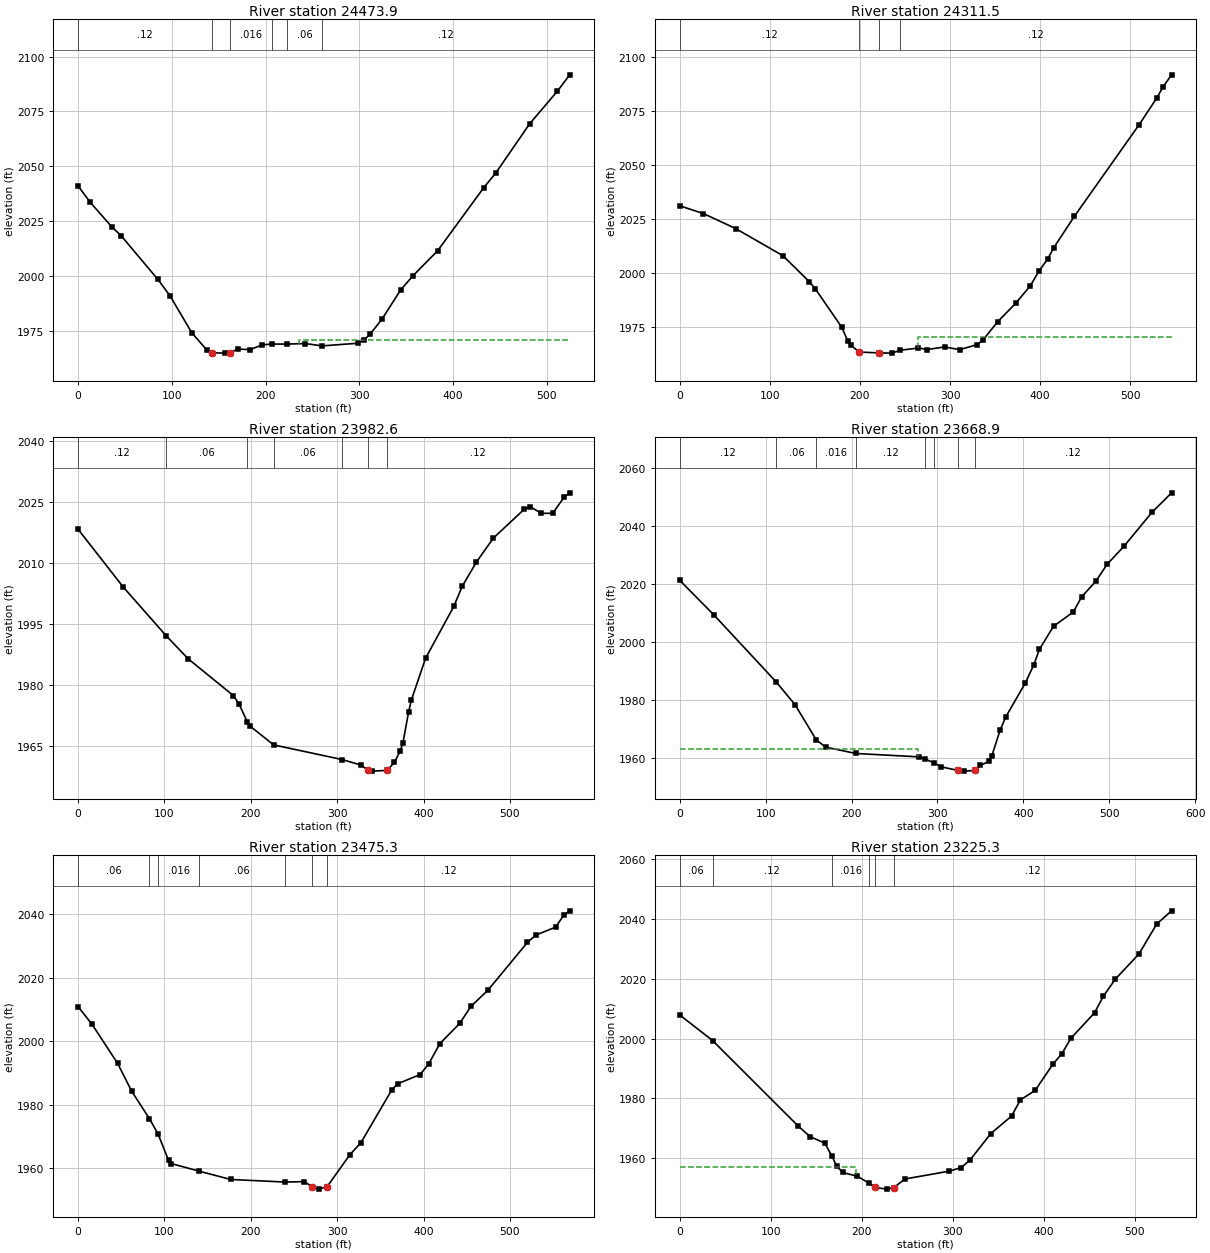
Type RM Length L Ch R = 1 ,24473.9 ,168,162.5,159.2
XS GIS Cut Line= 3
     2107444.634       195436.53     2107495.962       195574.72
     2107668.134      195910.085
#Sta/Elev= 30
       0 2041.07    13.1 2033.52      36 2022.38    45.9 2018.36    85.2 1998.38
    98.3  1990.8   121.2 1974.13   137.6 1966.08  142.711964.914   157.2 1964.76
  162.071964.899   170.4 1966.62   183.5 1966.36   196.6 1968.55  206.37 1968.88
  222.641968.892   242.5 1969.12  260.271968.068   298.2 1969.26   304.8 1970.75
   311.3 1973.29   324.4  1980.4   344.1 1993.59   357.2 2000.06   383.4 2011.39
   432.6 2040.17   445.7 2047.03   481.8 2069.44   511.3 2084.28   524.4  2091.7
#Mann= 6 ,-1 , 0
       0     .12       0  142.71    .045       0  162.07    .016       0
  206.37     .12       0  222.64     .06       0  260.27     .12       0
#XS Ineff= 2 , 0
                          235.62         1970.92
Permanent Ineff=
       F       F
Bank Sta=142.71,162.07
XS Rating Curve= 0 ,0
Exp/Cntr=0.3,0.1

Type RM Length L Ch R = 1 ,24311.5 ,320.4,328.9,336.5
XS GIS Cut Line= 2
      2107252.96      195508.527     2107569.257       195953.47
#Sta/Elev= 30
       0 2031.16    26.2 2027.59    62.1 2020.64   114.4 2008.14   143.8 1996.12
   150.4 1992.83   179.8  1975.1   186.3  1968.9   189.6 1966.79   199.4 1963.67
   220.61963.265   235.4 1963.16  244.911964.504   264.8 1965.52   274.6 1964.82
   294.2 1966.03   310.6 1964.75   330.2 1967.11   336.7 1969.32     353 1977.73
   372.7  1986.1     389 1994.19   398.8 2001.08   408.6  2006.8   415.2 2011.88
     438 2026.31     510 2068.69   529.6 2081.01   536.1 2085.89   545.9 2091.64
#Mann= 4 ,-1 , 0
       0     .12       0   199.4    .045       0   220.6    .016       0
  244.91     .12       0
#XS Ineff= 2 , 0
                           264.4         1970.64
Permanent Ineff=
       F       F
Bank Sta=199.4,220.6
XS Rating Curve= 0 ,0
Exp/Cntr=0.3,0.1

Type RM Length L Ch R = 1 ,23982.6 ,300.7,313.7,326.2
XS GIS Cut Line= 2
     2107054.594      195551.509      2107201.53      196101.473
#Sta/Elev= 30
       0 2018.27    52.4 2004.04  101.841992.129   127.6  1986.4   179.9 1977.37
   186.5 1975.27  195.931970.964   199.6  1969.8  226.511965.258  305.491961.666
   327.2 1960.33  335.591959.057   340.2 1958.81   357.71958.987   366.4 1960.96
     373 1963.76   376.2 1965.77   382.8 1973.41     386 1976.31   402.4 1986.55
   435.1  1999.3   444.9 2004.26   461.3 2010.19   480.9 2016.08   516.9 2023.22
   523.4 2023.79   536.5 2022.16   549.6 2022.17   562.7  2026.1   569.3  2027.2
#Mann= 7 ,-1 , 0
       0     .12       0  101.84     .06       0  195.93    .016       0
  226.51     .06       0  305.49     .12       0  335.59    .045       0
   357.7     .12       0
Bank Sta=335.59,357.7
XS Rating Curve= 0 ,0
Exp/Cntr=0.3,0.1

Type RM Length L Ch R = 1 ,23668.9 ,191.3,193.6,193
XS GIS Cut Line= 2
     2106938.057      195545.375     2106765.634        196091.4
#Sta/Elev= 30
       0 2021.18    39.3  2009.4  112.291986.131   134.2 1978.28     1591966.098
   170.1 1963.64  204.921961.476   278.1 1960.31   285.41959.547  296.371958.182
   304.3 1956.84   323.9 1955.65   330.5 1955.38   343.6  1955.6   350.1 1957.36
   359.9 1958.74   363.2 1960.57     373 1969.57   379.6 1974.13   402.5  1985.9
   412.3 1992.16   418.8 1997.47   435.2  2005.4   458.1 2010.27   467.9 2015.54
   484.3 2020.85   497.4 2026.73     517 2032.93   549.7 2044.67   572.6 2051.43
#Mann= 8 ,-1 , 0
       0     .12       0  112.29     .06       0     159    .016       0
  204.92     .12       0   285.4     .06       0  296.37     .12       0
   323.9    .045       0   343.6     .12       0
#XS Ineff= 2 , 0
           277.4 1963.11
Permanent Ineff=
       F       F
Bank Sta=323.9,343.6
XS Rating Curve= 0 ,0
Exp/Cntr=0.3,0.1

Type RM Length L Ch R = 1 ,23475.3 ,263.2,250,239.7
XS GIS Cut Line= 3
     2106767.537       195538.11     2106655.977      195796.825
      2106575.48      196072.731
#Sta/Elev= 30
       0 2010.93    16.4 2005.27    45.9 1992.99    62.2  1984.2   82.651975.583
   92.75 1970.71   104.8  1962.4   108.1 1961.41   140.51958.999   176.9  1956.4
  239.641955.594   262.1 1955.72  270.941954.119   278.5 1953.36   288.3 1954.11
   314.4  1964.1   327.5 1968.02   363.4 1984.73   369.9 1986.56     396 1989.49
   405.8 1992.78   418.9 1999.25   441.8  2005.6   454.8 2010.97   474.4 2016.06
   520.2 2031.13     530 2033.46   552.8 2035.97   562.6 2039.85   569.2 2041.11
#Mann= 7 ,-1 , 0
       0     .06       0   82.65     .12       0   92.75    .016       0
   140.5     .06       0  239.64     .12       0  270.94    .045       0
   288.3     .12       0
Bank Sta=270.94,288.3
XS Rating Curve= 0 ,0
Exp/Cntr=0.3,0.1

Type RM Length L Ch R = 1 ,23225.3 ,241,250,259.9
XS GIS Cut Line= 3
     2106378.101      195530.009     2106419.184      195750.684
     2106470.903      196062.463
#Sta/Elev= 30
       0 2007.88   35.971999.366   130.1 1970.78   143.1 1967.28   159.4 1965.05
   167.1 1960.76   172.4 1957.47   178.9 1955.28   195.2    1954  208.081951.685
   214.51950.254   227.7 1949.71  235.341950.244   247.3 1953.09   296.2 1955.72
   309.2 1956.92     319 1959.45   341.8 1968.27   364.6 1974.12   374.3 1979.52
   390.6 1982.71   410.2 1991.52     420 1994.98   429.7 2000.06   455.8 2008.62
   465.6 2014.21   478.6 2019.85   504.7 2028.32   524.2 2038.32   540.5 2042.71
#Mann= 6 ,-1 , 0
       0     .06       0   35.97     .12       0   167.1    .016       0
  208.08     .12       0   214.5    .045       0  235.34     .12       0
#XS Ineff= 2 , 0
          193.81 1957.23
Permanent Ineff=
       F       F
Bank Sta=214.5,235.34
XS Rating Curve= 0 ,0
Exp/Cntr=0.3,0.1

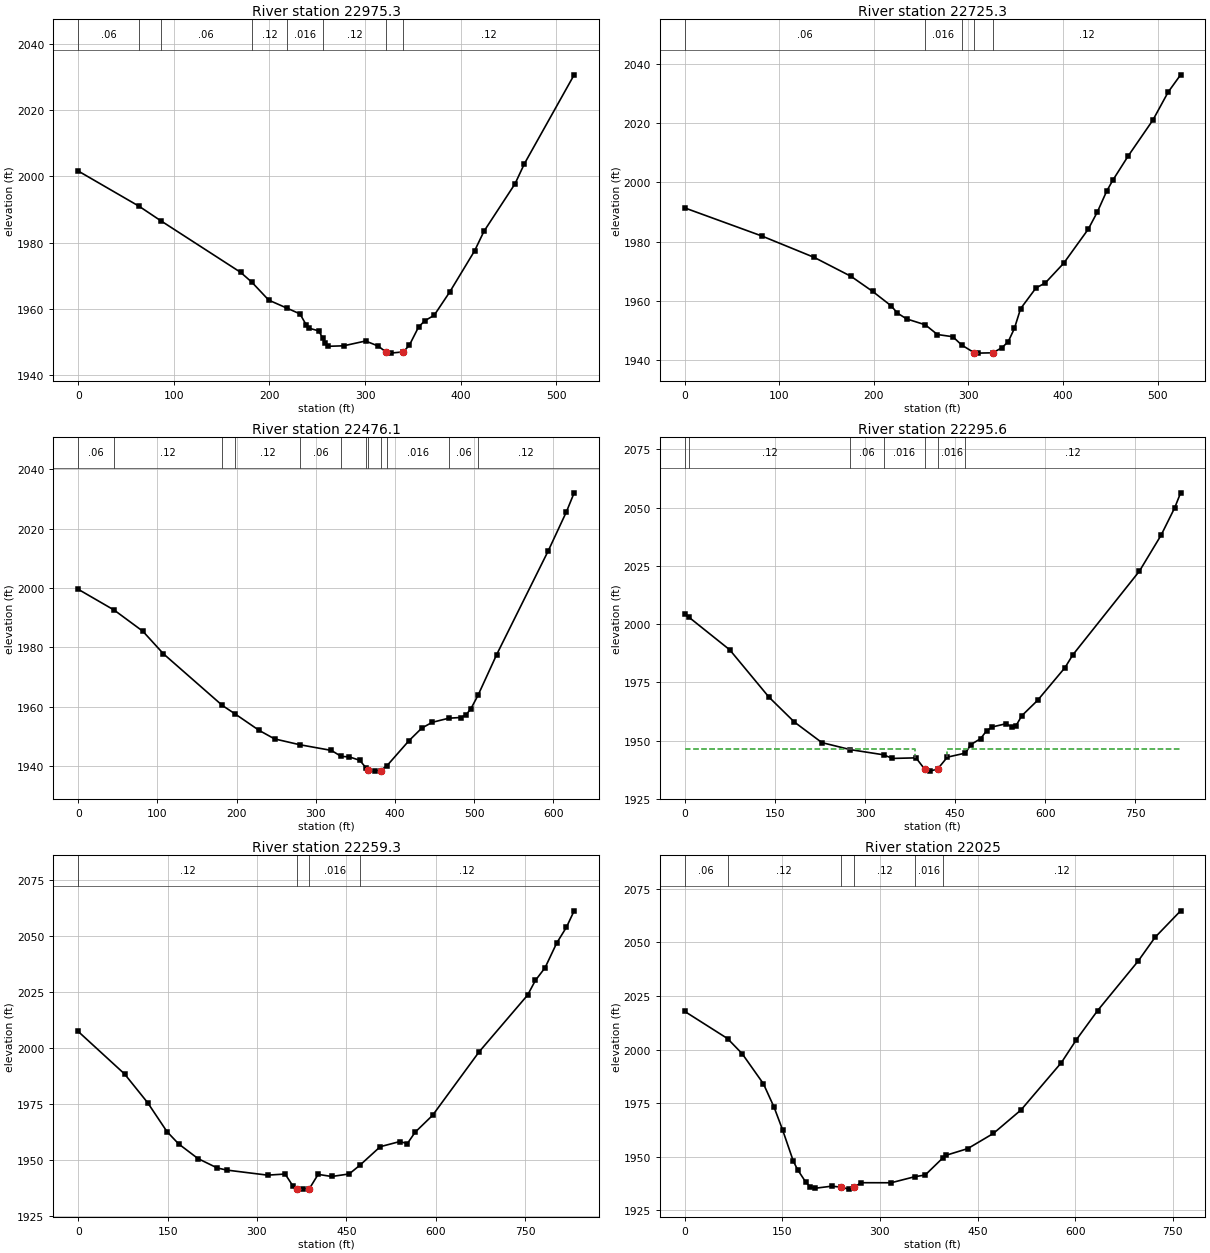
Type RM Length L Ch R = 1 ,22975.3 ,240.3,250,254.5
XS GIS Cut Line= 3
     2106264.552      195520.816     2106197.067      195843.745
     2106146.173      196025.454
#Sta/Elev= 30
       0 2001.59    63.61990.962   86.061986.636   169.8 1971.02  181.651968.016
   199.2 1962.63  218.771960.145   231.9 1958.47   238.4 1955.16   241.7 1954.14
   251.5 1953.34  255.781951.134     258 1949.74   261.3 1948.69   277.6 1948.84
   300.5 1950.29   313.6 1948.78  321.791946.981   326.6 1946.63   339.91947.006
   346.2 1948.98   355.9  1954.5   362.4  1956.4   372.2 1958.04   388.5 1965.08
   414.5  1977.5   424.3  1983.4   456.8 1997.75   466.6  2003.8   518.6 2030.62
#Mann= 8 ,-1 , 0
       0     .06       0    63.6     .12       0   86.06     .06       0
  181.65     .12       0  218.77    .016       0  255.78     .12       0
  321.79    .045       0   339.9     .12       0
Bank Sta=321.79,339.9
XS Rating Curve= 0 ,0
Exp/Cntr=0.3,0.1

Type RM Length L Ch R = 1 ,22725.3 ,239.7,249.2,260.1
XS GIS Cut Line= 3
      2106148.72      195496.318     2105975.191      195752.706
     2105881.083      195945.648
#Sta/Elev= 30
       0 1991.36    81.5 1981.89   136.9 1974.67     176 1968.25   198.8 1963.18
   218.3 1958.33   224.9 1955.89   234.6 1953.93  254.371951.938   267.2 1948.66
   283.5 1947.92  292.791945.139   306.3 1942.48   309.6 1942.39   325.8  1942.5
   335.6 1944.26   342.1 1946.29   348.6 1950.74   355.1 1957.37   371.4 1964.37
   381.2 1966.04   400.7  1972.7   426.7  1984.2   436.4 1990.07   446.2 1997.05
   452.7 2000.73     469 2008.92     495 2020.97   511.2 2030.44   524.3 2036.22
#Mann= 5 ,-1 , 0
       0     .06       0  254.37    .016       0  292.79     .12       0
   306.3    .045       0   325.8     .12       0
Bank Sta=306.3,325.8
XS Rating Curve= 0 ,0
Exp/Cntr=0.3,0.1

Type RM Length L Ch R = 1 ,22476.1 ,147.3,180.4,212.7
XS GIS Cut Line= 3
     2106087.605      195405.867     2105776.667      195627.228
     2105580.847       195773.59
#Sta/Elev= 30
       0 1999.58   45.391992.579    81.6 1985.46   107.6 1977.86  182.041960.468
   198.5 1957.55   228.4 1952.09   247.9 1949.22  279.721947.259   319.7 1945.34
  331.911943.341   342.5 1943.15   355.6    1942  363.321939.468   365.4 1938.68
   375.2 1938.37   381.7 1938.58  390.091940.261   417.5 1948.58   433.8 1952.85
   446.9 1954.79   467.91956.184   482.7 1956.42   489.2 1957.17   495.8 1959.36
  504.781963.875   528.4 1977.62   593.6 2012.59   616.4 2025.64   626.2 2032.05
#Mann= 12 ,-1 , 0
       0     .06       0   45.39     .12       0  182.04     .06       0
   198.5     .12       0  279.72     .06       0  331.91    .016       0
  363.32     .12       0   365.4    .045       0   381.7     .12       0
  390.09    .016       0   467.9     .06       0  504.78     .12       0
Bank Sta=365.4,381.7
XS Rating Curve= 0 ,0
Exp/Cntr=0.3,0.1

Type RM Length L Ch R = 1 ,22295.6 ,36.4,36.4,36.4
XS GIS Cut Line= 4
     2106066.059       195376.14     2105833.574      195544.397
     2105714.341      195423.824      2105537.63      195747.233
#Sta/Elev= 30
       0 2004.36    6.682003.057      75 1988.97   140.2 1968.67   182.6 1957.95
   228.3 1949.14  275.71 1946.12  330.811943.915   345.7 1942.35   384.8  1942.6
  399.04 1937.84   407.6  1936.9   420.7 1937.77     437  1942.9  467.14 1944.65
   476.1 1948.28   492.4 1950.86   502.2 1954.23     512 1955.88   534.8 1957.26
   544.6 1955.77   551.1 1956.34   560.9 1960.69     587 1967.25   632.7 1981.33
   645.7  1986.8   756.6 2022.78   792.5 2038.14   815.3 2049.98   825.1 2056.38
#Mann= 7 ,-1 , 0
       0     .06       0    6.68     .12       0  275.71     .06       0
  330.81    .016       0  399.04    .045       0   420.7    .016       0
  467.14     .12       0
#XS Ineff= 2 , 0
           383.9 1946.49  436.53         1946.49
Permanent Ineff=
       F       F
Bank Sta=399.04,420.7
XS Rating Curve= 0 ,0
Exp/Cntr=0.3,0.1

Type RM Length L Ch R = 1 ,22259.3 ,278.7,234.2,184.5
XS GIS Cut Line= 4
     2106051.953      195357.694     2105844.424      195507.505
     2105725.191      195386.932     2105530.035      195743.978
#Sta/Elev= 30
       0  2007.2    77.8 1988.23   116.6 1975.39     149 1962.49   168.5 1957.02
   200.9 1950.48   233.3 1946.27   249.5 1945.32   317.9 1943.06   347.3 1943.56
   360.3 1938.25   366.8 1937.08   376.6 1936.82  388.011937.041   402.7 1943.41
   425.5 1942.46   454.8  1943.6  472.381947.394   506.9 1955.76   539.5 1958.04
   552.5 1957.18   565.5 1962.23   594.8 1969.77   672.9 1998.12   754.3 2023.46
   767.3 2029.98   783.6 2035.68   803.1 2046.68   819.4 2053.72   832.4 2061.07
#Mann= 4 ,-1 , 0
       0     .12       0   366.8    .045       0  388.01    .016       0
  472.38     .12       0
Bank Sta=366.8,388.01
XS Rating Curve= 0 ,0
Exp/Cntr=0.3,0.1

Type RM Length L Ch R = 1 ,22025   ,318.6,295.3,269.2
XS GIS Cut Line= 2
     2105842.837       195043.61     2105496.046      195722.214
#Sta/Elev= 30
       0 2017.78   65.822005.112    88.3 1998.07     121 1984.04   137.4  1973.1
   150.4  1962.6   166.8 1948.08   173.4 1944.04   186.4 1938.04     193 1935.95
   199.5 1935.29   225.7 1936.29   240.4 1935.85   251.8 1934.92   260.71935.967
   271.5 1937.91   317.3 1937.89  353.441940.701   369.6  1941.5   396.71949.464
   402.3 1950.76     435 1953.81   474.3 1960.87   516.8 1971.82   578.9 1993.91
   601.8 2004.52   634.5 2018.14   696.7 2041.17   722.8  2052.3   762.1 2064.66
#Mann= 6 ,-1 , 0
       0     .06       0   65.82     .12       0   240.4    .045       0
   260.7     .12       0  353.44    .016       0   396.7     .12       0
Bank Sta=240.4,260.7
XS Rating Curve= 0 ,0
Exp/Cntr=0.3,0.1