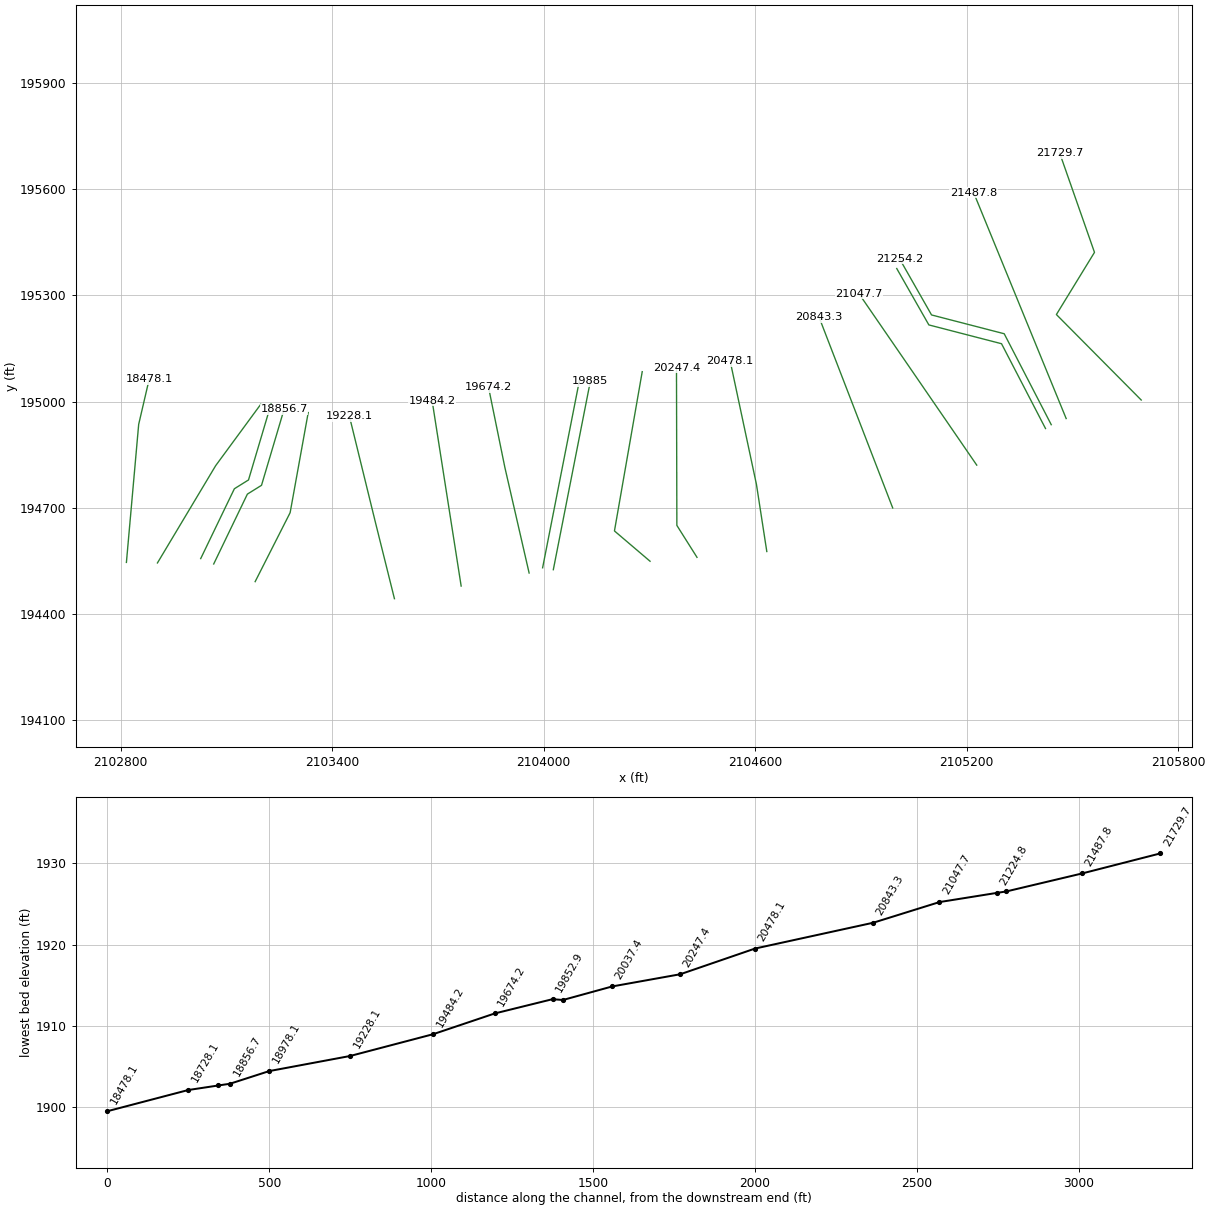
HEC-RAS study TRKYCK.prj: TRKYCK

--- TRKYCK.g01 (geometry) --- (continued)

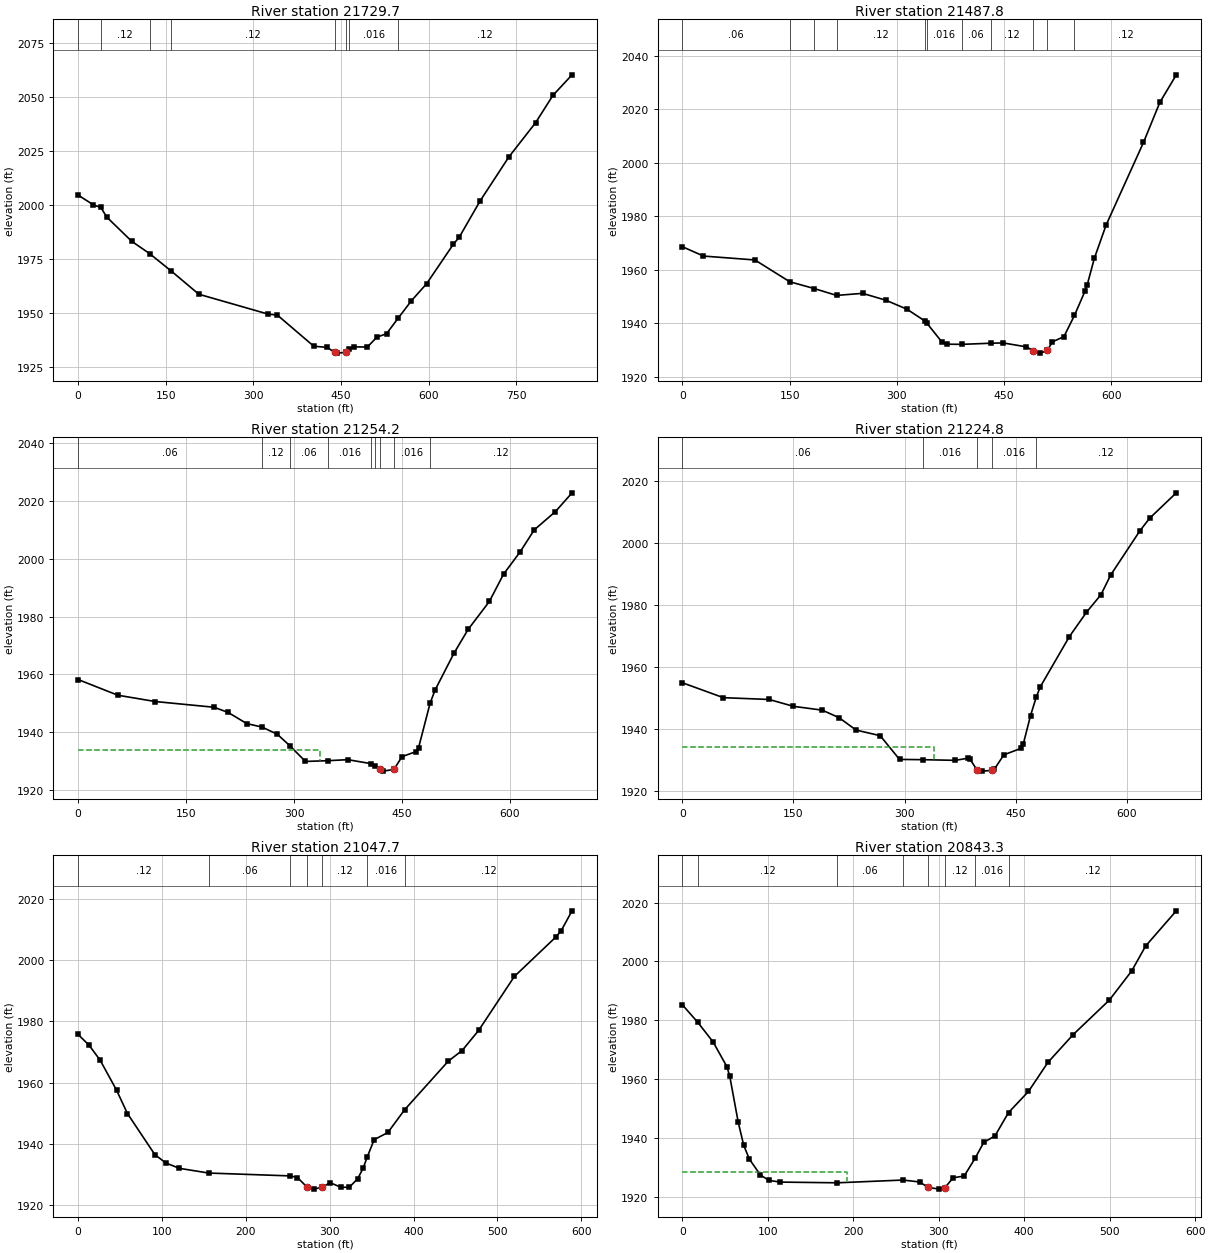
Type RM Length L Ch R = 1 ,21729.7 ,220.1,241.9,262.8
XS GIS Cut Line= 4
     2105695.224      195004.246     2105454.583      195246.001
     2105562.656      195421.782     2105463.892      195702.734
#Sta/Elev= 30
       0 2004.53    26.2 2000.01   38.85  1998.8    49.2 1994.28    91.8 1983.09
  122.191977.417  159.471969.294   206.6 1958.54   324.7 1949.36   341.1 1948.84
   403.3 1934.43   426.3 1933.88   439.21931.538   442.6 1931.22     459 1931.59
  464.431933.061   472.1 1934.12     495 1934.05   511.4 1938.64   527.8 1940.21
  547.771947.461   570.4 1955.51   596.5 1963.45   642.4 1981.82   652.2 1984.99
   688.2 2001.92   737.3 2022.28   783.1 2038.18   812.5 2050.77   845.3 2060.33
#Mann= 8 ,-1 , 0
       0     .06       0   38.85     .12       0  122.19     .06       0
  159.47     .12       0   439.2    .045       0     459     .12       0
  464.43    .016       0  547.77     .12       0
Bank Sta=439.2,459
XS Rating Curve= 0 ,0
Exp/Cntr=0.3,0.1

Type RM Length L Ch R = 1 ,21487.8 ,212.4,233.6,254.6
XS GIS Cut Line= 2
     2105482.292      194951.878     2105219.705      195590.983
#Sta/Elev= 30
       0 1968.54    29.5 1965.04   101.5 1963.58  150.231955.435  184.251952.909
  215.731950.331   252.2  1951.1   284.9 1948.51   314.4 1945.15  339.731940.677
  341.831940.029   363.5 1932.77     370 1932.09  391.181932.033  431.19 1932.45
   448.6 1932.57   481.4 1931.09   491.2 1929.56     501 1928.75   510.81929.748
   517.4 1932.93   533.8 1934.93  548.531942.858   563.2 1951.87   566.5  1954.4
   576.3 1964.15   592.7 1976.57   645.1 2007.52     668  2022.5     691  2032.8
#Mann= 11 ,-1 , 0
       0     .06       0  150.23     .08       0  184.25     .06       0
  215.73     .12       0  339.73     .06       0  341.83    .016       0
  391.18     .06       0  431.19     .12       0   491.2    .045       0
   510.8    .016       0  548.53     .12       0
Bank Sta=491.2,510.8
XS Rating Curve= 0 ,0
Exp/Cntr=0.3,0.1

Type RM Length L Ch R = 1 ,21254.2 ,29.4,29.4,29.4
XS GIS Cut Line= 4
     2105439.974      194934.516      2105306.51      195191.678
     2105100.347      195244.846     2105009.201      195404.351
#Sta/Elev= 30
       0 1958.22    55.3 1952.79   107.4 1950.61   188.8 1948.64   208.4 1946.85
   234.4 1942.98  255.441941.784   276.7 1939.32  294.071935.359   315.9 1929.89
  347.631930.158   374.9  1930.5  406.741929.143  412.441928.303  419.36 1927.11
   423.8 1926.54  438.781927.117   450.2 1931.56   469.9 1933.32   473.2  1934.7
  489.131950.028   496.1 1954.61   522.3 1967.32     542 1975.56   571.5 1985.23
   591.2 1994.66   614.2 2002.36   633.9    2010   663.4 2016.34   686.4 2022.81
#Mann= 9 ,-1 , 0
       0     .06       0  255.44     .12       0  294.07     .06       0
  347.63    .016       0  406.74     .06       0  412.44    .016       0
  419.36    .045       0  438.78    .016       0  489.13     .12       0
#XS Ineff= 2 , 0
          336.64 1933.99
Permanent Ineff=
       F       F
Bank Sta=419.36,438.78
XS Rating Curve= 0 ,0
Exp/Cntr=0.3,0.1

Type RM Length L Ch R = 1 ,21224.8 ,193.3,177.2,160.8
XS GIS Cut Line= 4
     2105423.698      194923.666     2105298.915      195163.466
     2105092.752      195216.634     2105001.606       195376.14
#Sta/Elev= 30
       0  1954.9    55.4 1950.08   117.2  1949.5   149.8 1947.29   188.9 1946.05
   211.7  1943.6   234.5 1939.62   267.1 1937.81   293.2 1930.14   324.4 1930.06
   368.6 1929.84     385 1930.51   388.2 1930.28   398.1 1926.62   404.6 1926.36
   417.7 1926.59     421 1926.91   434.1 1931.62     457  1933.7   460.3 1935.12
   470.1 1944.29  477.781950.249   483.2 1953.56   522.6 1969.83   545.6 1977.65
   565.2 1983.34   578.4 1989.73   617.7 2003.95   630.9 2008.02   666.9 2016.23
#Mann= 5 ,-1 , 0
       0     .06       0   324.4    .016       0   398.1    .045       0
   417.7    .016       0  477.78     .12       0
#XS Ineff= 2 , 0
          340.25 1934.19
Permanent Ineff=
       F       F
Bank Sta=398.1,417.7
XS Rating Curve= 0 ,0
Exp/Cntr=0.3,0.1

Type RM Length L Ch R = 1 ,21047.7 ,209.5,204.3,199
XS GIS Cut Line= 3
     2105228.573      194820.142       2105037.6      195097.359
     2104894.296      195305.127
#Sta/Elev= 30
       0 1975.72    13.1 1972.21    26.2 1967.36    45.8 1957.57    58.8 1949.92
    91.5  1936.5   104.6 1933.77   120.9 1932.01  155.75 1930.48  252.931929.548
   261.5 1929.02   272.71925.976   281.1 1925.23   290.9 1925.87   300.7 1927.32
   313.8 1925.78   323.6  1925.9   333.4 1928.63   339.9 1932.05  344.841935.782
     353 1941.37   369.4 1943.72  389.461951.186   441.5 1967.04   457.9 1970.48
   477.6 1977.04   520.2 1994.66   569.4 2007.47   575.9 2009.55     589  2016.1
#Mann= 7 ,-1 , 0
       0     .12       0  155.75     .06       0  252.93     .12       0
   272.7    .045       0   290.9     .12       0  344.84    .016       0
  389.46     .12       0
Bank Sta=272.7,290.9
XS Rating Curve= 0 ,0
Exp/Cntr=0.3,0.1

Type RM Length L Ch R = 1 ,20843.3 ,370.2,365.2,360.9
XS GIS Cut Line= 2
     2104990.174      194698.985     2104781.411      195238.004
#Sta/Elev= 30
       0 1985.28   17.841979.407    35.9  1972.7    52.2 1964.23    55.5 1960.96
    65.3 1945.49    71.8 1937.56    78.4 1932.88    91.4 1927.47   101.2 1925.68
   114.3 1925.08  181.211924.839  258.161925.771   277.6 1925.13   287.4  1923.3
   300.4 1922.69     307 1923.08   316.8 1926.54   329.8 1927.14  342.58 1933.19
   352.7 1938.57   365.8 1940.76  381.671948.688     405 1955.85   427.8 1965.74
   457.2 1975.13   499.7  1986.9   525.8 1996.78   542.1 2005.24     578  2017.2
#Mann= 8 ,-1 , 0
       0     .06       0   17.84     .12       0  181.21     .06       0
  258.16     .12       0   287.4    .045       0     307     .12       0
  342.58    .016       0  381.67     .12       0
#XS Ineff= 2 , 0
          192.57 1928.61
Permanent Ineff=
       F       F
Bank Sta=287.4,307
XS Rating Curve= 0 ,0
Exp/Cntr=0.3,0.1

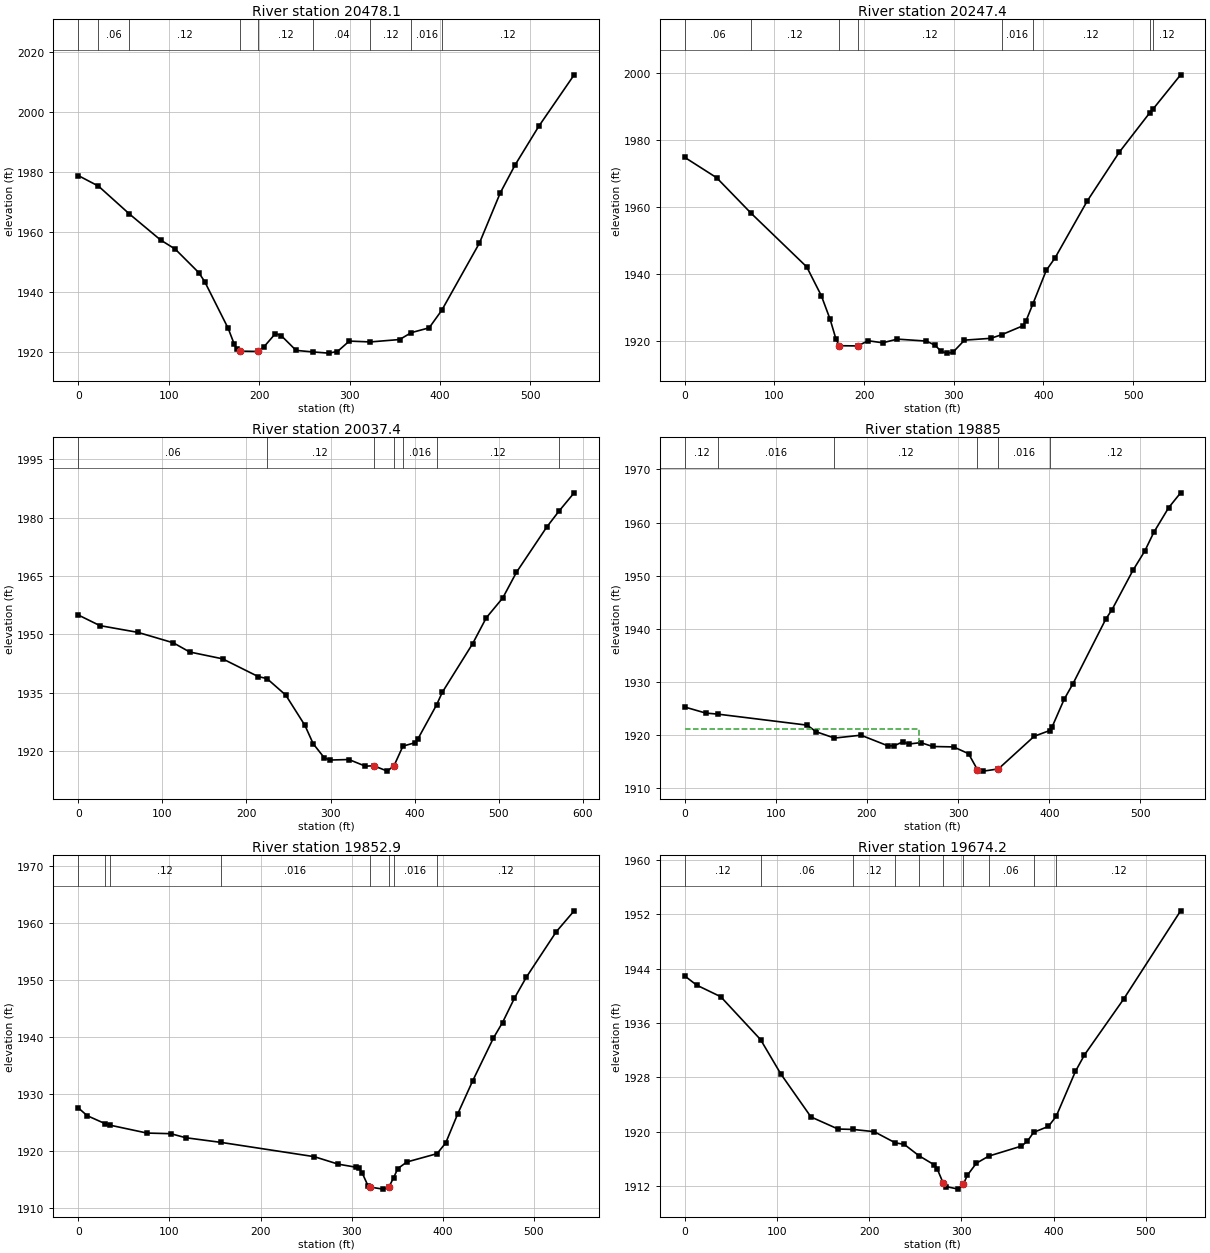
Type RM Length L Ch R = 1 ,20478.1 ,234.2,230.7,225.9
XS GIS Cut Line= 3
      2104632.93      194575.828     2104603.592      194765.371
     2104529.075      195114.016
#Sta/Elev= 30
       0 1978.69   22.371975.168   56.611965.878      91 1957.23   107.3 1954.16
   133.3 1946.33   139.8 1943.36   165.8 1927.76   172.3 1922.66   175.6 1920.79
   178.8 1920.17   198.3 1920.07   204.9 1921.45     218 1926.01   224.5 1925.32
   240.9 1920.42  259.791919.899   276.8 1919.51   286.6 1920.05   299.7 1923.52
  322.971923.241   355.3 1924.04  368.231926.334     388 1927.94  401.971933.809
   443.6  1956.2   466.6  1972.9   482.9 1982.16   509.1 1995.06   548.3 2012.25
#Mann= 9 ,-1 , 0
       0     .12       0   22.37     .06       0   56.61     .12       0
   178.8    .045       0   198.3     .12       0  259.79     .04       0
  322.97     .12       0  368.23    .016       0  401.97     .12       0
Bank Sta=178.8,198.3
XS Rating Curve= 0 ,0
Exp/Cntr=0.3,0.1

Type RM Length L Ch R = 1 ,20247.4 ,213.1,210,204.9
XS GIS Cut Line= 3
     2104434.857      194559.379      2104377.76      194649.647
     2104376.667      195095.839
#Sta/Elev= 30
       0 1974.91    35.6 1968.82    74.31958.125   136.1 1942.14   152.4 1933.51
   162.2 1926.44   168.7 1920.54   172.41918.566   193.11918.504   204.5 1920.06
   220.8 1919.44   237.1 1920.54   269.6 1919.95   279.4 1918.69   285.9 1916.86
   292.4 1916.35     299 1916.57     312 1920.23   341.3 1920.78   353.5 1921.86
   377.1 1924.52   380.4 1925.86  388.261931.063   403.2 1941.11     413 1944.84
   448.8 1961.82   484.6 1976.45  518.681988.271  522.33 1989.38     553 1999.59
#Mann= 8 ,-1 , 0
       0     .06       0    74.3     .12       0   172.4    .045       0
   193.1     .12       0   353.5    .016       0  388.26     .12       0
  518.68     .06       0  522.33     .12       0
Bank Sta=172.4,193.1
XS Rating Curve= 0 ,0
Exp/Cntr=0.3,0.1

Type RM Length L Ch R = 1 ,20037.4 ,152.7,152.4,151.6
XS GIS Cut Line= 3
     2104301.683       194548.32     2104200.677      194634.022
     2104279.472      195084.431
#Sta/Elev= 30
       0    1955    25.8 1952.26    71.1 1950.52   113.1 1947.84   132.5 1945.48
   171.7 1943.72   214.1 1939.15  224.371938.653   246.8 1934.39   269.6  1926.6
   279.4 1921.89   292.5  1918.3     299  1917.7   321.9 1917.83   341.5 1916.12
   351.3 1916.24   367.6 1914.85  375.631916.289  386.111921.277   400.3 1922.14
   403.6 1923.01  426.041931.855   432.9 1935.11   468.9 1947.58   485.2 1954.27
   504.8 1959.37   521.1 1965.97     557 1977.57  571.651981.692   589.7  1986.4
#Mann= 7 ,-1 , 0
       0     .06       0  224.37     .12       0   351.3    .045       0
  375.63     .12       0  386.11    .016       0  426.04     .12       0
  571.65     .06       0
Bank Sta=351.3,375.63
XS Rating Curve= 0 ,0
Exp/Cntr=0.3,0.1

Type RM Length L Ch R = 1 ,19885   ,32,32.1,31.9
XS GIS Cut Line= 2
     2104027.213       194524.36     2104132.465      195058.214
#Sta/Elev= 30
       0 1925.26      23 1924.12    36.91923.905   134.4 1921.84   144.2  1920.6
  164.361919.408   193.4 1919.95   222.9 1917.95   229.4 1917.92   239.3  1918.7
   245.8 1918.28     259 1918.55   272.1 1917.82     295 1917.74   311.4 1916.47
   321.2 1913.45   327.8 1913.18   344.2  1913.6   383.5 1919.75  400.531920.828
   403.2 1921.54   416.3  1926.7   426.1 1929.68   462.2 1941.88   468.7 1943.55
   491.7 1950.97   504.8 1954.64   514.6 1958.13     531 1962.81   544.1  1965.6
#Mann= 6 ,-1 , 0
       0     .12       0    36.9    .016       0  164.36     .12       0
   321.2    .045       0   344.2    .016       0  400.53     .12       0
#XS Ineff= 2 , 0
          256.97 1921.15
Permanent Ineff=
       F       F
Bank Sta=321.2,344.2
XS Rating Curve= 0 ,0
Exp/Cntr=0.3,0.1

Type RM Length L Ch R = 1 ,19852.9 ,168.7,178.7,188
XS GIS Cut Line= 2
     2103996.832      194529.786     2104102.083       195063.64
#Sta/Elev= 30
       0 1927.54     9.8 1926.16   29.481924.761   34.581924.504    75.4 1923.11
   101.6    1923     118 1922.29  156.541921.477     259 1918.97   285.2 1917.66
   304.8 1917.12   308.1  1916.9   311.4 1916.17     318 1913.84  319.621913.656
   334.4 1913.28   340.9 1913.65  345.991915.277   350.7 1916.89   360.6 1918.04
  393.711919.498   403.2 1921.38   416.3 1926.45   432.7 1932.24   455.6 1939.79
   465.5 1942.48   478.6 1946.76   491.7 1950.45   524.5 1958.41   544.1 1962.07
#Mann= 8 ,-1 , 0
       0     .12       0   29.48     .06       0   34.58     .12       0
  156.54    .016       0  319.62    .045       0   340.9     .12       0
  345.99    .016       0  393.71     .12       0
Bank Sta=319.62,340.9
XS Rating Curve= 0 ,0
Exp/Cntr=0.3,0.1

Type RM Length L Ch R = 1 ,19674.2 ,191.5,190,188.6
XS GIS Cut Line= 3
      2103958.56      194515.033     2103889.766      194813.608
     2103843.405      195040.151
#Sta/Elev= 30
       0 1942.95      13 1941.59    39.1 1939.88   82.281933.556   104.3 1928.48
   136.9 1922.16   166.2 1920.38  182.521920.319   205.4 1919.99  228.321918.342
     238 1918.12   253.81916.458   270.5  1915.1   273.8 1914.48   280.3 1912.39
   283.6 1911.89   296.6 1911.52  302.221912.271   306.4 1913.56   316.2 1915.34
  329.571916.384     365 1917.86   371.5 1918.58   378.21919.884   394.3 1920.77
  402.681922.237   423.6 1928.88   433.4 1931.31   475.8 1939.52   537.6 1952.54
#Mann= 10 ,-1 , 0
       0     .12       0   82.28     .06       0  182.52     .12       0
  228.32     .06       0   253.8     .12       0   280.3    .045       0
  302.22     .12       0  329.57     .06       0   378.2    .016       0
  402.68     .12       0
Bank Sta=280.3,302.22
XS Rating Curve= 0 ,0
Exp/Cntr=0.3,0.1

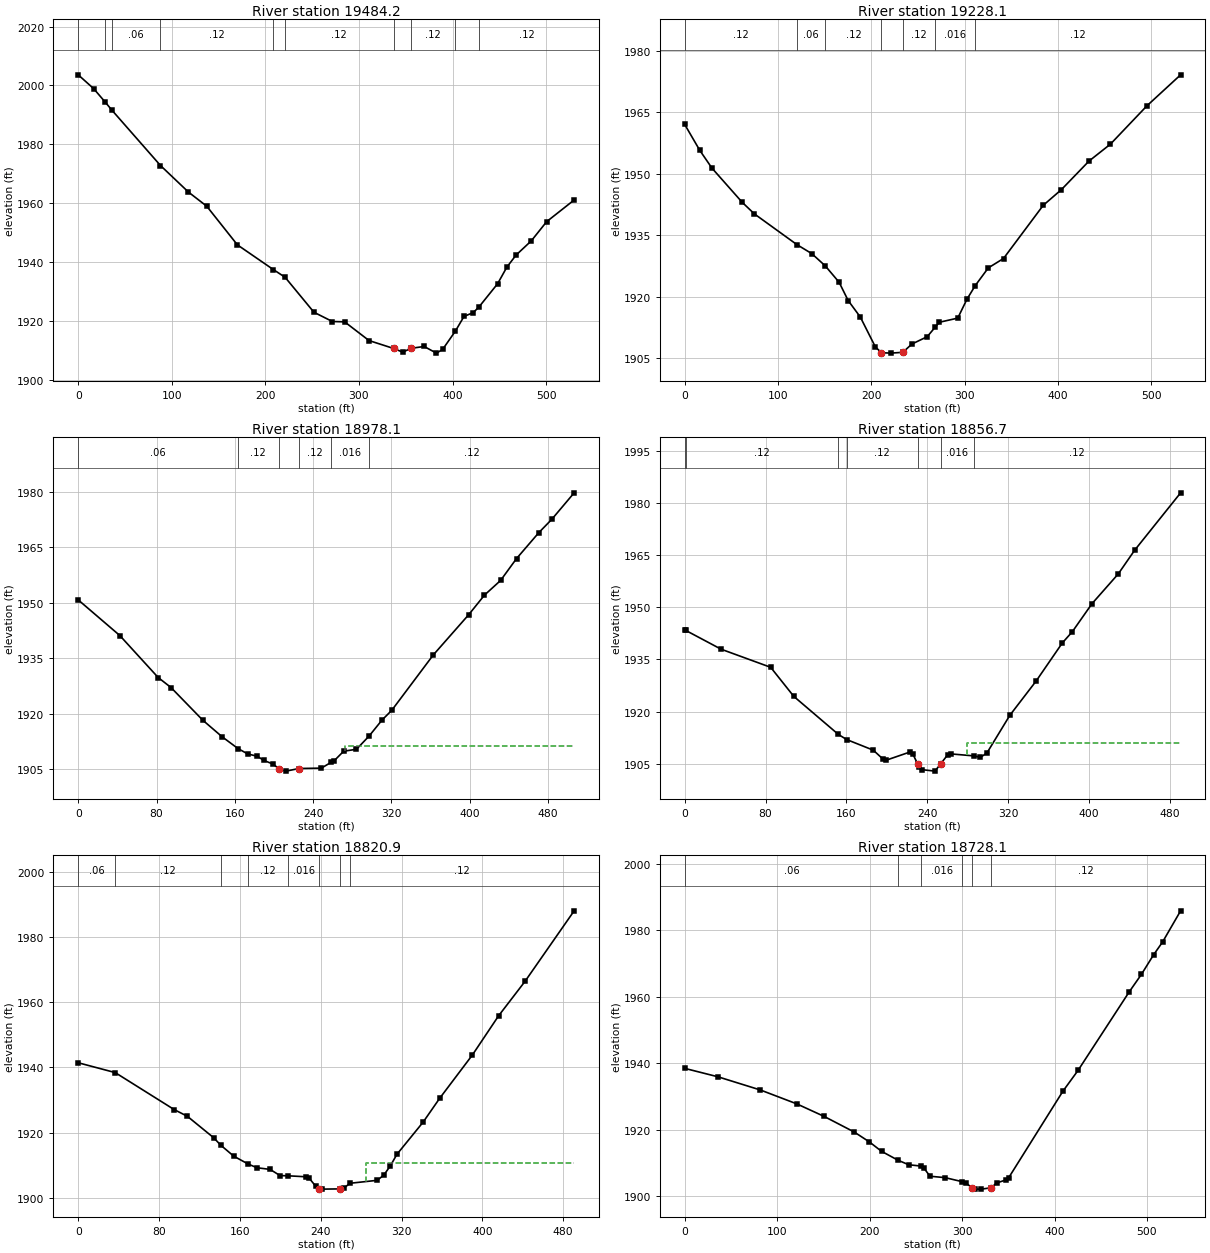
Type RM Length L Ch R = 1 ,19484.2 ,253.8,256.1,257.9
XS GIS Cut Line= 2
     2103765.721      194478.173     2103683.453      195001.801
#Sta/Elev= 30
       0 2003.58    16.4 1998.92   29.071994.233   35.781991.652   87.931972.745
   117.8 1963.72   137.4  1958.9   170.1 1945.78  208.491937.383  221.071934.765
   251.9 1922.87   271.6 1919.72   284.7 1919.61   310.8 1913.24     337 1910.56
   346.8 1909.31   355.8 1910.61   369.7 1911.23   382.8 1908.97   389.4 1910.21
  402.991916.412   412.3 1921.45   422.1 1922.74  428.091924.594   448.2 1932.56
   458.1 1938.21   467.9 1942.29   484.2 1947.14   500.6 1953.66     530 1961.03
#Mann= 10 ,-1 , 0
       0     .06       0   29.07     .12       0   35.78     .06       0
   87.93     .12       0  208.49     .06       0  221.07     .12       0
     337    .045       0   355.8     .12       0  402.99    .016       0
  428.09     .12       0
Bank Sta=337,355.8
XS Rating Curve= 0 ,0
Exp/Cntr=0.3,0.1

Type RM Length L Ch R = 1 ,19228.1 ,266.1,250,240.9
XS GIS Cut Line= 3
     2103576.419      194442.443     2103522.144      194659.544
     2103448.744      194958.059
#Sta/Elev= 30
       0 1962.08    16.2 1955.74    29.2 1951.42    61.6 1943.08    74.6 1940.26
  120.151932.766   136.2 1930.55   150.61927.567   165.4 1923.58   175.1 1919.12
   188.1  1915.1   204.3 1907.78   210.8  1906.4   220.5 1906.29   233.6 1906.48
   243.4 1908.51   259.8  1910.3   268.11912.566   272.8 1913.82   292.5 1914.83
   302.3 1919.42  311.29 1922.78   325.2 1927.08   341.5 1929.37     384 1942.33
   403.6 1946.19   433.1 1953.14     456 1957.26   495.2 1966.63   531.2 1974.17
#Mann= 7 ,-1 , 0
       0     .12       0  120.15     .06       0   150.6     .12       0
   210.8    .045       0   233.6     .12       0   268.1    .016       0
  311.29     .12       0
Bank Sta=210.8,233.6
XS Rating Curve= 0 ,0
Exp/Cntr=0.3,0.1

Type RM Length L Ch R = 1 ,18978.1 ,132.4,121.4,101.9
XS GIS Cut Line= 3
     2103181.242      194490.603     2103280.513      194685.722
     2103331.835      194968.873
#Sta/Elev= 30
       0  1950.8    42.5 1941.15    81.7 1929.78    94.8 1927.07   127.4 1918.19
     147 1913.74  163.181910.553   173.2 1909.08     183 1908.46   189.5 1907.35
   199.3 1906.31  204.791905.118   212.4 1904.43   225.5 1905.14   248.4 1905.24
  258.461906.824   261.4 1907.21   271.2 1909.82   284.3 1910.35  297.081913.897
   310.5 1918.29   320.3 1920.88   362.8  1935.9   398.8 1946.74   415.1  1952.1
   431.5 1956.05   447.8 1961.98   470.7 1969.04   483.8  1972.6   506.7 1979.79
#Mann= 6 ,-1 , 0
       0     .06       0  163.18     .12       0  204.79    .045       0
   225.5     .12       0  258.46    .016       0  297.08     .12       0
#XS Ineff= 2 , 0
                          273.07         1911.35
Permanent Ineff=
       F       F
Bank Sta=204.79,225.5
XS Rating Curve= 0 ,0
Exp/Cntr=0.3,0.1

Type RM Length L Ch R = 1 ,18856.7 ,37.8,35.8,40.2
XS GIS Cut Line= 4
     2103063.672      194540.636     2103159.158      194738.119
     2103199.305      194763.075     2103263.325      194977.919
#Sta/Elev= 30
       0 1943.46    1.061943.315      36 1937.92    85.1 1932.71     108 1924.35
  152.151913.407  160.321911.943   186.6  1908.9   196.4  1906.3   199.7 1906.04
   222.5 1908.32   225.7 1907.85   230.51904.961     232 1903.93   235.1 1903.28
   247.7 1902.87  253.191904.909   260.3 1907.57   263.5 1907.82  286.391907.245
   292.6 1906.82   299.1 1908.08   321.9 1918.96   347.8 1928.76   373.8 1939.74
   383.6 1942.93   403.1    1951   429.1 1959.56   445.3 1966.36   490.8 1982.86
#Mann= 7 ,-1 , 0
       0     .06       0    1.06     .12       0  152.15     .06       0
  160.32     .12       0   230.5    .045       0  253.19    .016       0
  286.39     .12       0
#XS Ineff= 2 , 0
                          279.67         1910.98
Permanent Ineff=
       F       F
Bank Sta=230.5,253.19
XS Rating Curve= 0 ,0
Exp/Cntr=0.3,0.1

Type RM Length L Ch R = 1 ,18820.9 ,81.4,92.8,97.2
XS GIS Cut Line= 4
     2103026.779      194555.827     2103122.266       194753.31
     2103162.413      194778.266     2103226.432       194993.11
#Sta/Elev= 30
       0 1941.41   36.611938.396      95 1927.05     108    1925   134.2 1918.38
  141.021916.145   153.9 1912.77  167.981910.389   176.8 1909.22   189.9 1908.71
   199.7 1906.82  207.781906.745   225.7 1906.44   228.8 1905.93   235.1 1903.52
   238.5 1902.81   241.4 1902.66   259.51902.734   263.5 1903.08   268.8 1904.45
   295.9 1905.36   302.4 1906.95   308.9  1909.8   315.4 1913.33   341.4 1923.23
   357.6 1930.46   390.1  1943.8   416.1 1955.84   442.1 1966.34   490.8    1988
#Mann= 8 ,-1 , 0
       0     .06       0   36.61     .12       0  141.02     .06       0
  167.98     .12       0  207.78    .016       0   238.5    .045       0
   259.5    .016       0   268.8     .12       0
#XS Ineff= 2 , 0
                          284.31         1910.64
Permanent Ineff=
       F       F
Bank Sta=238.5,259.5
XS Rating Curve= 0 ,0
Exp/Cntr=0.3,0.1

Type RM Length L Ch R = 1 ,18728.1 ,239.4,250,259
XS GIS Cut Line= 3
     2102904.037      194543.532     2103069.254      194818.666
     2103197.154      194992.136
#Sta/Elev= 30
       0 1938.44      36  1935.9    81.9 1931.93   121.2 1927.76   150.6 1924.01
   183.4 1919.28   199.8  1916.3   212.9 1913.48  230.931910.769   242.3 1909.44
  255.821909.027   258.7 1908.46   265.3 1905.98   281.6 1905.56  300.291904.334
   304.6 1903.87   310.41902.583   314.4 1902.11   320.9  1902.1   331.41902.502
   337.3 1903.93     347 1904.84   350.3 1905.47   409.1 1931.57   425.4  1937.8
   480.9  1961.5     494 1966.72   507.1 1972.58   516.9 1976.47   536.4 1985.84
#Mann= 6 ,-1 , 0
       0     .06       0  230.93     .12       0  255.82    .016       0
  300.29     .12       0   310.4    .045       0   331.4     .12       0
Bank Sta=310.4,331.4
XS Rating Curve= 0 ,0
Exp/Cntr=0.3,0.1

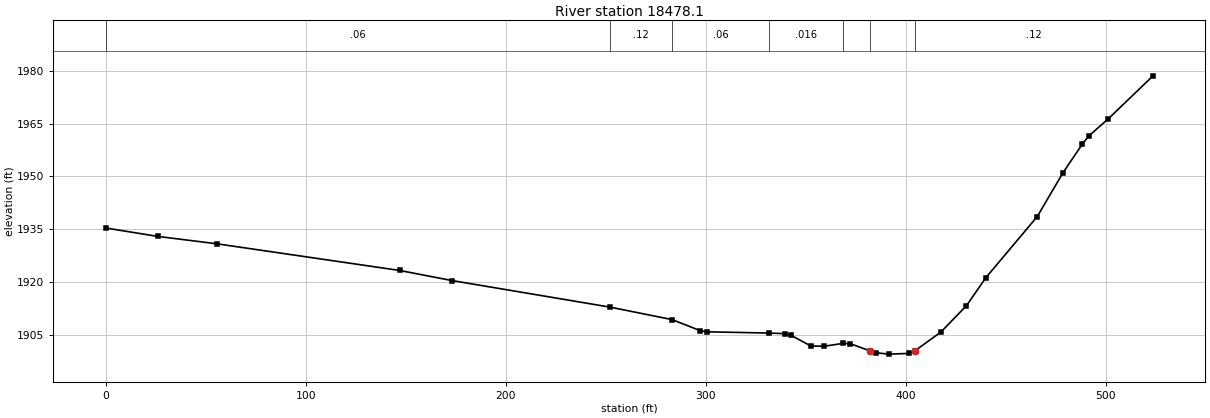
Type RM Length L Ch R = 1 ,18478.1 ,291.1,305.5,321.8
XS GIS Cut Line= 3
     2102815.959      194545.017     2102850.776      194935.288
     2102880.721      195063.715
#Sta/Elev= 30
       0 1935.34    26.1 1932.95    55.5 1930.86   146.9 1923.28     173 1920.42
   252.31912.839  283.221909.299   297.1  1906.2   300.4 1905.84  331.821905.475
   339.6 1905.32   342.8  1904.8   352.6  1901.8   359.2 1901.73  368.451902.522
   372.2 1902.47     382 1900.45   385.3 1899.86   391.8 1899.49   401.5 1899.69
   404.7 1900.47   417.6 1905.76   430.4 1913.27   440.1 1921.23   465.8 1938.61
   478.7  1951.1   488.3 1959.16   491.5 1961.48   501.2 1966.33   523.7 1978.61
#Mann= 7 ,-1 , 0
       0     .06       0   252.3     .12       0  283.22     .06       0
  331.82    .016       0  368.45     .12       0     382    .045       0
   404.7     .12       0
Bank Sta=382,404.7
XS Rating Curve= 0 ,0
Exp/Cntr=0.3,0.1