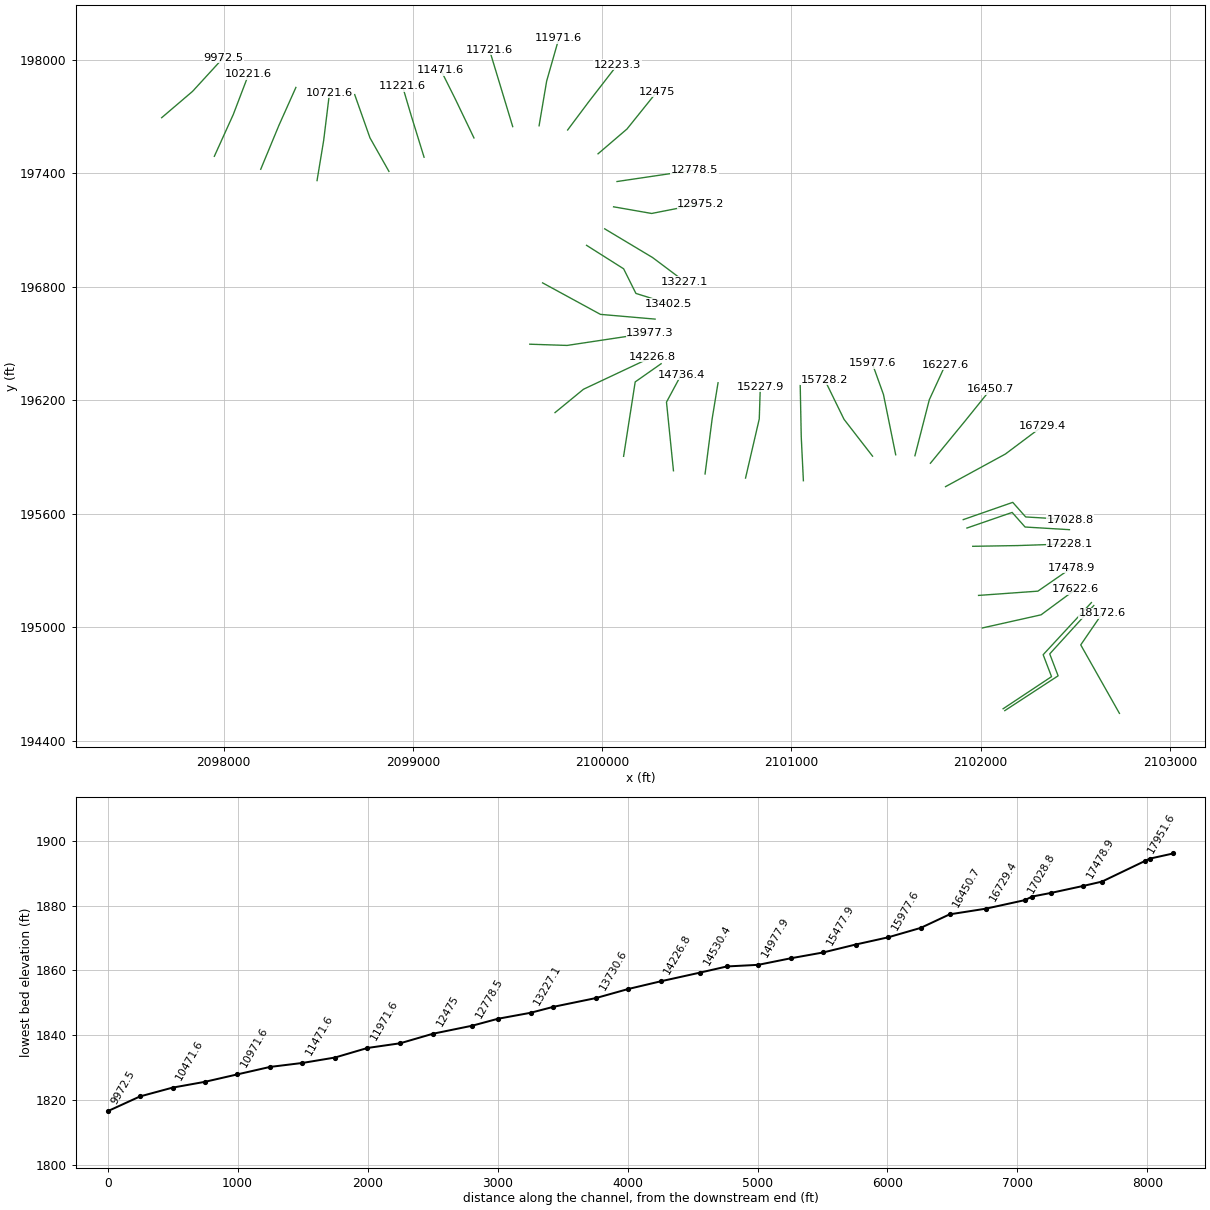
HEC-RAS study TRKYCK.prj: TRKYCK

--- TRKYCK.g01 (geometry) --- (continued)

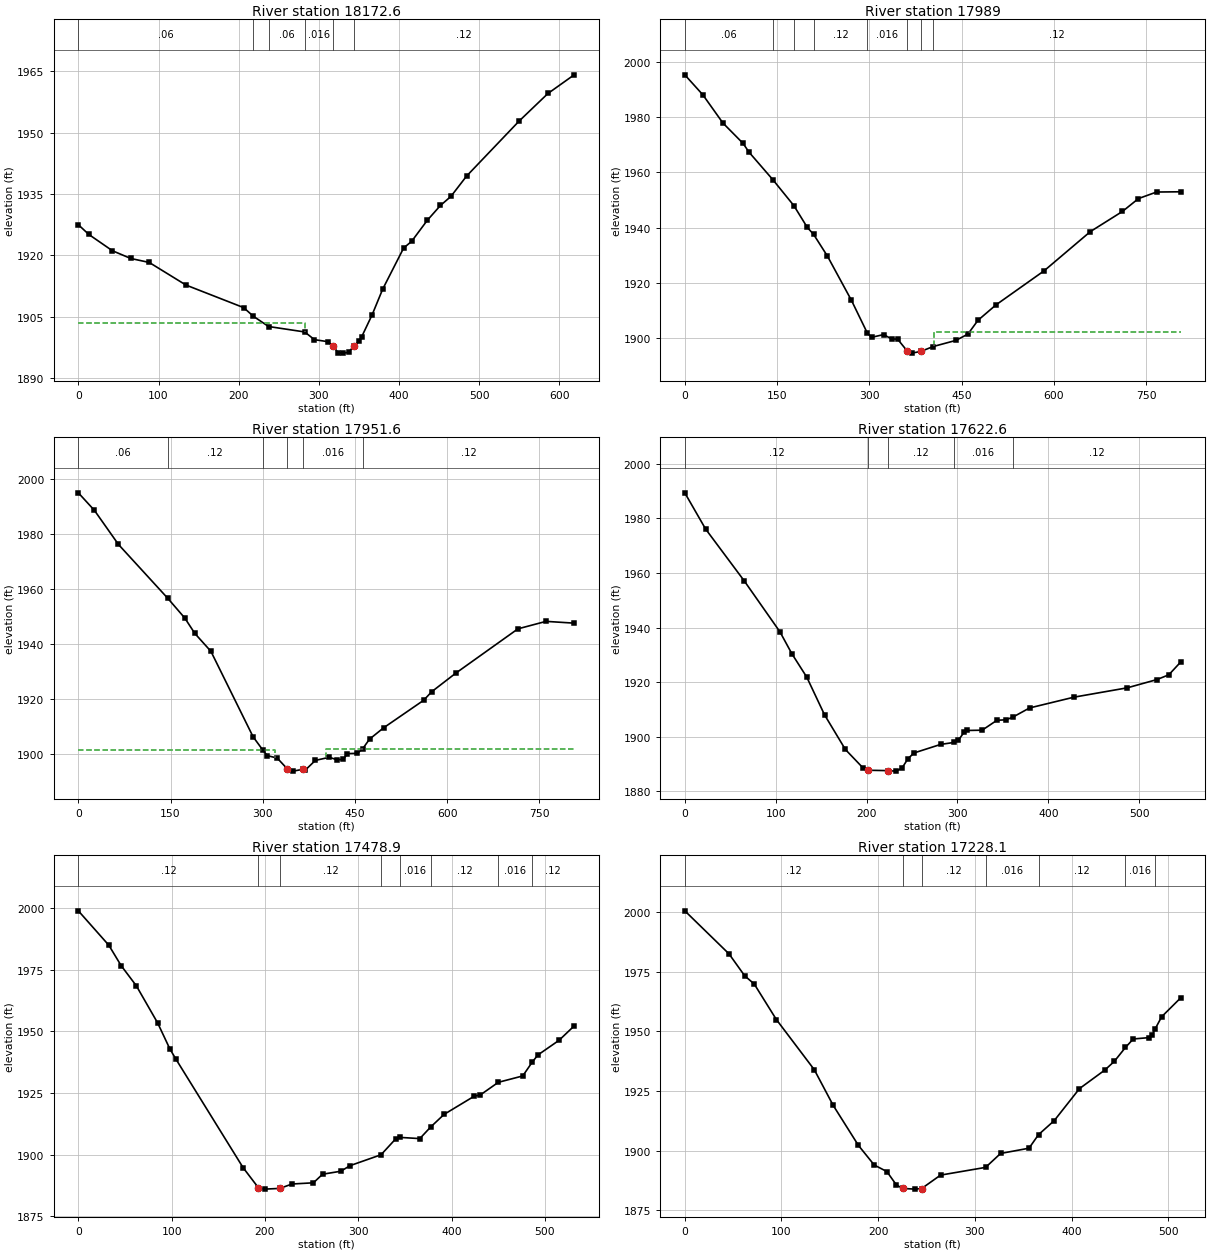
Type RM Length L Ch R = 1 ,18172.6 ,186.7,183.6,180.1
XS GIS Cut Line= 3
     2102733.296      194545.663     2102528.802      194907.459
     2102643.386      195074.805
#Sta/Elev= 30
       0 1927.49    13.1 1925.11    42.5 1921.13    65.4 1919.24    88.4 1918.27
   134.2 1912.75   206.2 1907.23  218.231905.127  237.271902.614  282.321901.285
   294.5  1899.4   310.9 1898.92   317.4 1897.88     324 1896.23   330.5 1896.11
     337  1896.3   343.6 1897.86   350.1 1898.97   353.4  1900.1   366.5 1905.51
   379.6 1911.75   405.8 1921.82   415.6  1923.4   435.2 1928.56   451.6 1932.19
   464.7 1934.41   484.3 1939.39   549.7 1952.81   585.7 1959.56   618.4 1964.12
#Mann= 6 ,-1 , 0
       0     .06       0  218.23     .12       0  237.27     .06       0
  282.32    .016       0   317.4    .045       0   343.6     .12       0
#XS Ineff= 2 , 0
          282.46 1903.51
Permanent Ineff=
       F       F
Bank Sta=317.4,343.6
XS Rating Curve= 0 ,0
Exp/Cntr=0.3,0.1

Type RM Length L Ch R = 1 ,17989   ,36,37.4,40.2
XS GIS Cut Line= 4
     2102127.669      194560.253     2102409.227      194744.048
     2102364.957      194859.933     2102597.818      195115.582
#Sta/Elev= 30
       0 1995.35    29.4 1988.09      62 1977.88    94.7 1970.51   104.5 1967.29
  143.241957.315  177.411947.913   199.1 1940.06  209.521937.479   231.8 1929.68
     271 1913.58  296.781901.745   303.6  1900.2   323.2  1901.2   336.2 1899.63
     346 1899.54  361.411895.295   368.9 1894.48   383.51895.081  403.79 1896.87
   440.7 1899.09   460.3 1901.38   476.6 1906.37     506 1911.98   584.3 1924.34
   659.3 1938.52   711.5 1945.83   737.6  1950.5     767 1952.87   806.1 1952.96
#Mann= 8 ,-1 , 0
       0     .06       0  143.24     .12       0  177.41     .06       0
  209.52     .12       0  296.78    .016       0  361.41    .045       0
   383.5    .016       0  403.79     .12       0
#XS Ineff= 2 , 0
                          405.57         1902.09
Permanent Ineff=
       F       F
Bank Sta=361.41,383.5
XS Rating Curve= 0 ,0
Exp/Cntr=0.3,0.1

Type RM Length L Ch R = 1 ,17951.6 ,369.1,328.9,286.8
XS GIS Cut Line= 4
     2102118.576      194569.933     2102374.505      194739.707
     2102330.234      194855.593     2102585.156      195130.914
#Sta/Elev= 30
       0 1995.11    26.1 1988.74    65.3 1976.29  145.481956.688   173.2 1949.48
   189.5 1943.89   215.6 1937.38   284.2 1906.26  299.821901.482   307.1  1899.4
   323.4  1898.5   339.9 1894.55   349.6 1893.74   365.9 1894.44   369.2 1894.13
   385.5 1897.65   408.3 1898.78   421.4 1897.81   431.2 1898.11   437.7 1900.12
     454 1900.23  462.391901.868   473.6 1905.39   496.4  1909.5   561.7 1919.56
   574.7 1922.66   613.9 1929.43     715 1945.57   760.7 1948.29   806.4 1947.64
#Mann= 6 ,-1 , 0
       0     .06       0  145.48     .12       0  299.82    .016       0
   339.9    .045       0   365.9    .016       0  462.39     .12       0
#XS Ineff= 2 , 0
          319.92 1901.49  402.48         1901.89
Permanent Ineff=
       F       F
Bank Sta=339.9,365.9
XS Rating Curve= 0 ,0
Exp/Cntr=0.3,0.1

Type RM Length L Ch R = 1 ,17622.6 ,146.9,143.7,140.5
XS GIS Cut Line= 3
     2102009.368      194996.994     2102319.167      195066.313
     2102502.742       195201.76
#Sta/Elev= 30
       0 1989.33    22.9 1976.07    65.5 1957.04   104.7 1938.42   117.8 1930.41
   134.2 1921.84   153.8 1908.01   176.7 1895.34   196.4 1888.48     2021887.724
   223.21887.595   232.4 1887.41   238.9 1888.49   245.5  1891.9     252 1894.04
   281.5 1897.19  296.241897.916   301.1 1898.76   307.6 1901.78   310.9  1902.3
   327.2  1902.4   343.5 1906.04   353.3  1906.2  360.651907.127   379.4 1910.55
   428.3  1914.5   486.9 1917.92   519.5 1920.94   532.6 1922.68   545.6 1927.34
#Mann= 5 ,-1 , 0
       0     .12       0     202    .045       0   223.2     .12       0
  296.24    .016       0  360.65     .12       0
Bank Sta=202,223.2
XS Rating Curve= 0 ,0
Exp/Cntr=0.3,0.1

Type RM Length L Ch R = 1 ,17478.9 ,251.9,250.8,249.8
XS GIS Cut Line= 3
     2101989.007      195168.838      2102302.24      195191.313
     2102480.966      195314.866
#Sta/Elev= 30
       0 1998.89    32.7 1984.93    45.8 1976.72    62.2 1968.47      85 1953.44
    98.1  1942.9   104.7 1938.69   176.6 1894.76     193 1886.62   199.5 1886.08
   215.9 1886.37     229 1888.16   251.9 1888.64   261.7 1892.12   281.3 1893.34
   291.1 1895.59  324.361900.012     340 1906.43  344.721907.051   365.9 1906.56
   377.51911.246   391.9 1916.37   424.3 1923.77   430.8 1924.27     4501929.371
   476.2 1931.96  486.341937.537   492.4 1940.45   515.1  1946.4   531.3 1952.23
#Mann= 8 ,-1 , 0
       0     .12       0     193    .045       0   215.9     .12       0
  324.36     .08       0  344.72    .016       0   377.5     .12       0
     450    .016       0  486.34     .12       0
Bank Sta=193,215.9
XS Rating Curve= 0 ,0
Exp/Cntr=0.3,0.1

Type RM Length L Ch R = 1 ,17228.1 ,168.9,141.4,116
XS GIS Cut Line= 3
     2101958.269      195428.268     2102196.634      195432.171
     2102470.847      195441.352
#Sta/Elev= 30
       0 2000.46    45.7 1982.44      62 1973.22    71.8 1969.82    94.7 1954.93
   133.9 1933.93   153.5 1918.96   179.6 1902.19   195.9 1894.01     209 1891.25
   218.8 1885.67   225.3 1884.18   238.4  1883.9   244.9 1884.13   264.5 1889.77
  311.091893.007   326.6 1898.84     356 1901.04  365.811906.704   382.1  1912.6
   408.2    1926   434.4 1933.77   444.2  1937.4  455.751943.241   463.8 1946.78
   480.1 1947.36   483.4 1948.41  486.531951.061   493.2  1956.1   512.8 1963.98
#Mann= 7 ,-1 , 0
       0     .12       0   225.3    .045       0   244.9     .12       0
  311.09    .016       0  365.81     .12       0  455.75    .016       0
  486.53     .12       0
Bank Sta=225.3,244.9
XS Rating Curve= 0 ,0
Exp/Cntr=0.3,0.1

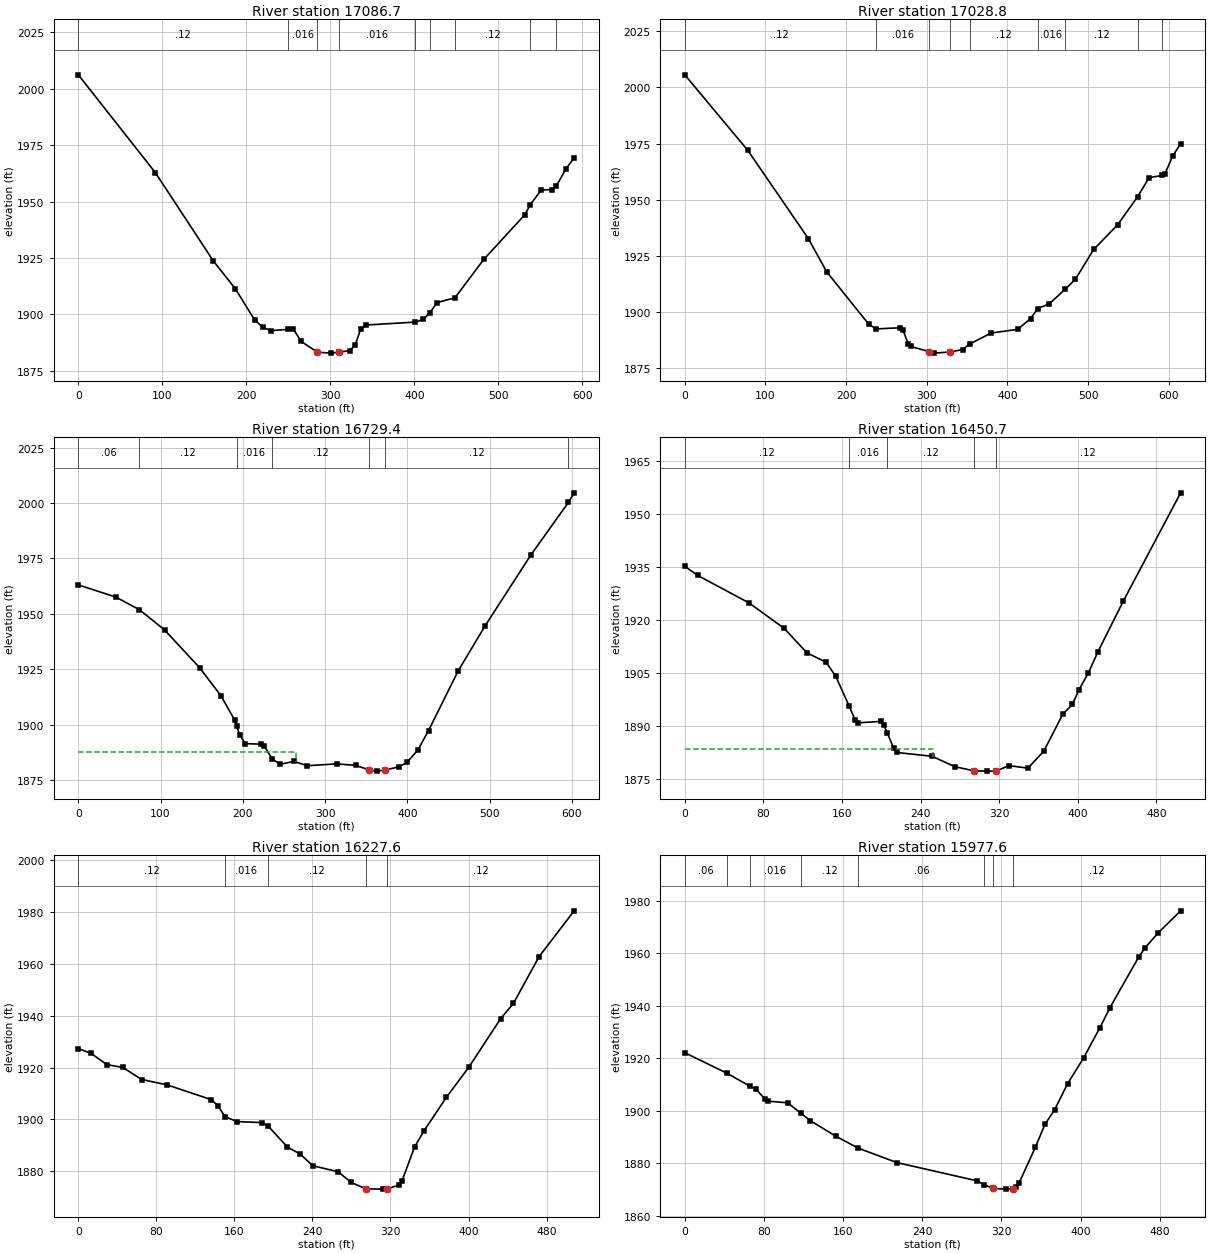
Type RM Length L Ch R = 1 ,17086.7 ,59.5,57.9,58
XS GIS Cut Line= 4
     2101927.604      195524.794     2102166.319      195607.259
     2102234.679       195530.22     2102469.054      195516.114
#Sta/Elev= 30
       0 2006.17    91.8 1962.77   160.7 1923.71     187 1911.31   209.9 1897.54
   219.8  1894.2   229.6 1892.78  249.971893.337   255.8 1893.65   265.4 1887.98
   284.7 1883.22   300.8 1882.81   310.5 1883.23   323.4 1883.96   329.8 1886.52
   336.2 1893.51   342.7 1895.28  400.821896.563     411 1897.77  418.391900.696
   427.3 1905.23   448.5 1907.36   482.7 1924.32   531.6 1944.13  538.231948.661
   551.2  1955.1   564.3 1955.32  568.931956.701   580.6 1964.49   590.4 1969.36
#Mann= 9 ,-1 , 0
       0     .12       0  249.97    .016       0   284.7    .045       0
   310.5    .016       0  400.82     .12       0  418.39    .016       0
   448.5     .12       0  538.23    .016       0  568.93     .12       0
Bank Sta=284.7,310.5
XS Rating Curve= 0 ,0
Exp/Cntr=0.3,0.1

Type RM Length L Ch R = 1 ,17028.8 ,257.7,299.4,338.3
XS GIS Cut Line= 4
     2101908.073      195569.282     2102169.575      195660.428
     2102237.934      195583.388     2102472.309      195569.282
#Sta/Elev= 30
       0  2005.6    78.2 1971.92   153.1 1932.72   175.9  1917.9   228.1 1894.52
  237.271892.476   267.2 1892.98   270.4 1892.11   276.9 1885.92   280.2 1884.65
   302.7 1882.38   309.1 1881.69   328.4 1882.18   344.5 1883.28  353.091885.748
   379.9 1890.64   412.5 1892.26   428.8 1897.06  437.371901.542   451.7 1903.58
  471.731910.177   484.3 1914.64   507.1 1927.93   536.5 1938.77  561.461951.403
   575.6  1959.8  592.151960.854   595.2 1961.51   604.9  1969.5   614.7 1974.93
#Mann= 9 ,-1 , 0
       0     .12       0  237.27    .016       0   302.7    .045       0
   328.4    .016       0  353.09     .12       0  437.37    .016       0
  471.73     .12       0  561.46    .016       0  592.15     .12       0
Bank Sta=302.7,328.4
XS Rating Curve= 0 ,0
Exp/Cntr=0.3,0.1

Type RM Length L Ch R = 1 ,16729.4 ,269.9,278.7,284.2
XS GIS Cut Line= 3
     2101814.377      195743.405     2102130.716      195915.774
     2102324.871      196061.385
#Sta/Elev= 30
       0 1963.05    45.8 1957.52   74.261951.858   104.8 1942.76   147.4 1925.73
   173.6 1912.96     190 1902.13  192.371899.486   196.5 1895.18     203 1891.47
   222.7 1891.21     226 1890.41  235.711884.582   245.6  1882.1     262 1883.49
   278.4  1881.5   314.4 1882.34   337.3 1881.65   353.7 1879.61   363.5 1879.06
   373.4 1879.64   389.8 1880.97   399.6 1883.01   412.7 1888.49   425.8 1897.33
   461.9  1924.3   494.7 1944.62   550.5 1976.68  595.862000.224   602.9 2004.57
#Mann= 7 ,-1 , 0
       0     .06       0   74.26     .12       0  192.37    .016       0
  235.71     .12       0   353.7    .045       0   373.4     .12       0
  595.86    .016       0
#XS Ineff= 2 , 0
          265.12 1887.57
Permanent Ineff=
       F       F
Bank Sta=353.7,373.4
XS Rating Curve= 0 ,0
Exp/Cntr=0.3,0.1

Type RM Length L Ch R = 1 ,16450.7 ,213.2,223.1,228.5
XS GIS Cut Line= 3
     2101734.518       195867.13     2101919.095      196092.039
     2102053.185      196258.358
#Sta/Elev= 30
       0 1935.13    13.1 1932.58    65.4 1924.81   101.3 1917.59   124.2 1910.73
   143.8 1908.04   153.6 1904.11     1671895.835   173.3 1891.77   176.5 1890.95
   199.4 1891.35   202.7 1890.22  205.951888.162   212.5 1883.82   215.8 1882.58
   251.7  1881.5   274.6 1878.58   294.2 1877.39   307.1 1877.31   316.8 1877.31
   329.8 1878.87   349.2 1878.14   365.4 1882.97   384.8 1893.44   394.5 1896.14
     401  1900.2   410.7 1905.04   420.4    1911   446.3 1925.34   504.6  1955.9
#Mann= 5 ,-1 , 0
       0     .12       0     167    .016       0  205.95     .12       0
   294.2    .045       0   316.8     .12       0
#XS Ineff= 2 , 0
          252.63 1883.65
Permanent Ineff=
       F       F
Bank Sta=294.2,316.8
XS Rating Curve= 0 ,0
Exp/Cntr=0.3,0.1

Type RM Length L Ch R = 1 ,16227.6 ,239.7,250,267.5
XS GIS Cut Line= 3
     2101652.747       195906.74     2101728.713      196202.542
     2101813.497      196386.854
#Sta/Elev= 30
       0 1927.34      13 1925.51    29.2 1921.16    45.5 1920.07      65 1915.41
      91 1913.34   136.5 1907.62     143 1905.28  150.291901.139   162.4 1899.18
   188.4 1898.79  194.151897.607   214.4 1889.35   227.4 1886.64   240.4 1882.15
   266.4 1879.81   279.4  1875.8   294.61873.223   311.9 1873.12   316.21873.184
   328.3 1874.65   331.6 1876.08   344.7 1889.39   354.5  1895.7   377.4 1908.57
   400.3 1920.15     433 1938.93   446.1 1944.82   472.3 1962.79   508.3 1980.49
#Mann= 5 ,-1 , 0
       0     .12       0  150.29    .016       0  194.15     .12       0
   294.6    .045       0   316.2     .12       0
Bank Sta=294.6,316.2
XS Rating Curve= 0 ,0
Exp/Cntr=0.3,0.1

Type RM Length L Ch R = 1 ,15977.6 ,239.3,249.4,251.6
XS GIS Cut Line= 3
     2101551.115      195911.952     2101486.437      196230.363
     2101426.715      196396.257
#Sta/Elev= 30
       0 1922.13   42.371914.384   66.081909.351    71.5 1908.44    81.2 1904.47
    84.5 1903.69     104 1903.07  116.971899.188   126.7 1896.34   152.7 1890.35
  175.481885.786   214.4 1880.32   295.7 1873.36  302.811871.863   311.9 1870.47
   324.9 1870.22   331.4 1870.37   334.7 1870.87     338 1872.65   354.3 1886.11
   364.1 1894.92   373.9 1900.48     387 1910.39   403.3 1920.26   419.6 1931.65
   429.4 1939.04   458.8 1958.56   465.3 1962.08   478.4 1967.73   501.2 1976.15
#Mann= 8 ,-1 , 0
       0     .06       0   42.37     .12       0   66.08    .016       0
  116.97     .12       0  175.48     .06       0  302.81     .12       0
   311.9    .045       0   331.4     .12       0
Bank Sta=311.9,331.4
XS Rating Curve= 0 ,0
Exp/Cntr=0.3,0.1

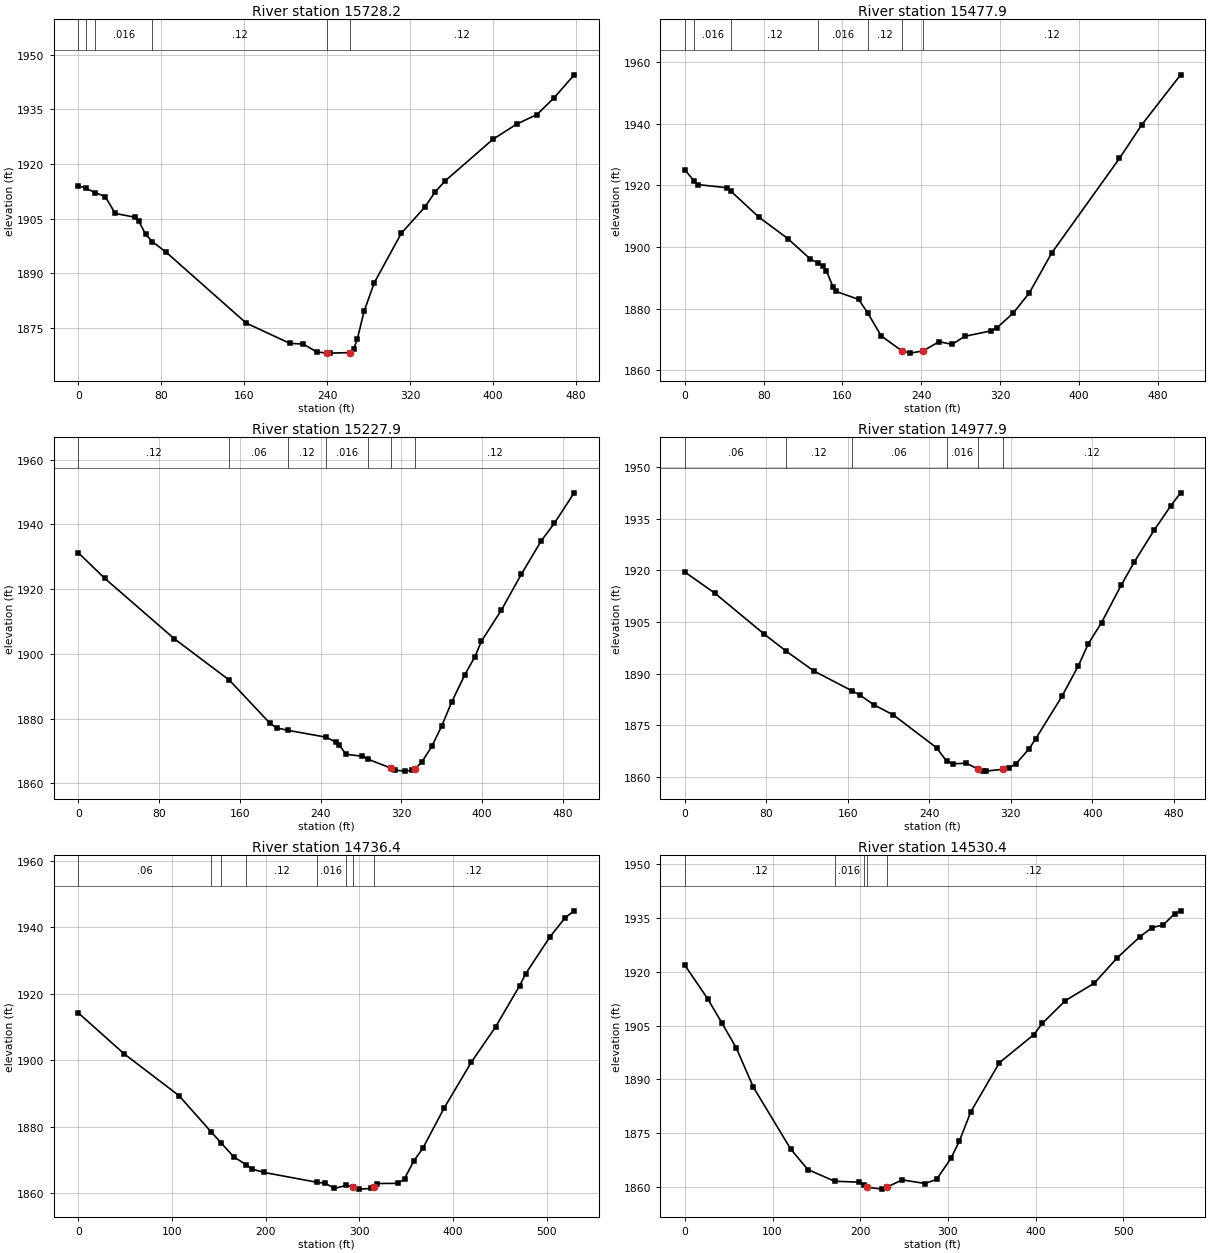
Type RM Length L Ch R = 1 ,15728.2 ,263.3,250.3,240.2
XS GIS Cut Line= 3
     2101428.812      195904.551     2101278.005      196099.131
     2101176.034      196307.693
#Sta/Elev= 30
       0 1914.04    6.991913.376   16.531912.095    25.9 1911.07    35.6 1906.41
    55.1 1905.34    58.3  1904.3    64.8 1900.73   71.361898.667    84.2 1895.87
     162 1876.25   204.1 1870.68     217  1870.5     230 1868.31   239.7 1868.02
   242.9    1868   262.5 1868.16   265.8 1869.27   269.1 1871.83   275.6 1879.45
   285.4 1887.32   311.6 1900.97   334.5 1908.23   344.3 1912.38   354.1 1915.42
   399.9 1926.79   422.8 1930.97   442.4  1933.6   458.7 1938.13   478.3 1944.53
#Mann= 6 ,-1 , 0
       0     .06       0    6.99     .12       0   16.53    .016       0
   71.36     .12       0   239.7    .045       0   262.5     .12       0
Bank Sta=239.7,262.5
XS Rating Curve= 0 ,0
Exp/Cntr=0.3,0.1

Type RM Length L Ch R = 1 ,15477.9 ,256,250,248.3
XS GIS Cut Line= 3
     2101063.351      195774.639     2101052.051      196006.309
     2101046.646      196277.462
#Sta/Elev= 30
       0 1925.08    9.241921.439    13.1 1920.23    42.5 1919.22   47.071917.998
    75.1 1909.69   104.5 1902.72   127.4 1896.07  135.341894.776   140.5 1893.84
   143.7 1892.29   150.3 1887.11   153.5 1885.57   176.4 1882.98  185.421878.711
   199.3 1871.15  220.131866.325   228.7 1865.55   241.8 1866.26   258.1 1869.26
   271.2 1868.39   284.2 1871.01   310.4 1872.74   316.9  1873.8   333.2 1878.51
   349.6 1885.06   372.4 1898.05   441.1 1928.72   463.9 1939.69   503.2 1955.84
#Mann= 7 ,-1 , 0
       0     .12       0    9.24    .016       0   47.07     .12       0
  135.34    .016       0  185.42     .12       0  220.13    .045       0
   241.8     .12       0
Bank Sta=220.13,241.8
XS Rating Curve= 0 ,0
Exp/Cntr=0.3,0.1

Type RM Length L Ch R = 1 ,15227.9 ,247.3,250,246.9
XS GIS Cut Line= 3
     2100757.681      195788.807     2100830.211      196101.256
     2100835.789      196271.659
#Sta/Elev= 30
       0 1931.24    26.2 1923.32    94.9 1904.71  149.621891.864   189.8 1878.56
   196.4 1877.11   208.11876.334  245.541874.235   255.3 1872.68   258.6 1871.79
   265.1 1868.96   281.5 1868.34  287.351867.376   309.91864.667   314.2 1864.03
     324 1863.75   330.6 1863.96   333.9 1864.55   340.4 1866.62   350.3 1871.44
   360.1 1877.79   369.9 1885.14     383 1893.59   392.9 1899.13   399.4 1903.93
   419.1 1913.52   438.8 1924.56   458.5 1934.86   471.6 1940.37   491.2 1949.76
#Mann= 7 ,-1 , 0
       0     .12       0  149.62     .06       0   208.1     .12       0
  245.54    .016       0  287.35     .12       0   309.9    .045       0
   333.9     .12       0
Bank Sta=309.9,333.9
XS Rating Curve= 0 ,0
Exp/Cntr=0.3,0.1

Type RM Length L Ch R = 1 ,14977.9 ,236.4,241.5,247.1
XS GIS Cut Line= 3
     2100543.791      195810.376     2100581.568      196103.792
     2100612.386      196292.164
#Sta/Elev= 30
       0 1919.52    29.3 1913.41      78 1901.48   99.551896.535   126.8 1890.77
  163.881885.074   172.3 1883.72   185.3 1881.03   204.8 1878.02   247.1 1868.53
  256.981864.617   263.3 1863.87   276.3 1864.02  287.911862.326   292.6 1861.75
   295.8 1861.73     312 1862.27   318.5 1862.76     325 1863.83   337.9 1868.18
   344.4 1871.11   370.2 1883.43   386.4 1892.36   396.1 1898.69   409.1 1904.85
   428.5 1915.77   441.4 1922.51   460.8  1931.7     477 1938.71   486.7 1942.49
#Mann= 6 ,-1 , 0
       0     .06       0   99.55     .12       0  163.88     .06       0
  256.98    .016       0  287.91    .045       0     312     .12       0
Bank Sta=287.91,312
XS Rating Curve= 0 ,0
Exp/Cntr=0.3,0.1

Type RM Length L Ch R = 1 ,14736.4 ,211.3,206,200
XS GIS Cut Line= 3
     2100376.871      195827.208        2100340.      196190.011
     2100418.075      196335.182
#Sta/Elev= 30
       0 1914.26    48.8 1901.98   107.4 1889.39  142.211878.337  152.881875.017
   166.1 1870.92  179.18 1868.58   185.6 1867.26   198.6 1866.24  254.881863.287
   263.7 1863.01   273.5 1861.43  285.62 1862.33     293 1861.95   299.6 1861.23
   312.6 1861.42   315.8 1861.98   319.1 1862.91   341.9 1862.98   348.4  1864.4
   358.2  1869.7   367.9 1873.53   390.5 1885.56   419.6  1899.4   445.5 1910.02
   471.3 1922.46   477.8 1926.09   503.6 1937.13   519.8  1942.9   529.5 1944.99
#Mann= 8 ,-1 , 0
       0     .06       0  142.21     .12       0  152.88     .06       0
  179.18     .12       0  254.88    .016       0  285.62     .12       0
     293    .045       0   315.8     .12       0
Bank Sta=293,315.8
XS Rating Curve= 0 ,0
Exp/Cntr=0.3,0.1

Type RM Length L Ch R = 1 ,14530.4 ,321.3,303.6,280.3
XS GIS Cut Line= 3
     2100113.372      195903.674     2100174.635      196296.782
      2100311.65      196392.804
#Sta/Elev= 30
       0 1921.85    26.1 1912.46    42.4 1905.67    58.7 1898.73    78.3 1887.72
   120.7 1870.52   140.2  1864.8  170.751861.535   198.9 1861.27  203.781860.519
  207.171859.892     225 1859.33  230.011859.834   247.8 1861.91   273.9  1860.9
     287 1862.05   303.3 1867.89   313.1 1872.82   326.1 1880.96   358.7 1894.63
   397.8 1902.44   407.7 1905.64   433.9 1911.96   466.8 1916.82     493 1923.93
   519.2 1929.84   532.4 1932.29   545.5  1933.1   558.6 1936.26   565.2 1937.01
#Mann= 5 ,-1 , 0
       0     .12       0  170.75    .016       0  203.78     .12       0
  207.17    .045       0  230.01     .12       0
Bank Sta=207.17,230.01
XS Rating Curve= 0 ,0
Exp/Cntr=0.3,0.1

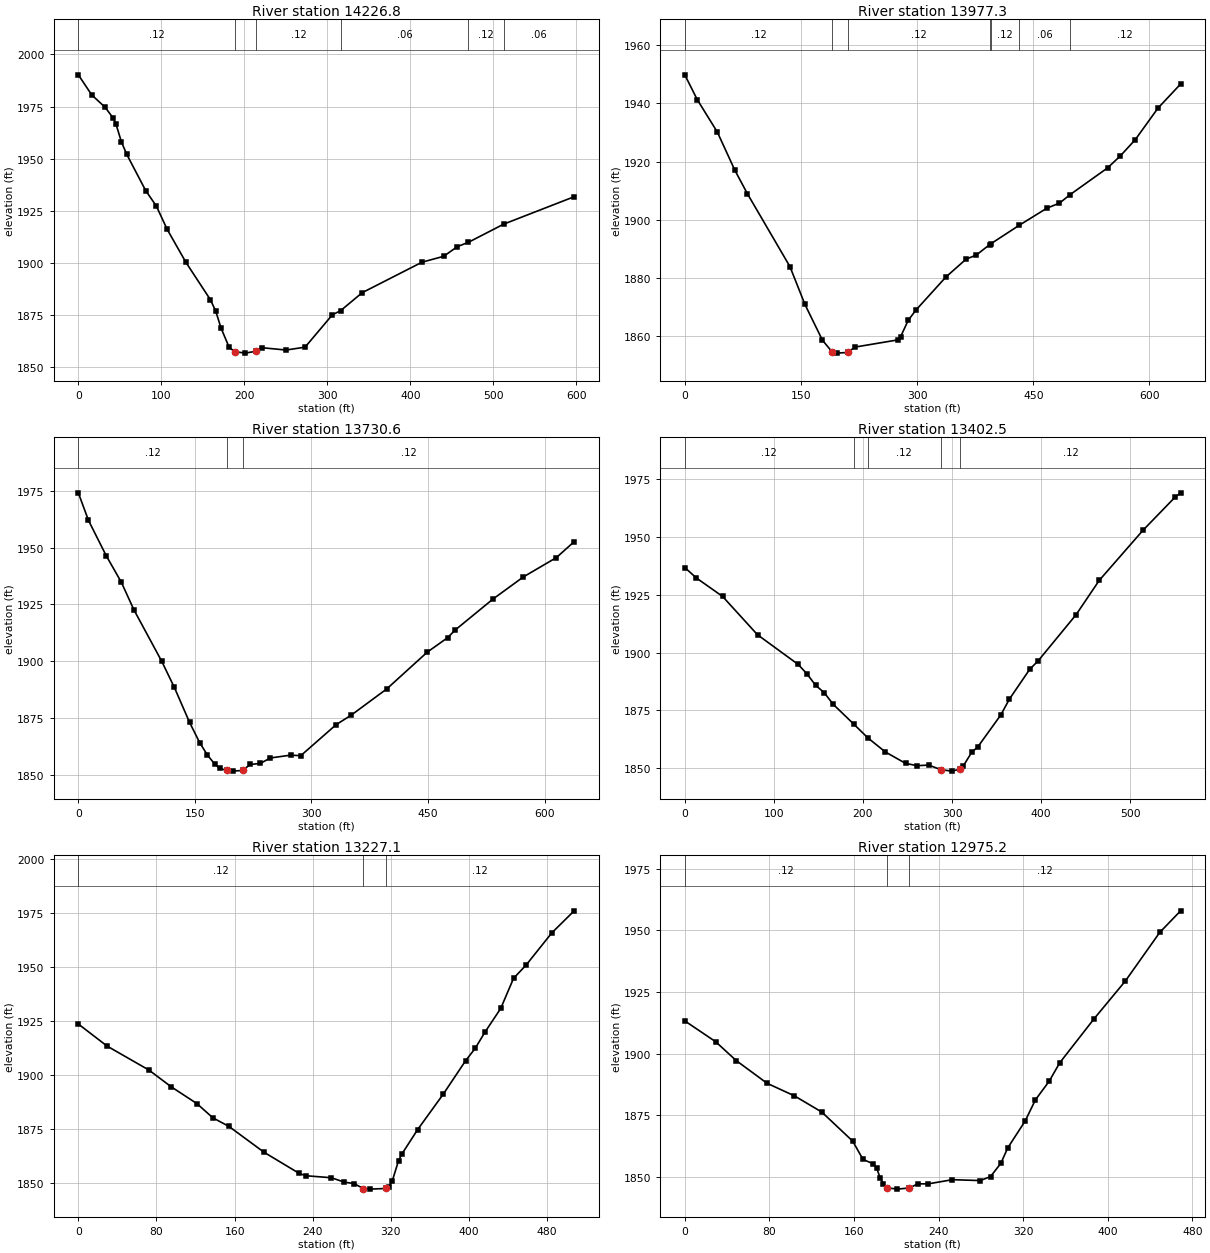
Type RM Length L Ch R = 1 ,14226.8 ,263.8,249.5,242.3
XS GIS Cut Line= 3
     2099751.034      196134.575     2099901.441      196258.011
     2100265.769      196429.508
#Sta/Elev= 30
       0 1990.22    16.2 1980.55    32.4 1974.58    42.2 1969.34    45.4 1966.53
    51.9 1958.01    58.4 1951.98    81.1 1934.68      94  1927.2     107 1916.04
   129.7 1900.14   158.9 1882.38   165.4 1876.92   171.9 1868.64   181.6  1859.5
   188.1 1857.38   201.1 1856.64   214.2 1857.58   220.8 1859.26   250.2 1858.12
   273.1 1859.51   305.9    1875  316.041877.066   341.9 1885.65   413.9 1900.28
   440.1 1903.12   456.5 1907.76  469.871909.839  512.261918.543   597.2 1931.71
#Mann= 6 ,-1 , 0
       0     .12       0   188.1    .045       0   214.2     .12       0
  316.04     .06       0  469.87     .12       0  512.26     .06       0
Bank Sta=188.1,214.2
XS Rating Curve= 0 ,0
Exp/Cntr=0.3,0.1

Type RM Length L Ch R = 1 ,13977.3 ,256.9,246.7,231.1
XS GIS Cut Line= 3
     2099617.674      196495.922     2099814.689      196489.473
      2100252.86       196555.52
#Sta/Elev= 30
       0 1949.79    16.2 1941.22      42 1930.15    64.6 1917.06    80.8 1908.99
   135.7    1884   155.1    1871   177.7 1858.71   190.7 1854.54   197.1 1854.27
   210.2 1854.51   219.9 1856.35   275.3 1858.82   278.6 1859.88   288.4 1865.49
   298.1 1868.95   337.2 1880.41   363.3 1886.55   376.3 1887.91  393.621891.516
  395.331891.826  431.941898.178   467.6 1904.03   483.8 1905.76  497.461908.658
   545.8 1917.83     562 1921.86   581.6 1927.52   610.9 1938.34   640.2 1946.64
#Mann= 7 ,-1 , 0
       0     .12       0   190.7    .045       0   210.2     .12       0
  393.62     .06       0  395.33     .12       0  431.94     .06       0
  497.46     .12       0
Bank Sta=190.7,210.2
XS Rating Curve= 0 ,0
Exp/Cntr=0.3,0.1

Type RM Length L Ch R = 1 ,13730.6 ,341.3,328,313.5
XS GIS Cut Line= 3
     2099685.433       196819.94     2099991.042      196653.553
     2100280.027      196628.529
#Sta/Elev= 30
       0 1974.23      13 1962.11    35.8 1946.55    55.3 1934.82    71.5 1922.64
   107.3 1899.94   123.6 1888.38   143.1 1873.01   156.1 1864.08   165.8 1858.73
   175.6 1854.54   182.1 1852.66   191.41851.789   198.4 1851.49   211.4 1851.79
   221.1 1854.42   234.2  1854.9   247.2  1857.3   273.2 1858.54   286.2 1858.29
   331.7 1871.98   351.2 1876.19   396.8 1887.73     449 1903.97   475.1 1910.32
   484.8 1913.69   533.7 1927.42   572.8 1937.17   615.2 1945.68     638 1952.69
#Mann= 3 ,-1 , 0
       0     .12       0   191.4    .045       0   211.4     .12       0
Bank Sta=191.4,211.4
XS Rating Curve= 0 ,0
Exp/Cntr=0.3,0.1

Type RM Length L Ch R = 1 ,13402.5 ,163.2,175.4,185.7
XS GIS Cut Line= 4
     2099917.665       197018.26     2100113.437      196894.438
     2100178.542       196764.23     2100349.572      196710.543
#Sta/Elev= 30
       0 1936.69      13 1932.19    42.4 1924.22    81.6 1907.67   127.2 1894.87
     137 1890.84   146.8 1885.86   156.6 1882.61   166.4 1877.69  189.531869.121
  205.621863.083   225.1 1857.06   247.8 1852.13   260.8 1851.13   273.7 1851.39
   287.11849.449   299.6 1848.78   309.21849.638   312.5 1850.97   322.2 1857.02
   328.7 1859.17   354.6 1872.99   364.3 1879.87     387 1892.68   396.8  1896.5
   439.2 1916.35   465.2 1931.17   514.1 1952.72     550 1966.98   556.5 1968.96
#Mann= 5 ,-1 , 0
       0     .12       0  189.53     .06       0  205.62     .12       0
   287.1    .045       0   309.2     .12       0
Bank Sta=287.1,309.2
XS Rating Curve= 0 ,0
Exp/Cntr=0.3,0.1

Type RM Length L Ch R = 1 ,13227.1 ,242.3,251.9,270.7
XS GIS Cut Line= 3
     2100013.353      197105.504     2100266.563      196953.754
     2100436.578      196826.241
#Sta/Elev= 30
       0 1923.53    29.5 1913.28    72.2  1902.2    95.1 1894.41   121.4 1886.62
   137.8    1880   154.2 1876.04   190.2 1864.03   226.3  1854.2   232.9 1853.16
   259.1 1852.22   272.2  1850.2   282.1 1849.54   291.9 1847.22   298.5 1846.94
   314.8 1847.24   318.1 1848.15   321.4 1850.62   327.9 1860.22   331.2 1863.16
   347.5  1874.6   373.7 1891.02   396.6 1906.56   406.4 1912.26   416.2 1919.65
   432.5 1930.76   445.6 1944.69   458.7    1951   484.8  1965.8   507.7 1976.04
#Mann= 3 ,-1 , 0
       0     .12       0   291.9    .045       0   314.8     .12       0
Bank Sta=291.9,314.8
XS Rating Curve= 0 ,0
Exp/Cntr=0.3,0.1

Type RM Length L Ch R = 1 ,12975.2 ,189.5,196.7,195.4
XS GIS Cut Line= 3
     2100060.425      197221.756     2100261.488      197186.656
      2100521.29      197237.668
#Sta/Elev= 30
       0 1913.29    29.2 1904.84    48.6 1897.21    77.8    1888   103.7  1882.9
   129.6 1876.32   158.8 1864.53   168.5 1857.15   178.2 1855.33   181.4 1853.61
   184.7 1849.74   187.9 1847.07   191.1 1845.63   200.9 1845.09  212.391845.565
   220.4 1847.24   230.2 1847.22   253.1 1848.92   279.3 1848.56   289.1 1850.16
   298.9 1855.56   305.4  1861.8   321.8 1872.65   331.6  1881.3   344.7  1888.9
   354.5 1896.26   387.2 1914.23   416.6 1929.44   449.2 1949.18   468.9 1957.91
#Mann= 3 ,-1 , 0
       0     .12       0   191.1    .045       0  212.39     .12       0
Bank Sta=191.1,212.39
XS Rating Curve= 0 ,0
Exp/Cntr=0.3,0.1

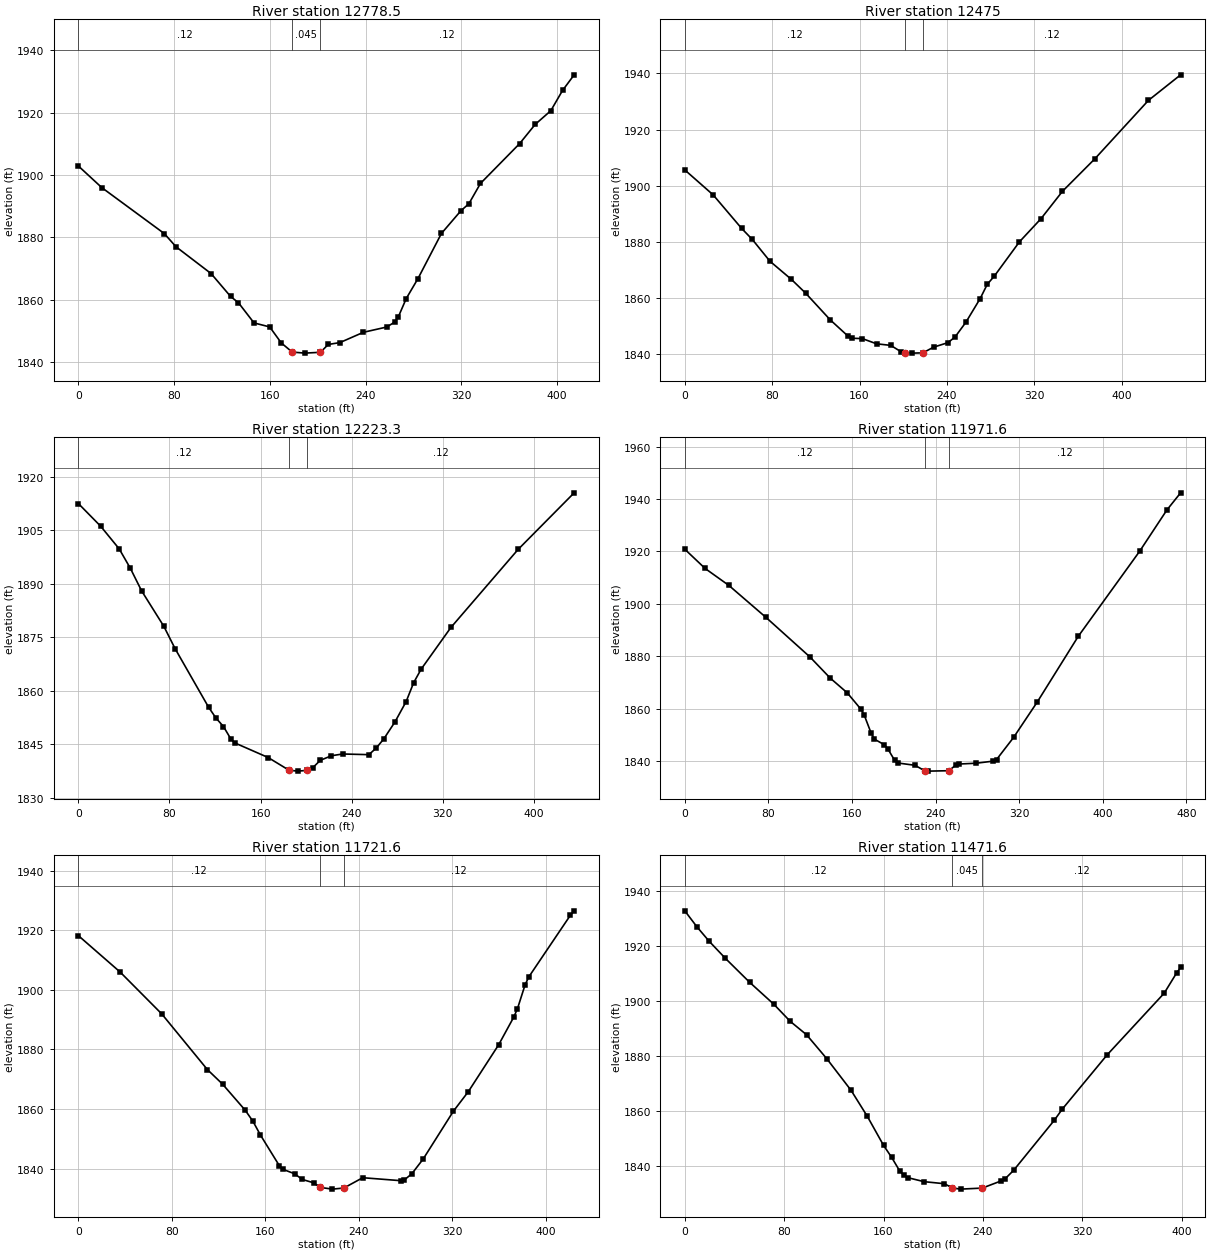
Type RM Length L Ch R = 1 ,12778.5 ,289.2,303.6,320.2
XS GIS Cut Line= 2
     2100078.678      197355.406     2100488.566       197416.01
#Sta/Elev= 30
       0 1902.89    19.6 1895.96    71.8 1881.25    81.6 1877.02   110.9 1868.44
   127.2 1861.12   133.8 1859.09   146.8 1852.63   159.9 1851.35   169.6 1846.22
  178.681843.304   189.2 1842.96   202.3 1843.23   208.8 1845.73   218.6 1846.34
   238.2 1849.63   257.7 1851.32   264.3 1852.89   267.5 1854.68     274 1860.44
   283.8 1866.83   303.4 1881.28   319.7 1888.56   326.3 1890.77     336 1897.29
   368.7 1910.03   381.7 1916.18   394.8 1920.59   404.6 1927.07   414.3 1932.07
#Mann= 3 ,-1 , 0
       0     .12       0  178.68    .045       0   202.3     .12       0
Bank Sta=178.68,202.3
XS Rating Curve= 0 ,0
Exp/Cntr=0.3,0.1

Type RM Length L Ch R = 1 ,12475   ,248.1,251.7,251.8
XS GIS Cut Line= 3
     2099978.237      197501.833     2100131.424      197632.909
     2100289.572      197829.725
#Sta/Elev= 30
       0 1905.67      26 1896.78      52 1884.88    61.8 1880.94      78 1873.17
    97.6 1866.72   110.6 1861.84   133.3 1852.27   149.6 1846.48   152.8 1845.77
   162.6 1845.64   175.6 1843.79   188.6 1843.23   198.4 1840.88   201.6 1840.61
   208.2 1840.47     218 1840.57   227.8 1842.58     241  1844.2   247.5 1846.21
   257.4 1851.44   270.5 1859.88     277 1864.95   283.6 1867.95   306.5 1880.09
   326.2 1888.31   345.9 1898.07   375.4 1909.57   424.6 1930.42   454.1 1939.52
#Mann= 3 ,-1 , 0
       0     .12       0   201.6    .045       0     218     .12       0
Bank Sta=201.6,218
XS Rating Curve= 0 ,0
Exp/Cntr=0.3,0.1

Type RM Length L Ch R = 1 ,12223.3 ,240.5,251.7,259.9
XS GIS Cut Line= 3
     2099817.735       197627.66     2099929.193      197776.744
     2100081.814      197973.546
#Sta/Elev= 30
       0 1912.47    19.6 1906.11    35.9 1899.75    45.7  1894.3    55.5 1888.03
    75.1 1878.05    84.9 1871.84   114.3 1855.44   120.8  1852.4   127.4 1850.01
   133.9 1846.52   137.2 1845.45   166.6 1841.34  184.961837.781   192.7 1837.53
  200.751837.738   205.8  1838.5   212.4 1840.56   222.2 1841.84     232 1842.33
     255 1842.14   261.5    1844   268.1 1846.55   277.9  1851.3   287.7 1856.99
   294.3 1862.27   300.8 1866.04     327 1877.75     386 1899.61   435.2 1915.46
#Mann= 3 ,-1 , 0
       0     .12       0  184.96    .045       0  200.75     .12       0
Bank Sta=184.96,200.75
XS Rating Curve= 0 ,0
Exp/Cntr=0.3,0.1

Type RM Length L Ch R = 1 ,11971.6 ,239.2,250,262.6
XS GIS Cut Line= 3
     2099666.813      197649.864     2099706.842      197886.067
     2099771.341      198111.818
#Sta/Elev= 30
       0 1920.84    19.4 1913.51    42.1 1907.04    77.7 1894.79   119.8 1879.67
   139.2 1871.59   155.4    1866   168.4 1859.78   171.6 1857.56   178.1 1850.78
   181.3 1848.32     191 1846.14   194.2 1844.61   200.7 1840.26     204 1839.18
   220.2 1838.31   229.9 1836.14   233.1 1836.08   252.6 1836.24   259.1 1838.32
   262.4 1838.79   278.7  1839.1     295 1839.89   298.3 1840.51   314.6 1848.96
   337.4 1862.59   376.5  1887.6   435.2 1920.07   461.3 1935.86   474.4 1942.39
#Mann= 3 ,-1 , 0
       0     .12       0   229.9    .045       0   252.6     .12       0
Bank Sta=229.9,252.6
XS Rating Curve= 0 ,0
Exp/Cntr=0.3,0.1

Type RM Length L Ch R = 1 ,11721.6 ,246.5,250,253.7
XS GIS Cut Line= 3
     2099527.473      197645.425     2099463.447      197856.713
     2099404.434      198051.459
#Sta/Elev= 30
       0 1918.18    35.7 1905.98    71.4  1891.9   110.4 1873.25   123.4 1868.36
   142.9 1859.55   149.4  1855.9   155.8  1851.3   172.1 1840.94   175.3 1839.74
   185.1 1838.28   191.6 1836.38   201.3 1835.26  206.771833.715   217.5 1833.13
   227.2  1833.5   243.4 1836.96   275.7 1835.97   278.9 1836.19   285.4 1838.29
   295.1 1843.23   320.9 1859.24   333.8 1865.87   359.7 1881.56   372.6 1890.83
   375.8 1893.68   382.3 1901.66   385.5 1904.33     421 1924.96   424.3 1926.49
#Mann= 3 ,-1 , 0
       0     .12       0  206.77    .045       0   227.2     .12       0
Bank Sta=206.77,227.2
XS Rating Curve= 0 ,0
Exp/Cntr=0.3,0.1

Type RM Length L Ch R = 1 ,11471.6 ,253.3,250,246
XS GIS Cut Line= 3
     2099322.691      197585.697     2099225.215      197788.811
     2099147.466       197944.31
#Sta/Elev= 30
       0 1932.79     9.8 1926.94    19.6 1921.72    32.6 1915.52    52.2 1906.77
    71.8 1898.72    84.9 1892.54      98 1887.68   114.3 1878.96   133.9 1867.41
   146.9    1858     160 1847.41   166.5 1843.05     173  1838.1   176.3 1836.53
   179.6 1835.63   192.6 1834.18     209 1833.43   215.5 1831.88     222 1831.46
   239.5 1831.84   254.8 1834.47   258.1 1835.32   264.7 1838.28   297.5 1856.54
     304 1860.64   340.1 1880.38     386 1902.82   395.9 1910.12   399.2 1912.17
#Mann= 3 ,-1 , 0
       0     .12       0   215.5    .045       0   239.5     .12       0
Bank Sta=215.5,239.5
XS Rating Curve= 0 ,0
Exp/Cntr=0.3,0.1

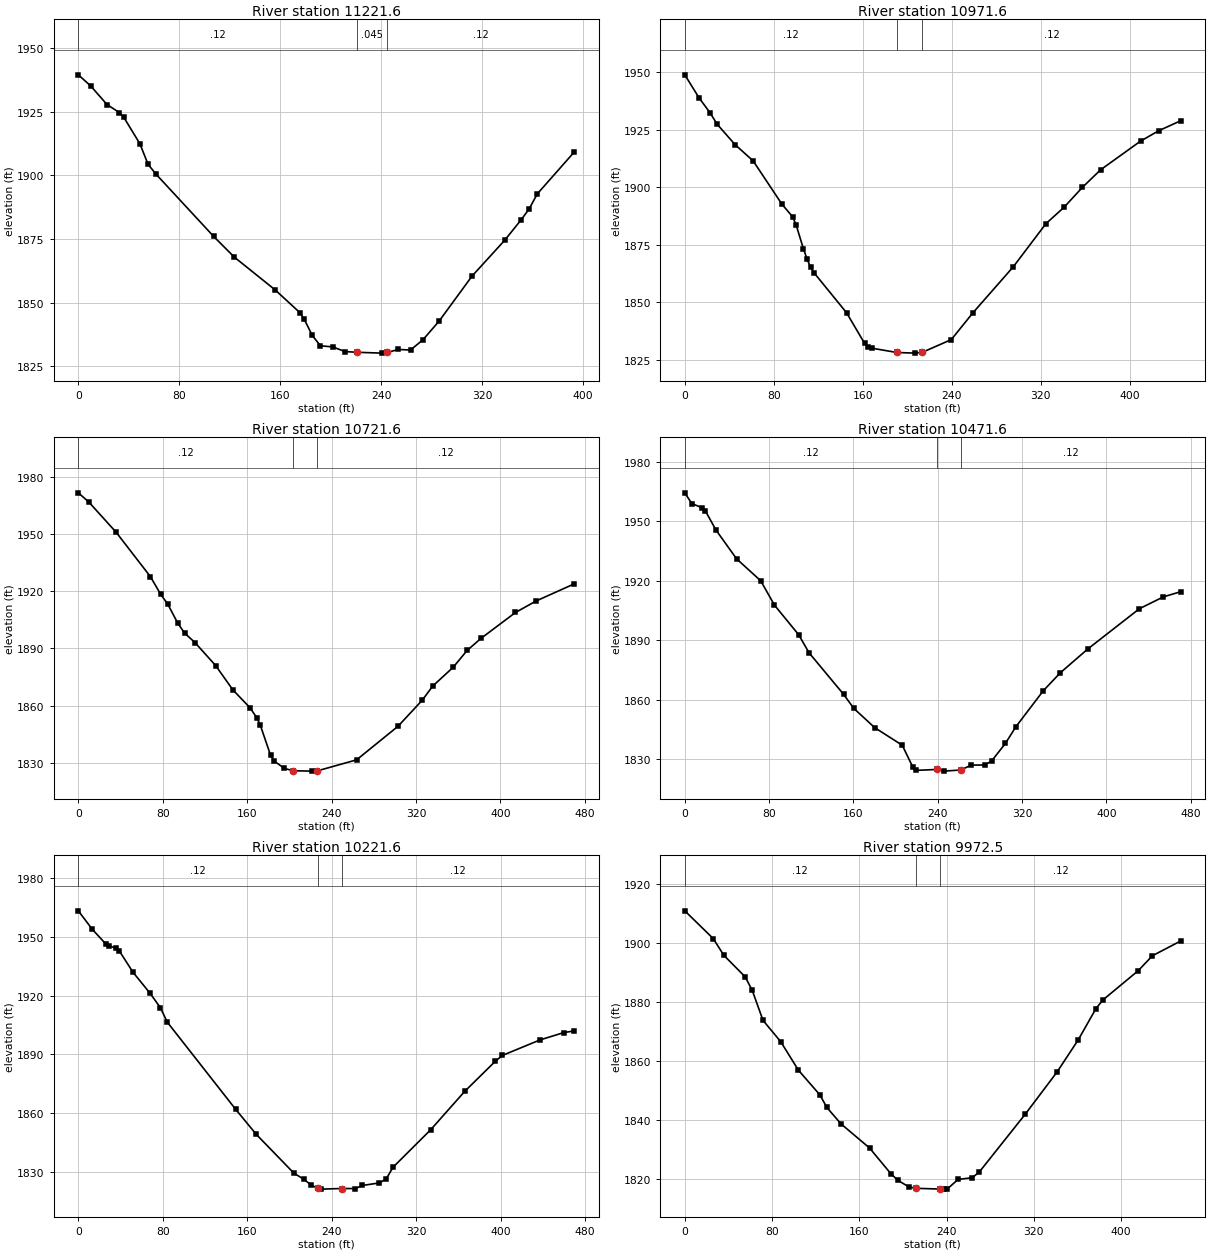
Type RM Length L Ch R = 1 ,11221.6 ,245.1,250,251.1
XS GIS Cut Line= 3
     2099059.048      197483.835     2098991.808      197701.381
     2098944.897      197859.844
#Sta/Elev= 30
       0 1939.48     9.8 1935.12    22.8 1927.77    32.5 1924.69    35.8 1922.99
    48.8 1912.41    55.3 1904.31    61.8 1900.36   107.3 1876.02   123.6 1867.93
   156.1 1855.01   175.6 1846.12   178.9 1843.69   185.4 1837.19   191.9 1833.11
   201.7 1832.67   211.4 1830.83   221.2 1830.56   240.7 1830.23     2451830.527
   253.6 1831.66   263.3 1831.46   273.1 1835.45     286 1842.82     312 1860.44
   337.9 1874.51   350.8 1882.45   357.3 1886.83   363.8 1892.76     393 1909.14
#Mann= 3 ,-1 , 0
       0     .12       0   221.2    .045       0     245     .12       0
Bank Sta=221.2,245
XS Rating Curve= 0 ,0
Exp/Cntr=0.3,0.1

Type RM Length L Ch R = 1 ,10971.6 ,265.1,250,239.3
XS GIS Cut Line= 3
     2098873.405      197408.926     2098773.218      197586.179
      2098692.48      197814.553
#Sta/Elev= 30
       0 1948.89    12.9 1938.83    22.6 1932.46    29.1 1927.41    45.2 1918.55
    61.4 1911.52    87.3 1892.69      97 1887.16   100.2 1883.49   106.6 1873.37
   109.9 1868.86   113.1 1865.19   116.4 1862.74   145.4 1845.52   161.6 1832.22
   164.8 1830.56   168.1 1830.09   190.7 1828.22   206.9 1827.94   213.4 1828.26
   239.6 1833.82   259.2 1845.55   295.3 1865.43   324.7  1884.2   341.1 1891.38
   357.4 1899.94   373.8 1907.59   409.8 1920.09   426.2 1924.61   445.8 1928.92
#Mann= 3 ,-1 , 0
       0     .12       0   190.7    .045       0   213.4     .12       0
Bank Sta=190.7,213.4
XS Rating Curve= 0 ,0
Exp/Cntr=0.3,0.1

Type RM Length L Ch R = 1 ,10721.6 ,255,250,243.1
XS GIS Cut Line= 3
     2098493.573       197360.26     2098528.541      197572.058
     2098559.657      197825.296
#Sta/Elev= 30
       0 1971.65     9.8  1966.9    35.8 1950.98    68.3 1927.67    78.1 1918.34
    84.6 1913.39    94.3 1903.16   100.8    1898   110.6 1893.05   130.1 1881.03
   146.4 1868.29   162.6 1858.93   169.1 1853.65   172.4 1849.79   182.1 1834.03
   185.4    1831   195.2 1827.09   203.31825.841   221.2 1825.64     226 1825.71
   263.7 1831.57     303 1849.22   325.9 1862.87   335.7 1870.21   355.3  1880.2
   368.4 1888.97   381.5 1895.27   414.2 1908.87   433.8 1914.92   469.8 1923.87
#Mann= 3 ,-1 , 0
       0     .12       0   203.3    .045       0     226     .12       0
Bank Sta=203.3,226
XS Rating Curve= 0 ,0
Exp/Cntr=0.3,0.1

Type RM Length L Ch R = 1 ,10471.6 ,250.6,250,251.1
XS GIS Cut Line= 3
     2098196.087      197420.191     2098292.602      197653.094
     2098381.805      197852.368
#Sta/Elev= 30
       0 1964.35     6.6 1958.96    16.4  1956.8    19.6 1955.16    29.5 1945.63
    49.1 1931.04      72 1919.95    85.1 1907.63     108 1892.72   117.9 1883.57
   150.6 1862.65   160.4 1855.49   180.1 1845.82   206.3 1836.91   216.1 1826.12
   219.4 1824.23     239 1824.67   245.6 1823.84   261.9 1824.41   271.7 1826.89
   284.7 1826.93   291.2 1829.03   304.2 1837.86     314 1846.17   340.1 1864.42
   356.4 1873.56   382.4 1885.54   431.3 1905.84   454.1 1911.84   470.4 1914.42
#Mann= 3 ,-1 , 0
       0     .12       0     239    .045       0   261.9     .12       0
Bank Sta=239,261.9
XS Rating Curve= 0 ,0
Exp/Cntr=0.3,0.1

Type RM Length L Ch R = 1 ,10221.6 ,257.9,249.1,240.6
XS GIS Cut Line= 3
       2097950.9      197488.616     2098051.234      197709.953
     2098131.973      197921.638
#Sta/Elev= 30
       0 1963.25      13 1953.95    25.9 1946.38    29.2 1945.22    35.6 1944.32
    38.9  1942.7    51.8 1931.87      68 1921.11    77.8 1913.72    84.2 1906.43
     149 1861.88   168.5 1849.11   204.1 1829.31   213.8 1826.08   220.3  1823.3
   226.8 1821.48   230.1 1821.13   249.5 1821.45   262.4 1821.41   268.9 1822.99
   285.1  1824.3   291.6 1826.34     298 1832.28   333.6 1851.39     366 1871.08
   395.1 1886.51   401.6  1889.4   437.2 1897.31   459.9  1901.1   469.6  1901.9
#Mann= 3 ,-1 , 0
       0     .12       0   226.8    .045       0   249.5     .12       0
Bank Sta=226.8,249.5
XS Rating Curve= 0 ,0
Exp/Cntr=0.3,0.1

Type RM Length L Ch R = 1 ,9972.5  ,247.3,248.9,248.3
XS GIS Cut Line= 3
      2097672.49       197692.42     2097836.083      197831.923
     2097998.058      198008.645
#Sta/Elev= 30
       0 1910.99    26.1 1901.56    35.8  1895.9    55.4 1888.57    61.9 1883.96
    71.7 1873.83      88 1866.58   104.2 1856.91   123.8 1848.58   130.3 1844.26
   143.3 1838.68   169.4 1830.53   188.9 1821.82   195.4 1819.55   205.2 1817.38
   211.7 1816.84   234.4 1816.58   237.7 1816.56   240.9 1816.66   250.6 1819.86
   263.6 1820.42   270.1 1822.39   312.2 1841.98   341.3 1856.26   360.8 1867.21
     377 1877.78   383.4 1880.74   415.8 1890.67   428.8 1895.74   454.7 1900.75
#Mann= 3 ,-1 , 0
       0     .12       0   211.7    .045       0   234.4     .12       0
Bank Sta=211.7,234.4
XS Rating Curve= 0 ,0
Exp/Cntr=0.3,0.1