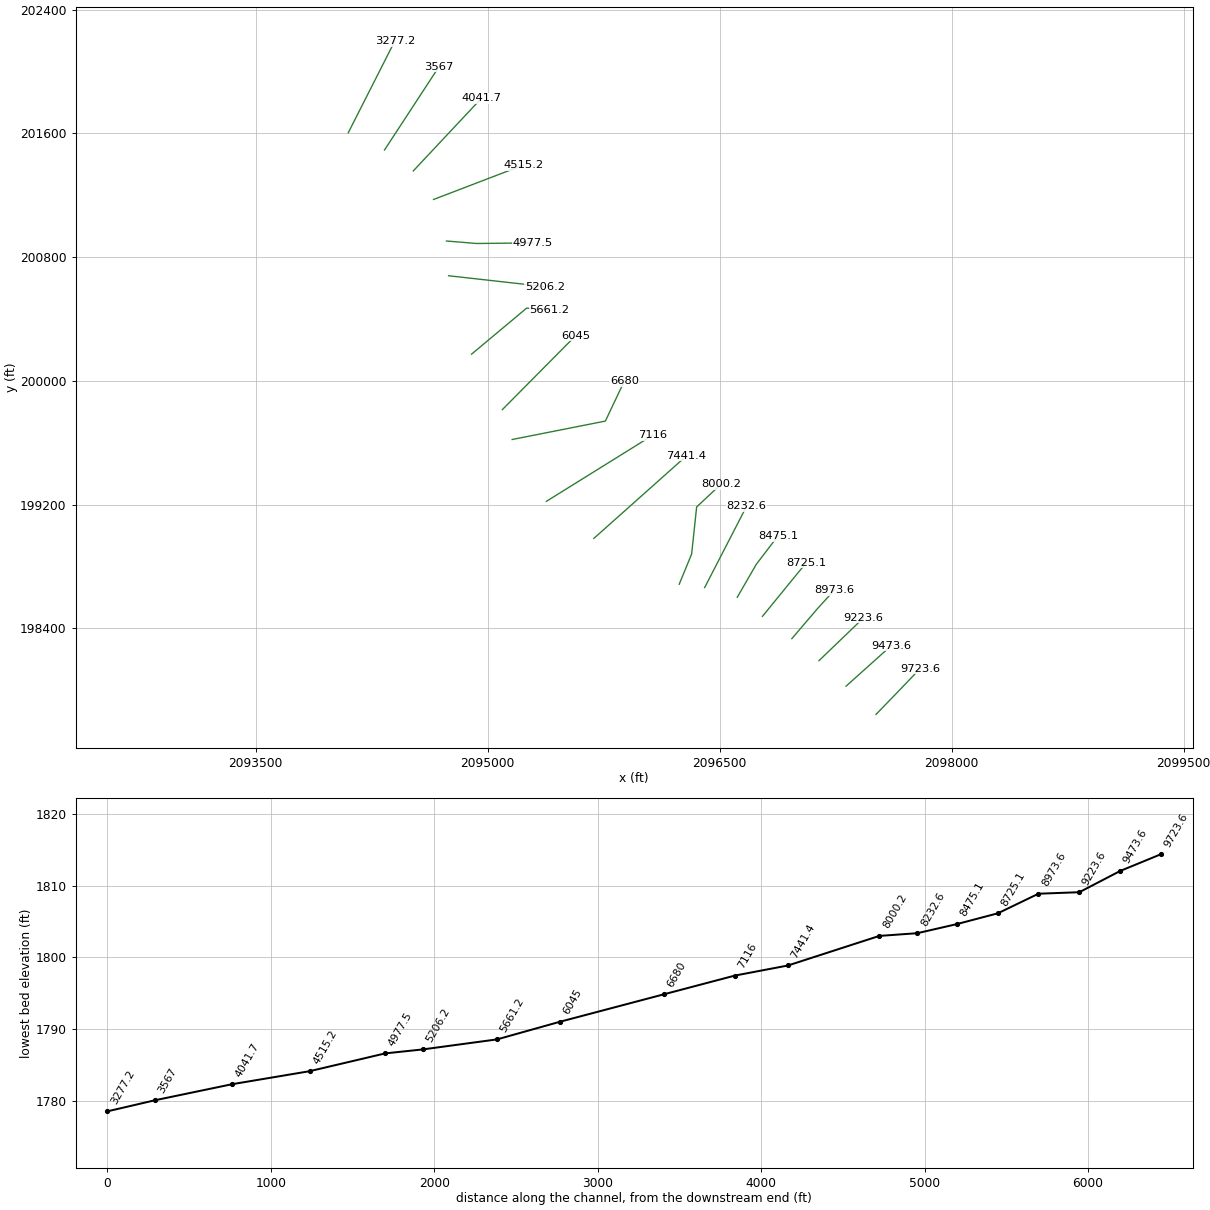
HEC-RAS study TRKYCK.prj: TRKYCK

--- TRKYCK.g01 (geometry) --- (continued)

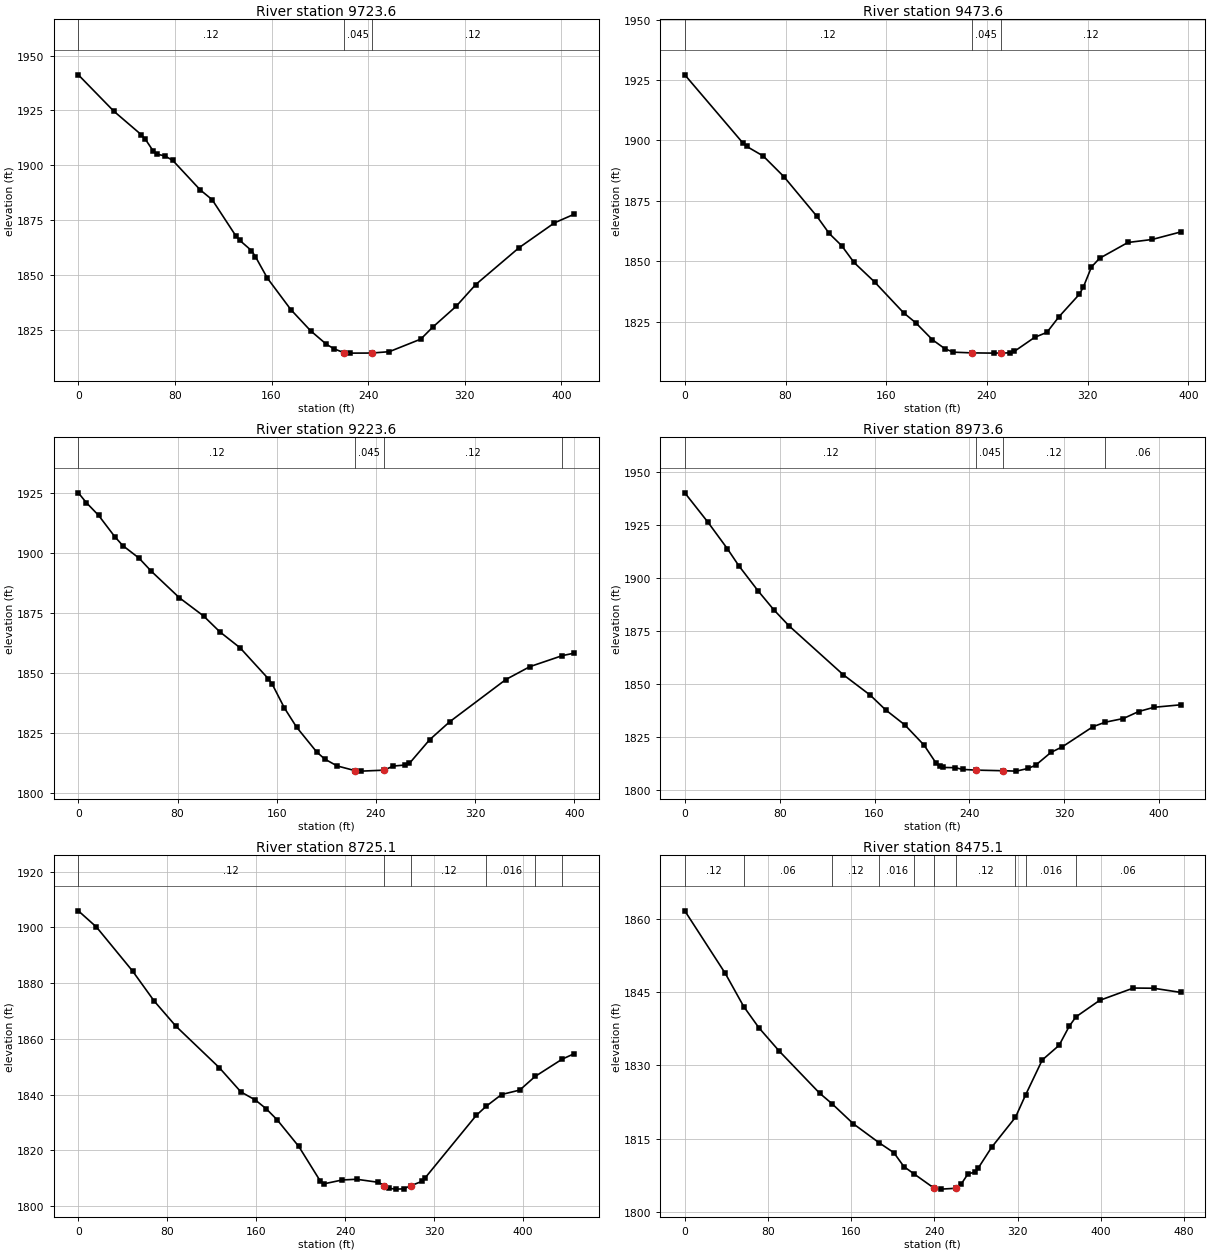
Type RM Length L Ch R = 1 ,9723.6  ,251.6,250,248.2
XS GIS Cut Line= 3
     2097511.427      197843.982      2097672.43      198010.246
      2097795.96      198139.952
#Sta/Elev= 30
       0 1941.23    29.3  1924.7    52.2  1913.9    55.4 1911.95    61.9 1906.59
    65.2 1905.06    71.7 1904.26    78.2 1902.22     101 1888.75   110.8 1884.33
   130.4 1867.85   133.6 1865.82   143.4 1861.11   146.7 1858.32   156.5  1848.6
     176  1834.2   192.3  1824.6   205.4 1818.42   211.9 1816.31     2201814.574
   224.9 1814.38   242.91814.416   257.5 1815.04   283.6 1820.77   293.3 1826.13
   312.9 1835.74   329.1 1845.64     365 1862.45   394.3 1873.76   410.6 1877.69
#Mann= 3 ,-1 , 0
       0     .12       0     220    .045       0   242.9     .12       0
Bank Sta=220,242.9
XS Rating Curve= 0 ,0
Exp/Cntr=0.3,0.1

Type RM Length L Ch R = 1 ,9473.6  ,249.1,250,250.7
XS GIS Cut Line= 3
     2097317.674      198026.306     2097495.851       198186.05
     2097610.863      198289.164
#Sta/Elev= 30
       0 1927.13    45.9 1899.08    49.2 1897.51    62.3 1893.55    78.7 1885.02
   104.9 1868.62   114.7 1861.52   124.6 1856.47   134.4 1849.53   150.8 1841.44
   173.7 1828.76   183.6  1824.5   196.7 1817.56   206.5 1813.89   213.1 1812.44
   227.81812.146   245.7 1812.04   250.81812.088   258.6 1812.16   261.8 1812.79
   277.9 1818.58   287.6 1820.62   297.2  1827.1   313.3 1836.34   316.5 1839.31
     323 1847.67   329.4 1851.25   351.9 1857.79   371.2 1859.04   393.8 1862.14
#Mann= 3 ,-1 , 0
       0     .12       0   227.8    .045       0   250.8     .12       0
Bank Sta=227.8,250.8
XS Rating Curve= 0 ,0
Exp/Cntr=0.3,0.1

Type RM Length L Ch R = 1 ,9223.6  ,247.7,250,251.4
XS GIS Cut Line= 3
     2097142.515      198191.132     2097311.673      198353.782
     2097430.666      198468.198
#Sta/Elev= 30
       0  1924.9     6.5 1920.79    16.3 1915.54    29.3 1906.71    35.8 1902.96
    48.9 1897.74    58.7 1892.34    81.5 1881.22     101 1873.64   114.1 1867.05
   130.4 1860.41   153.2 1847.53   156.4 1845.21   166.2 1835.33     176 1827.37
   192.3 1816.99   198.8 1814.07   208.6 1811.26   223.21809.269   228.2 1809.08
   246.21809.474   254.1 1811.19   263.8 1811.64     267 1812.33   283.2 1822.11
   299.4 1829.61   344.7 1847.19   364.1 1852.56  390.361857.165   399.8 1858.17
#Mann= 4 ,-1 , 0
       0     .12       0   223.2    .045       0   246.2     .12       0
  390.36     .06       0
Bank Sta=223.2,246.2
XS Rating Curve= 0 ,0
Exp/Cntr=0.3,0.1

Type RM Length L Ch R = 1 ,8973.6  ,247.8,248.5,249.5
XS GIS Cut Line= 3
     2096967.141      198333.579     2097134.148      198529.149
     2097242.739      198647.877
#Sta/Elev= 30
       0 1939.97    19.5 1926.14    35.8 1913.72    45.6 1905.58    61.8 1893.78
    74.9 1884.97    87.9  1877.3   133.5 1854.34   156.3 1844.69   169.3 1837.75
   185.6 1830.61   201.8 1821.09   211.6 1812.88   214.9 1811.16   218.1 1810.59
   227.9  1810.5   234.4 1809.67   245.61809.346   268.71809.048   279.7 1808.87
   289.4 1810.15   295.8 1811.63   308.7 1817.67   318.3 1820.31   344.1 1829.78
  354.47 1831.91   369.8 1833.65   382.7 1836.94   395.6 1838.94   418.1 1840.11
#Mann= 4 ,-1 , 0
       0     .12       0   245.6    .045       0   268.7     .12       0
  354.47     .06       0
Bank Sta=245.6,268.7
XS Rating Curve= 0 ,0
Exp/Cntr=0.3,0.1

Type RM Length L Ch R = 1 ,8725.1  ,246.1,250,250.5
XS GIS Cut Line= 3
     2096777.124      198477.582     2096960.032        198701.9
     2097059.487      198823.087
#Sta/Elev= 30
       0 1905.96    16.3 1900.15    48.8 1884.37    68.3 1873.58    87.8 1864.59
   126.8 1849.73   146.3 1841.01   159.4 1838.08   169.1 1834.95   178.9 1831.01
   198.4 1821.44   217.9 1808.93   221.1 1808.04   237.4 1809.42   250.4 1809.68
   269.9 1808.59  275.271807.411   279.7 1806.39   286.2 1806.14   292.7 1806.24
   299.2 1807.36     309  1808.9   312.3 1810.27     358 1832.55  366.891835.819
   380.9 1840.08   397.2 1841.66  411.061846.552  435.421852.761   446.2 1854.71
#Mann= 6 ,-1 , 0
       0     .12       0  275.27    .045       0   299.2     .12       0
  366.89    .016       0  411.06     .06       0  435.42     .12       0
Bank Sta=275.27,299.2
XS Rating Curve= 0 ,0
Exp/Cntr=0.3,0.1

Type RM Length L Ch R = 1 ,8475.1  ,241.2,242.5,246.4
XS GIS Cut Line= 3
     2096614.216      198601.042     2096737.469      198814.246
     2096877.342      198997.238
#Sta/Elev= 30
       0 1861.59    38.9 1848.79   56.67 1841.99    71.3 1837.64    90.7  1832.9
   129.6 1824.27  141.381822.144     162 1818.01   186.81814.123   200.9 1812.11
   210.6 1809.25  220.361807.754   239.8 1804.81   246.3 1804.64  260.411804.812
   265.7 1805.68   272.2 1807.76   278.7 1808.11     282 1808.93   294.9 1813.19
  317.871819.352  327.491823.875   343.6 1831.07   359.8 1834.07   369.5 1837.96
  375.981839.894   398.7 1843.26   431.2 1845.79   450.6 1845.75   476.6  1844.9
#Mann= 10 ,-1 , 0
       0     .12       0   56.67     .06       0  141.38     .12       0
   186.8    .016       0  220.36     .12       0   239.8    .045       0
  260.41     .12       0  317.87     .06       0  327.49    .016       0
  375.98     .06       0
Bank Sta=239.8,260.41
XS Rating Curve= 0 ,0
Exp/Cntr=0.3,0.1

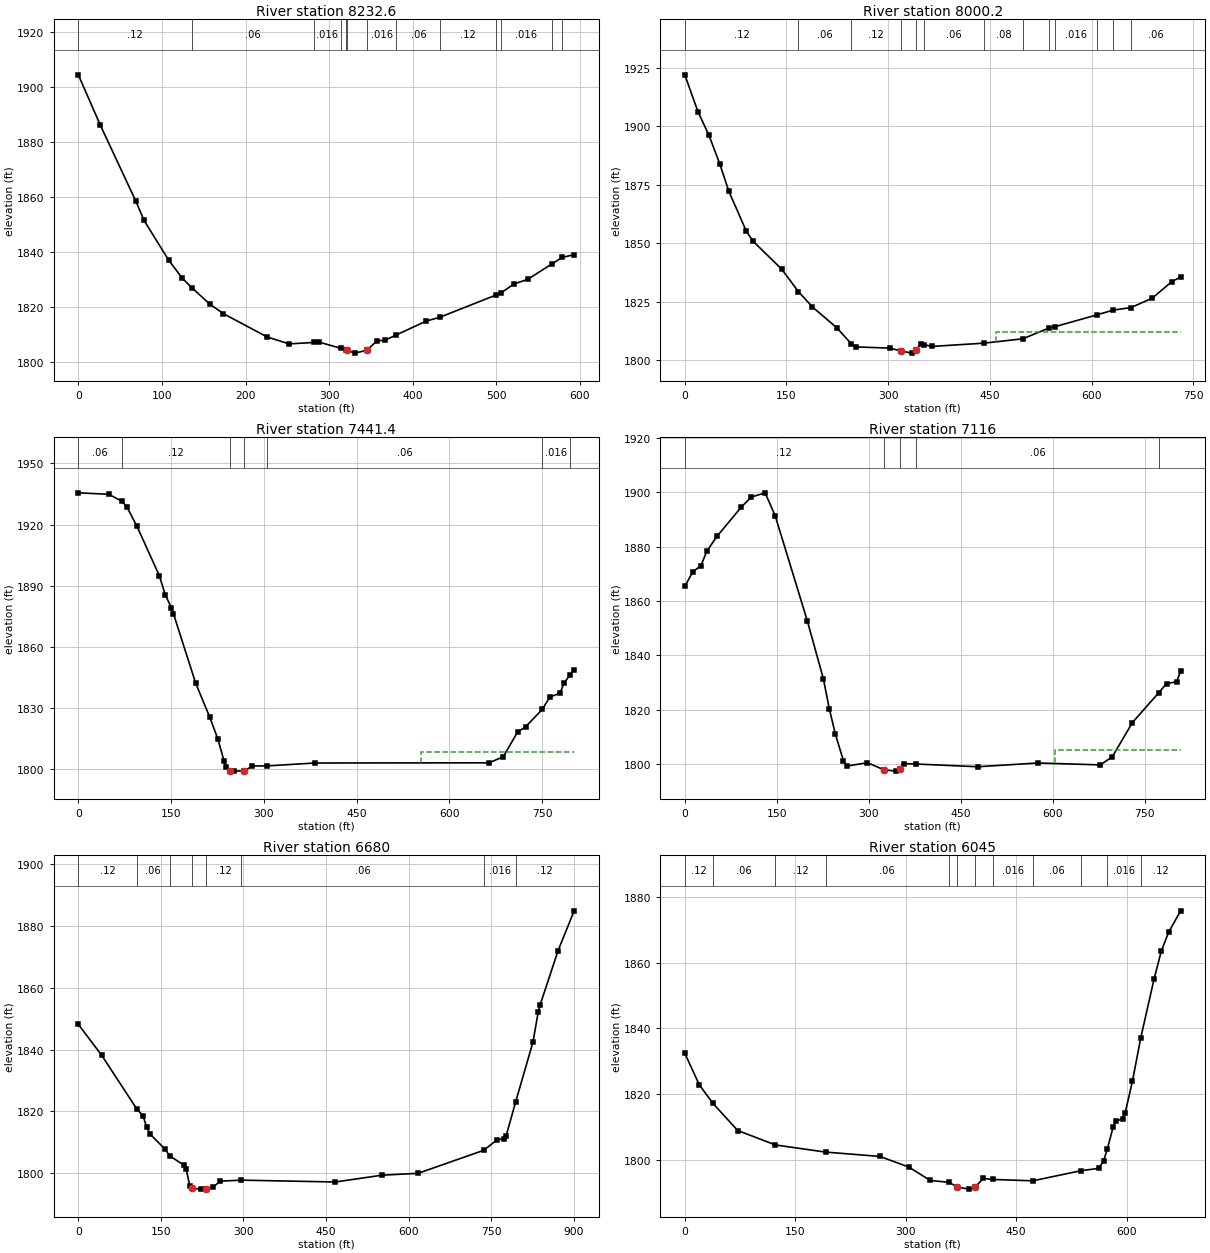
Type RM Length L Ch R = 1 ,8232.6  ,223.3,232.5,240.3
XS GIS Cut Line= 2
     2096403.381      198663.532     2096675.179      199190.529
#Sta/Elev= 30
       0 1904.37    26.2 1886.17    68.8 1858.52    78.6 1851.52   108.1  1837.1
   124.5 1830.49  136.131827.014   157.2 1821.16   173.6 1817.68     226 1809.21
   252.2 1806.72  281.411807.239   288.3 1807.34  314.341805.082  320.151804.536
     321  1804.4   330.9 1803.37  345.071804.432   357.1  1807.8   366.9 1808.08
   380.41809.991     416 1814.98  432.991816.463  499.461824.448  505.771825.289
   520.9 1828.45   537.3 1830.12  565.941835.657  578.651838.083     593 1839.13
#Mann= 13 ,-1 , 0
       0     .12       0  136.13     .06       0  281.41    .016       0
  314.34     .12       0  320.15    .016       0     321    .045       0
  345.07    .016       0   380.4     .06       0  432.99     .12       0
  499.46     .06       0  505.77    .016       0  565.94     .06       0
  578.65     .08       0
Bank Sta=321,345.07
XS Rating Curve= 0 ,0
Exp/Cntr=0.3,0.1

Type RM Length L Ch R = 1 ,8000.2  ,574.8,558.8,541.3
XS GIS Cut Line= 4
     2096238.918      198685.227     2096319.167      198880.115
     2096351.719      199184.803     2096508.221      199331.024
#Sta/Elev= 30
       0 1921.95    19.5 1906.13    35.7 1896.07    51.9 1883.65    64.8 1872.29
    90.8 1855.06   100.5 1850.88   142.7 1838.96  167.611829.276   188.1 1822.77
   223.8 1813.94  245.58    1807   253.1 1805.63     302 1805.14   318.21803.995
   334.6 1802.99   341.2 1804.16   347.7 1806.76  352.881806.646     364 1805.84
  441.73 1807.26  498.771809.129  537.461813.755  546.631814.351  607.621819.308
   631.41821.336  658.411822.487   689.2 1826.43   718.4 1833.52   731.4 1835.54
#Mann= 13 ,-1 , 0
       0     .12       0  167.61     .06       0  245.58     .12       0
   318.2    .045       0   341.2     .12       0  352.88     .06       0
  441.73     .08       0  498.77     .06       0  537.46     .12       0
  546.63    .016       0  607.62     .12       0   631.4    .016       0
  658.41     .06       0
#XS Ineff= 2 , 0
                          459.03         1811.82
Permanent Ineff=
       F       F
Bank Sta=318.2,341.2
XS Rating Curve= 0 ,0
Exp/Cntr=0.3,0.1

Type RM Length L Ch R = 1 ,7441.4  ,329.3,325.3,321.4
XS GIS Cut Line= 2
     2095687.121      198981.446     2096285.701       199514.76
#Sta/Elev= 30
       0 1935.56    49.1 1934.85   70.481931.455    78.5 1928.62    94.9 1919.07
   130.9 1894.91   140.7 1885.35   150.5 1879.13   153.8 1876.21   189.8 1842.01
   212.7 1825.22   225.8 1814.44   235.6 1803.83   238.9 1801.11   245.4 1799.07
     252 1798.87   268.3 1799.02   281.4  1801.4  304.79 1801.44   382.8 1802.86
   664.3 1802.95   687.2 1805.98   710.1 1818.03   723.2 1820.68  750.121829.148
   762.4 1835.28   778.8 1837.15   785.3 1842.16     7951846.052   801.7 1848.73
#Mann= 7 ,-1 , 0
       0     .06       0   70.48     .12       0   245.4    .045       0
   268.3     .12       0  304.79     .06       0  750.12    .016       0
     795     .12       0
#XS Ineff= 2 , 0
                          554.18         1808.11
Permanent Ineff=
       F       F
Bank Sta=245.4,268.3
XS Rating Curve= 0 ,0
Exp/Cntr=0.3,0.1

Type RM Length L Ch R = 1 ,7116    ,443.4,436.1,427.3
XS GIS Cut Line= 2
     2095380.239      199221.002     2096066.562      199647.694
#Sta/Elev= 30
       0 1865.38    13.1 1870.72    26.2 1872.94      36 1878.34    52.4 1883.75
    91.6 1894.37     108 1898.16   130.9 1899.75   147.2 1891.41   199.6 1852.79
   225.8 1831.47   235.6 1820.33   245.4 1811.07   258.5 1801.35     265 1799.36
   297.7 1800.56   323.9 1798.01   343.6 1797.46   350.1 1798.12   356.6 1800.22
  377.36 1800.07   477.7 1799.07   575.8 1800.46   677.3 1799.75   696.9 1802.74
   729.6 1815.32  772.231826.198   785.2 1829.62   801.6  1830.3   808.2 1834.21
#Mann= 5 ,-1 , 0
       0     .12       0   323.9    .045       0   350.1     .12       0
  377.36     .06       0  772.23    .016       0
#XS Ineff= 2 , 0
                          603.72          1805.3
Permanent Ineff=
       F       F
Bank Sta=323.9,350.1
XS Rating Curve= 0 ,0
Exp/Cntr=0.3,0.1

Type RM Length L Ch R = 1 ,6680    ,620.4,635,633.8
XS GIS Cut Line= 3
     2095159.196      199620.799     2095761.658      199739.924
      2095884.46      199999.073
#Sta/Elev= 30
       0 1848.19    42.5 1838.16     1061820.854   117.6 1818.54   124.1 1814.97
   130.7 1812.58   156.8 1807.93  166.261805.545   192.7 1802.54     196 1801.32
   202.5 1795.93   205.8 1795.13   222.1 1794.84   231.9 1795.03     245 1795.54
   258.1 1797.42  296.371797.747   467.1 1797.15   552.1 1799.36   617.4 1799.96
  736.56 1807.41   760.8 1810.81   773.8 1811.16   777.1 1811.99  794.551823.057
     826 1842.42   835.7 1852.29     839 1854.44   871.6 1872.03   900.9 1884.95
#Mann= 8 ,-1 , 0
       0     .12       0     106     .06       0  166.26     .12       0
   205.8    .045       0   231.9     .12       0  296.37     .06       0
  736.56    .016       0  794.55     .12       0
Bank Sta=205.8,231.9
XS Rating Curve= 0 ,0
Exp/Cntr=0.3,0.1

Type RM Length L Ch R = 1 ,6045    ,384.4,383.8,382.2
XS GIS Cut Line= 2
     2095095.747      199814.117     2095569.705      200292.137
#Sta/Elev= 30
       0 1832.43    19.6 1822.85   38.18 1817.16    71.9 1808.88  122.981804.491
  191.111802.311   264.7 1800.99   303.9 1797.78   333.3 1793.66  358.481793.106
   370.21791.657   385.6 1791.02   393.91791.583   405.2 1794.28     4191793.962
  472.411793.554  537.961796.639     562 1797.34   568.6 1799.62  573.451803.121
   581.7 1810.02   584.9 1811.64   594.7  1812.5     598 1814.37   607.8 1823.94
  619.16 1837.23   637.2 1855.11     647  1863.6   656.8 1869.28   673.2 1875.85
#Mann= 12 ,-1 , 0
       0     .12       0   38.18     .06       0  122.98     .12       0
  191.11     .06       0  358.48     .12       0   370.2    .045       0
   393.9     .06       0     419    .016       0  472.41     .06       0
  537.96     .12       0  573.45    .016       0  619.16     .12       0
Bank Sta=370.2,393.9
XS Rating Curve= 0 ,0
Exp/Cntr=0.3,0.1

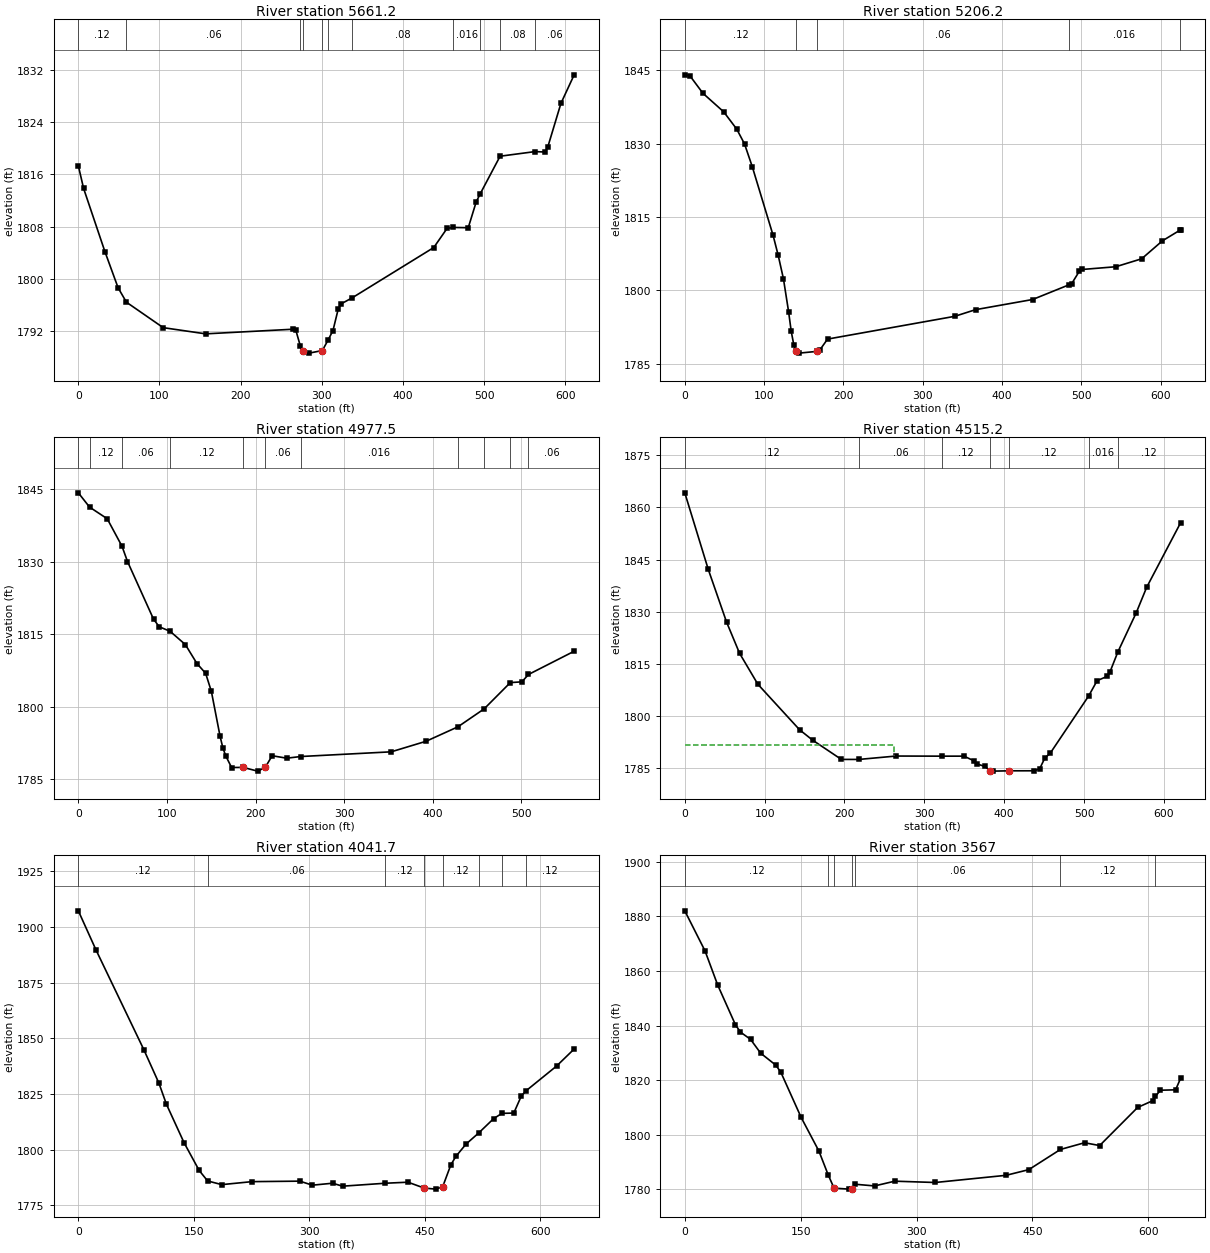
Type RM Length L Ch R = 1 ,5661.2  ,472.7,455,435.7
XS GIS Cut Line= 3
     2094896.609      200172.498      2095252.76      200470.176
     2095399.223      200459.715
#Sta/Elev= 30
       0 1817.32     6.5 1813.85    32.7 1804.17      49  1798.6   59.25 1796.39
   104.6 1792.48   156.9 1791.53   264.8 1792.24     268  1792.1  273.571789.664
  276.241788.883   284.4 1788.57   300.7 1788.97   307.51790.519   313.8 1792.04
   320.3 1795.36   323.6 1796.12  337.251797.042     438 1804.78   454.4 1807.72
  461.481807.865   480.5 1807.82   490.3 1811.79  495.241813.027  519.721818.797
  562.771819.505   575.1 1819.44   578.4 1820.17   594.7 1826.91     611 1831.29
#Mann= 11 ,-1 , 0
       0     .12       0   59.25     .06       0  273.57     .08       0
  276.24    .045       0   300.7     .08       0   307.5     .06       0
  337.25     .08       0  461.48    .016       0  495.24     .06       0
  519.72     .08       0  562.77     .06       0
Bank Sta=276.24,300.7
XS Rating Curve= 0 ,0
Exp/Cntr=0.3,0.1

Type RM Length L Ch R = 1 ,5206.2  ,227.8,228.7,231.3
XS GIS Cut Line= 2
      2094748.35      200679.372     2095369.628      200609.663
#Sta/Elev= 30
       0  1844.1     6.6 1843.87    22.9 1840.32    49.1 1836.52    65.5 1832.99
    75.3 1829.97    85.1  1825.3   111.3 1811.28   117.8 1807.16   124.4 1802.36
   130.9 1795.62   134.2 1791.62   137.5 1788.82  140.361787.572     144 1787.17
   166.9 1787.53   170.2  1787.8     180 1790.04   340.4  1794.7   366.6 1796.06
   438.6 1798.14  483.881801.107   487.7 1801.34   497.5 1803.93   500.8 1804.28
   543.4 1804.84   576.1 1806.47   602.3 1810.15  624.38 1812.32   625.2 1812.38
#Mann= 5 ,-1 , 0
       0     .12       0  140.36    .045       0   166.9     .06       0
  483.88    .016       0  624.38     .06       0
Bank Sta=140.36,166.9
XS Rating Curve= 0 ,0
Exp/Cntr=0.3,0.1

Type RM Length L Ch R = 1 ,4977.5  ,455.2,462.3,469.7
XS GIS Cut Line= 3
     2094734.171      200904.021     2094929.404      200887.905
     2095293.212      200891.893
#Sta/Elev= 30
       0 1844.28   12.651841.327    32.6 1838.91   49.311833.205    55.5 1830.05
    84.9  1818.1    91.4 1816.52  103.531815.602   120.8 1812.84   133.9 1808.91
   143.7 1806.89   150.2 1803.12     160 1793.84   163.2  1791.4   166.5 1789.74
     173 1787.37   186.1 1787.39   202.4 1786.62  210.911787.375   218.8 1789.81
   235.2  1789.3  251.311789.649   353.2 1790.62   392.6 1792.81  428.551795.806
   458.1 1799.52  487.641804.963   500.7 1805.12  508.141806.643   559.7 1811.46
#Mann= 11 ,-1 , 0
       0     .06       0   12.65     .12       0   49.31     .06       0
  103.53     .12       0   186.1    .045       0  210.91     .06       0
  251.31    .016       0  428.55     .06       0   458.1     .08       0
  487.64    .016       0  508.14     .06       0
Bank Sta=186.1,210.91
XS Rating Curve= 0 ,0
Exp/Cntr=0.3,0.1

Type RM Length L Ch R = 1 ,4515.2  ,458.1,473.5,483
XS GIS Cut Line= 2
     2094651.299      201172.552     2095231.172      201394.667
#Sta/Elev= 30
       0 1864.19    29.4 1842.16    52.3 1827.02    68.6 1818.03    91.5 1809.13
   143.8 1796.03   160.1 1793.05   196.1 1787.51  217.851787.501   264.7 1788.48
  322.711788.445   349.7 1788.45   362.8 1787.03     366 1786.21   375.8 1785.49
   382.11784.311   385.6 1784.14   406.1 1784.23   437.9 1784.24   444.5 1784.84
     451 1787.93   457.6 1789.26  505.841805.767   516.4 1810.16   529.4 1811.44
   532.7 1812.78   542.5 1818.48   565.4 1829.69   578.5 1837.03     621 1855.59
#Mann= 7 ,-1 , 0
       0     .12       0  217.85     .06       0  322.71     .12       0
   382.1    .045       0   406.1     .12       0  505.84    .016       0
   542.5     .12       0
#XS Ineff= 2 , 0
          262.23 1791.66
Permanent Ineff=
       F       F
Bank Sta=382.1,406.1
XS Rating Curve= 0 ,0
Exp/Cntr=0.3,0.1

Type RM Length L Ch R = 1 ,4041.7  ,470.7,474.7,477.9
XS GIS Cut Line= 2
     2094519.913      201357.026     2094960.289      201826.645
#Sta/Elev= 30
       0 1907.21    22.9 1889.69      85 1844.95   104.6 1829.91   114.4  1820.4
   137.3 1803.15   156.9 1790.71  167.911785.993   186.3 1784.35   225.5 1785.69
   287.6 1785.91   303.9  1784.1   330.1 1784.98   343.1 1783.65  398.561784.974
   428.1 1785.44     4491782.806   464.1 1782.33   473.11783.406   483.7 1793.24
   490.2    1797   503.3  1802.5  519.851807.527   539.2 1813.95  550.021816.331
   565.4 1816.46   575.2 1824.12  581.351826.456   620.9 1837.54   643.8  1845.2
#Mann= 8 ,-1 , 0
       0     .12       0  167.91     .06       0  398.56     .12       0
     449    .045       0   473.1     .12       0  519.85     .06       0
  550.02    .016       0  581.35     .12       0
Bank Sta=449,473.1
XS Rating Curve= 0 ,0
Exp/Cntr=0.3,0.1

Type RM Length L Ch R = 1 ,3567    ,287.1,289.8,292
XS GIS Cut Line= 2
     2094333.835      201492.233     2094685.114      202029.383
#Sta/Elev= 30
       0 1882.03    26.2 1867.34    42.6 1854.83    65.5 1840.33      72 1837.61
    85.1 1834.95    98.2 1829.88   117.9 1825.47   124.4 1822.85   150.6 1806.35
   173.6 1794.02  185.621785.295   193.2 1780.44   212.8 1780.08   216.1 1780.28
  220.92 1781.86   245.6 1781.25   271.8 1782.99   324.2 1782.51   415.9 1785.14
   445.3 1787.22  486.181794.611   517.4 1797.07     537 1796.04   586.2 1810.01
   605.8 1812.49  609.171814.026   615.6 1816.31   635.3 1816.46   641.8  1820.7
#Mann= 7 ,-1 , 0
       0     .12       0  185.62     .08       0   193.2    .045       0
   216.1     .08       0  220.92     .06       0  486.18     .12       0
  609.17    .016       0
Bank Sta=193.2,216.1
XS Rating Curve= 0 ,0
Exp/Cntr=0.3,0.1

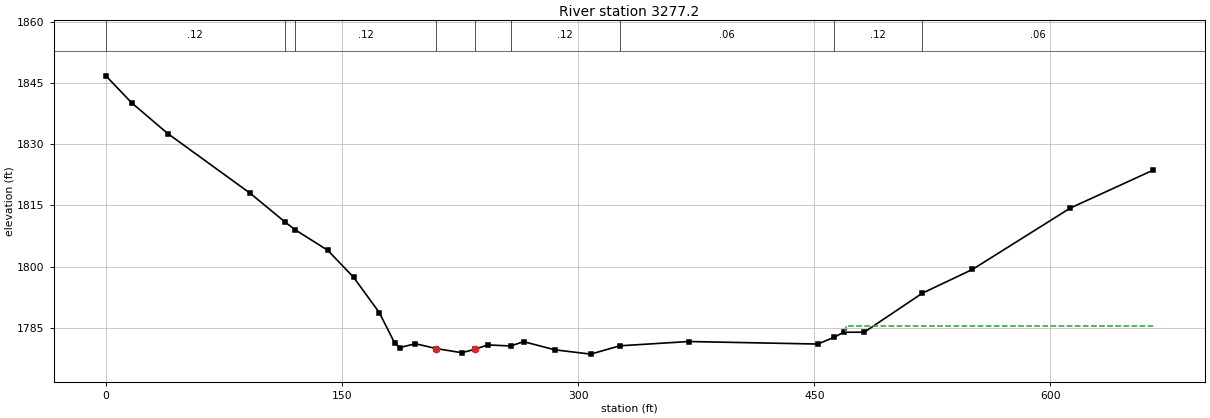
Type RM Length L Ch R = 1 ,3277.2  ,311.1,314.2,315.7
XS GIS Cut Line= 2
     2094099.641      201603.934     2094400.685      202197.062
#Sta/Elev= 30
       0 1846.76    16.4 1840.13    39.3 1832.61    91.8 1817.93  113.521811.008
  120.151809.042   140.9    1804   157.3  1797.4   173.7 1788.71   183.5 1781.21
   186.8 1780.15   196.6 1781.09     2101779.893   226.1 1778.89   234.31779.712
   242.5  1780.8  257.141780.539   265.4  1781.6   285.1  1779.6     308 1778.54
  326.421780.578   370.3 1781.63   452.2 1781.01  462.631782.665   468.6 1783.91
   481.7 1783.91  518.671793.481   550.5 1799.31   612.7 1814.36   665.2 1823.63
#Mann= 9 ,-1 , 0
       0     .12       0  113.52     .06       0  120.15     .12       0
     210    .045       0   234.3     .06       0  257.14     .12       0
  326.42     .06       0  462.63     .12       0  518.67     .06       0
#XS Ineff= 2 , 0
                          470.28         1785.41
Permanent Ineff=
       F       F
Bank Sta=210,234.3
XS Rating Curve= 0 ,0
Exp/Cntr=0.3,0.1