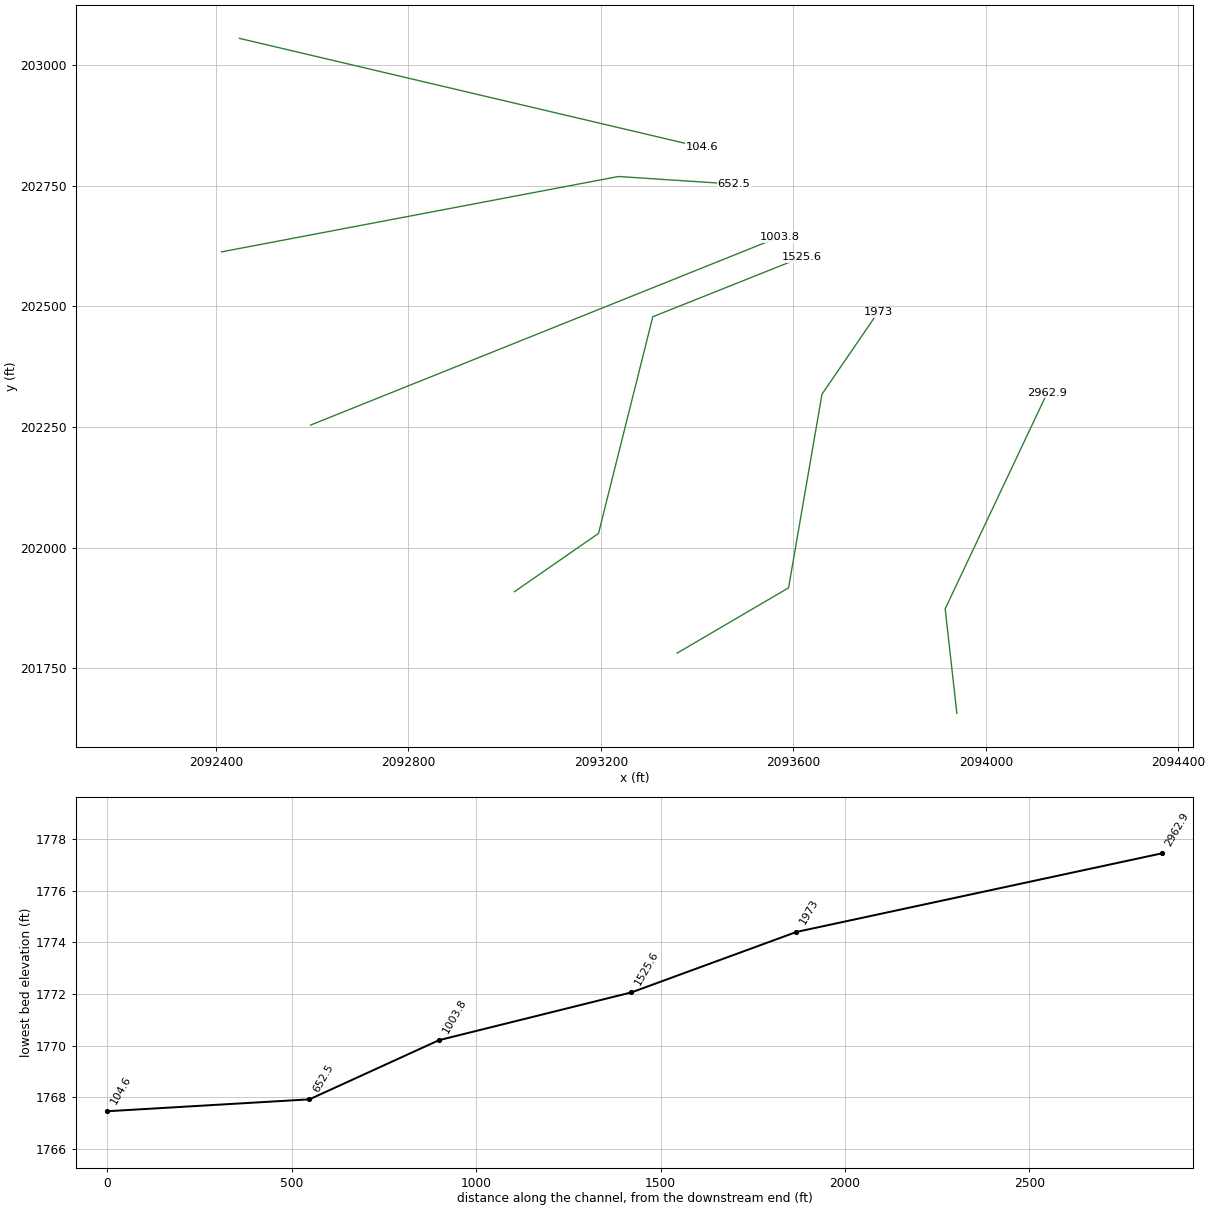
HEC-RAS study TRKYCK.prj: TRKYCK

--- TRKYCK.g01 (geometry) --- (continued)

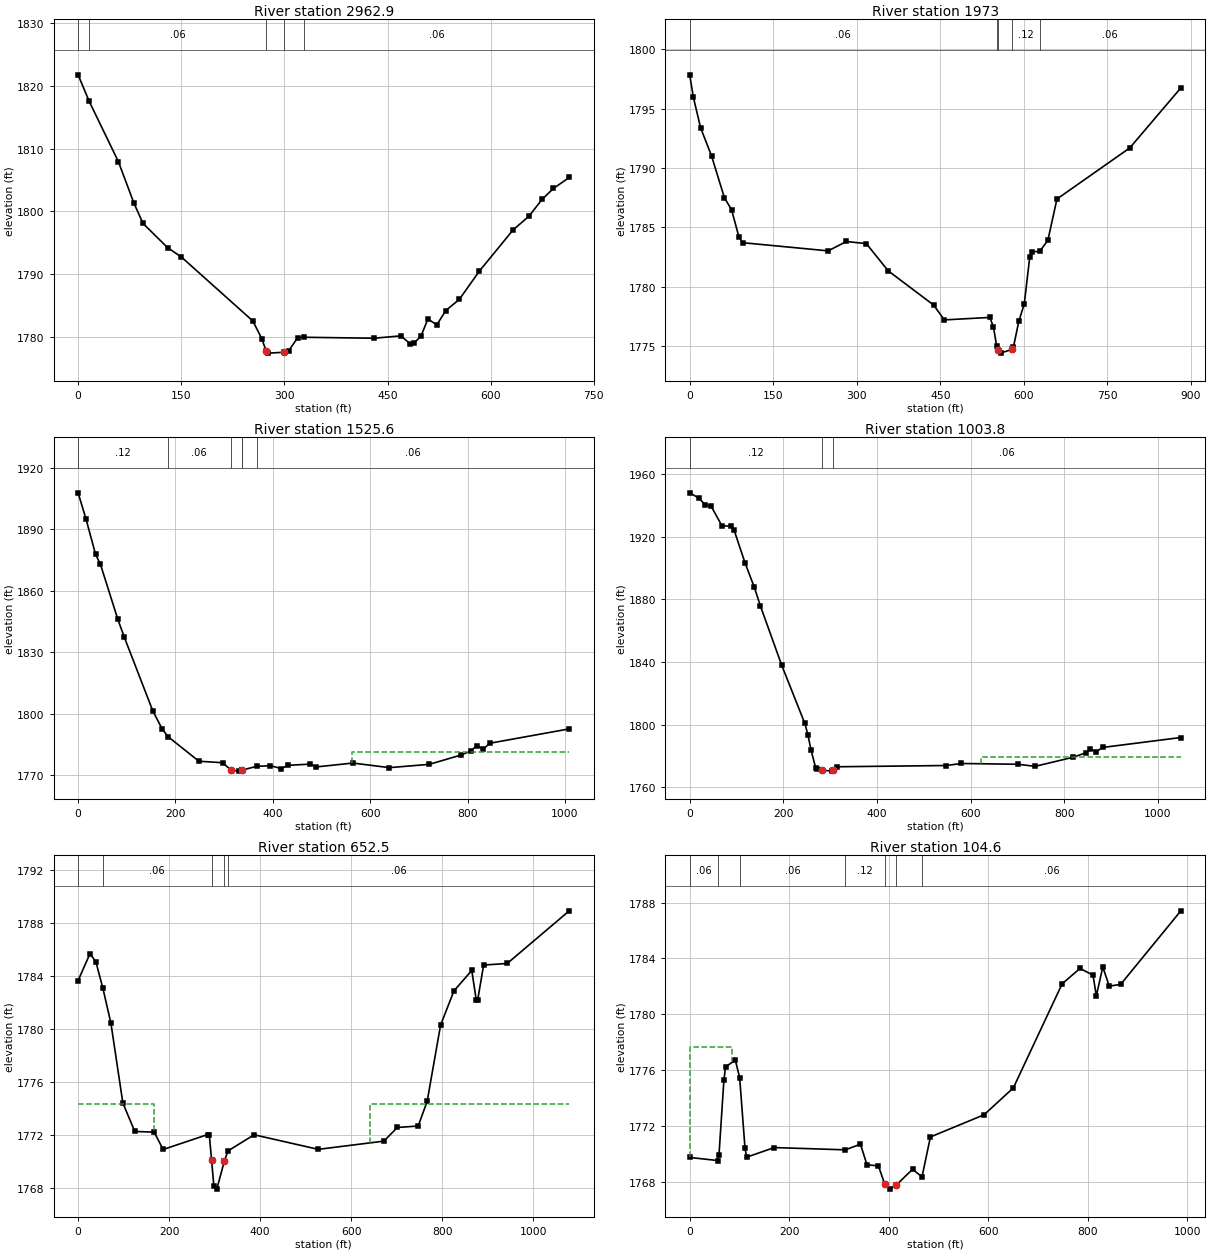
Type RM Length L Ch R = 1 ,2962.9  ,980,989.9,992
XS GIS Cut Line= 3
     2093939.764      201656.112     2093915.521      201872.954
     2094127.897      202321.303
#Sta/Elev= 30
       0 1821.74   16.091817.531    58.6 1807.92    81.4 1801.26    94.4 1798.09
   130.3 1794.21   149.8 1792.78   254.1 1782.56   267.2 1779.73   273.7 1777.71
   276.9 1777.44   299.8 1777.58   306.3 1777.82   319.4  1779.9  327.891779.966
   430.3 1779.81   469.5 1780.19   482.6 1778.96   489.1 1779.08   498.9 1780.19
   508.7 1782.88   521.7 1781.94   534.8 1784.22   554.4 1785.99   583.7 1790.51
   632.7 1797.06   655.6 1799.22   675.1 1801.95   691.4 1803.66   714.3  1805.4
#Mann= 5 ,-1 , 0
       0     .12       0   16.09     .06       0   273.7    .045       0
   299.8     .12       0  327.89     .06       0
Bank Sta=273.7,299.8
XS Rating Curve= 0 ,0
Exp/Cntr=0.3,0.1

Type RM Length L Ch R = 1 ,1973    ,448.8,447.4,444.3
XS GIS Cut Line= 4
     2093358.358      201781.041        2093590.      201916.357
     2093659.444      202317.832     2093776.076      202487.862
#Sta/Elev= 30
       0 1797.86     6.5 1795.98    19.6 1793.39    39.3 1791.01    62.2 1787.51
    75.2 1786.48    88.3  1784.2    94.9 1783.71   248.6 1783.02   281.3 1783.81
   317.2 1783.63   356.3 1781.34   437.8 1778.46   457.3  1777.2   538.8 1777.41
   545.3 1776.63  551.02 1775.04   553.51774.624   558.3  1774.4   578.11774.712
   581.2 1774.89     591  1777.1   600.7 1778.54   610.5 1782.48   613.8 1782.94
  628.451782.975   643.1 1783.91   659.4 1787.39   790.2  1791.7   881.9 1796.76
#Mann= 5 ,-1 , 0
       0     .06       0  551.02     .12       0   553.5    .045       0
   578.1     .12       0  628.45     .06       0
Bank Sta=553.5,578.1
XS Rating Curve= 0 ,0
Exp/Cntr=0.3,0.1

Type RM Length L Ch R = 1 ,1525.6  ,542.3,521.8,498.1
XS GIS Cut Line= 4
     2093020.495      201908.494     2093195.035      202029.204
     2093307.882      202478.423     2093617.663      202601.762
#Sta/Elev= 30
       0 1907.83    16.3 1895.02    35.9 1877.77    45.7 1873.09    81.6 1846.11
    94.7 1837.54   153.4 1801.46     173  1792.5  184.611788.913   248.1 1776.89
     297 1776.16   313.3  1772.7   329.6 1772.06   336.2 1772.52  336.411772.557
  366.871774.387   394.9 1774.71   417.7 1773.29   430.8 1774.89   476.4 1775.47
   489.5 1774.11   564.5    1776   639.5 1773.76   721.2 1775.36   786.5 1779.91
   806.2 1781.84   819.2 1784.54   832.3 1782.82   845.4 1785.65  1008.8 1792.67
#Mann= 6 ,-1 , 0
       0     .12       0  184.61     .06       0   313.3    .045       0
   336.2     .06       0  336.41     .08       0  366.87     .06       0
#XS Ineff= 2 , 0
                          562.23         1781.62
Permanent Ineff=
       F       F
Bank Sta=313.3,336.2
XS Rating Curve= 0 ,0
Exp/Cntr=0.3,0.1

Type RM Length L Ch R = 1 ,1003.8  ,355,351.2,346
XS GIS Cut Line= 2
      2092596.73      202253.863     2093570.799      202643.853
#Sta/Elev= 30
       0 1948.15    19.7 1944.74    32.8 1940.56    45.9 1939.54    68.9 1927.01
    88.5 1926.87    95.1 1924.07     118 1903.49   137.7 1888.02   150.8 1875.99
   196.7 1837.78   245.9 1800.72   252.5 1793.46     259 1783.83   268.9 1772.48
   272.2 1771.28   281.71770.834   304.9 1770.21   306.51770.661   314.8    1773
   547.6  1773.8   580.4 1775.09   701.7  1774.6   737.8 1773.26   819.7 1779.13
     846 1781.93   855.8 1784.19   868.9 1782.69     882 1785.34  1049.2  1791.7
#Mann= 3 ,-1 , 0
       0     .12       0   281.7    .045       0   306.5     .06       0
#XS Ineff= 2 , 0
                          621.67         1779.39
Permanent Ineff=
       F       F
Bank Sta=281.7,306.5
XS Rating Curve= 0 ,0
Exp/Cntr=0.3,0.1

Type RM Length L Ch R = 1 ,652.5   ,552.3,547.9,498
XS GIS Cut Line= 3
     2092411.615      202612.971     2093236.267      202769.221
      2093475.95      202753.522
#Sta/Elev= 30
       0 1783.65    26.2 1785.69    39.3 1785.04   54.451783.076    72.1 1780.44
    98.4 1774.41   124.6 1772.27   167.2 1772.22   186.9 1770.91   285.2 1772.04
   288.5 1771.97  293.351770.115   298.4 1768.16   304.9 1767.92   321.3 1770.02
  329.411770.803   386.9 1772.02   527.9 1770.92   672.1 1771.54   701.6 1772.57
   747.5 1772.68   767.2 1774.54   796.7 1780.29   826.2 1782.88   865.3 1784.41
     875 1782.21   878.3 1782.19   891.3 1784.82   943.2 1784.94  1079.5 1788.91
#Mann= 5 ,-1 , 0
       0     .12       0   54.45     .06       0  293.35    .045       0
   321.3     .08       0  329.41     .06       0
#XS Ineff= 2 , 0
          167.18 1774.33  641.49         1774.33
Permanent Ineff=
       F       F
Bank Sta=293.35,321.3
XS Rating Curve= 0 ,0
Exp/Cntr=0.3,0.1

Type RM Length L Ch R = 1 ,104.6   ,107.4,104.6,93
XS GIS Cut Line= 2
     2092448.507       203055.68     2093409.947      202829.838
#Sta/Elev= 30
       0 1769.73   56.441769.508    58.9 1769.94    68.7 1775.25      72 1776.21
    91.6 1776.72  100.39 1775.46   111.2 1770.39   114.5 1769.75     170 1770.44
   312.81770.276   343.4 1770.68   356.4  1769.2   379.4 1769.13   392.4  1767.8
   402.2 1767.46   415.3 1767.75     448 1768.88  467.131768.345     484  1771.2
   591.9 1772.79   650.8 1774.72   748.9 1782.18   784.8 1783.28     811  1782.8
   817.6 1781.31   830.6 1783.38   843.7 1782.01   866.6 1782.14   987.6 1787.41
#Mann= 7 ,-1 , 0
       0     .06       0   56.44    .016       0  100.39     .06       0
   312.8     .12       0   392.4    .045       0   415.3     .12       0
  467.13     .06       0
#XS Ineff= 2 , 0
           85.66 1777.67
Permanent Ineff=
       F       F
Bank Sta=392.4,415.3
XS Rating Curve= 0 ,0
Exp/Cntr=0.3,0.1

Chan Stop Cuts=-1
Use User Specified Reach Order=0
Composite Channel Slope=5